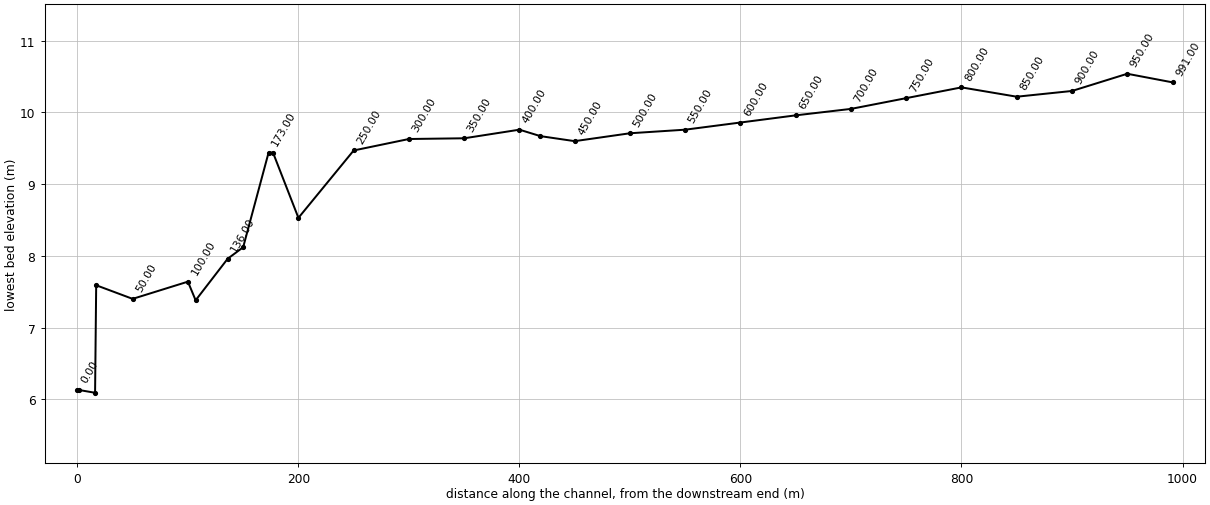
--- sdc.prj (project) ---

Proj Title=seoungdoung-ch
Current Plan=p01
Default Exp/Contr=.3,.1
SI Units
Geom File=g01
Flow File=f01
Plan File=p01
Y Axis Title=Elevation
X Axis Title(PF)=Main Channel Distance
X Axis Title(XS)=Station
BEGIN DESCRIPTION:
           BACK WATER COMPUTATION
      APPLICATION OF HEC-2 BY Samju Construction Engineering
      ¼ºµ¿Ãµ(¿ËÃµÀ¾): 30,50,80,100,150³âºóµµ °³¼öÀü
END DESCRIPTION:
DSS Export Rating Curves= 0
DSS Export Rating Curve Sorted= 0
DSS Export Volume Flow Curves= 0
DXF OffsetX= 0
DXF OffsetY= 0
DXF ScaleX= 1
DXF ScaleY= 10

--- sdc.p01 (plan) ---

Plan Title=Imported Plan 01
Version=Version 3.0.1  Mar 2001
Short Identifier=Imported Pla
Geom File=g01
Flow File=f01
Subcritical Flow
K Sum by GR= 0
Std Step Tol= 0.003
Critical Tol= 0.003
Num of Std Step Trials= 20
Max Error Tol= 0.1
Flow Tol Ratio= 0.001
Split Flow NTrial= 30
Split Flow Tol= 0.02
Split Flow Ratio= 0.02
Log Output Level= 0
Friction Slope Method= 1
Unsteady Friction Slope Method= 2
Parabolic Critical Depth
Global Vel Dist= 0 , 0 , 0
Global Log Level= 0
CheckData=True
Encroach Param=-1 ,0,0, 0
Computation Interval=1HOUR
Output Interval=1HOUR
Run HTab= 0
Run UNet= 0
Run PostProcess= 0
UNET Theta= 1
UNET ZTol= 0.02
UNET ZSATol= 0.1
UNET MxIter= 20
UNET MaxInSteps= 20
UNET DtIC= 0
UNET DtMin= 0
UNET MaxCRTS= 20
UNET WFStab= 2
UNET SFStab= 1
UNET WFX= 1
UNET SFX= 1
UNET Convert EG Bridges=-1
UNET Use Existing IB Tables=-1
Instantaneous Interval=1HOUR
Write IC File= 0
Write Velocity= 0
Write Detailed= 0

--- sdc.f01 (steady flow) ---

Flow Title=Imported Flow 01
Version=Version 3.0.1  Mar 2001
Number of Profiles= 5
Profile Names=10yr,20yr,30yr,50yr,80yr
River Rch & RM=RIVER-1,Reach-1         ,19.041
   12.58   13.87   14.62   15.57   16.44
River Rch & RM=seungdong,seungdong       ,991.00
   12.58   13.87   14.62   15.57   16.44
Boundary for River Rch & Prof#=seungdong,seungdong       , 1
Up Type= 0
Dn Type= 3
Dn Slope=.0045
Boundary for River Rch & Prof#=seungdong,seungdong       , 2
Up Type= 0
Dn Type= 3
Dn Slope=.0045
Boundary for River Rch & Prof#=seungdong,seungdong       , 3
Up Type= 0
Dn Type= 3
Dn Slope=.0045
Boundary for River Rch & Prof#=seungdong,seungdong       , 4
Up Type= 0
Dn Type= 3
Dn Slope=.0045
Boundary for River Rch & Prof#=seungdong,seungdong       , 5
Up Type= 0
Dn Type= 3
Dn Slope=.0045
DSS Import GetInterval= 0
DSS Import GetPeak= 0
DSS Import FillOption= 0

--- sdc.g01 (geometry) ---

Geom Title=Imported Geom 01
Version=Version 3.0.1  Mar 2001

River Reach=seungdong       ,seungdong
Reach XY= 2
              .5             .95              .5             .05

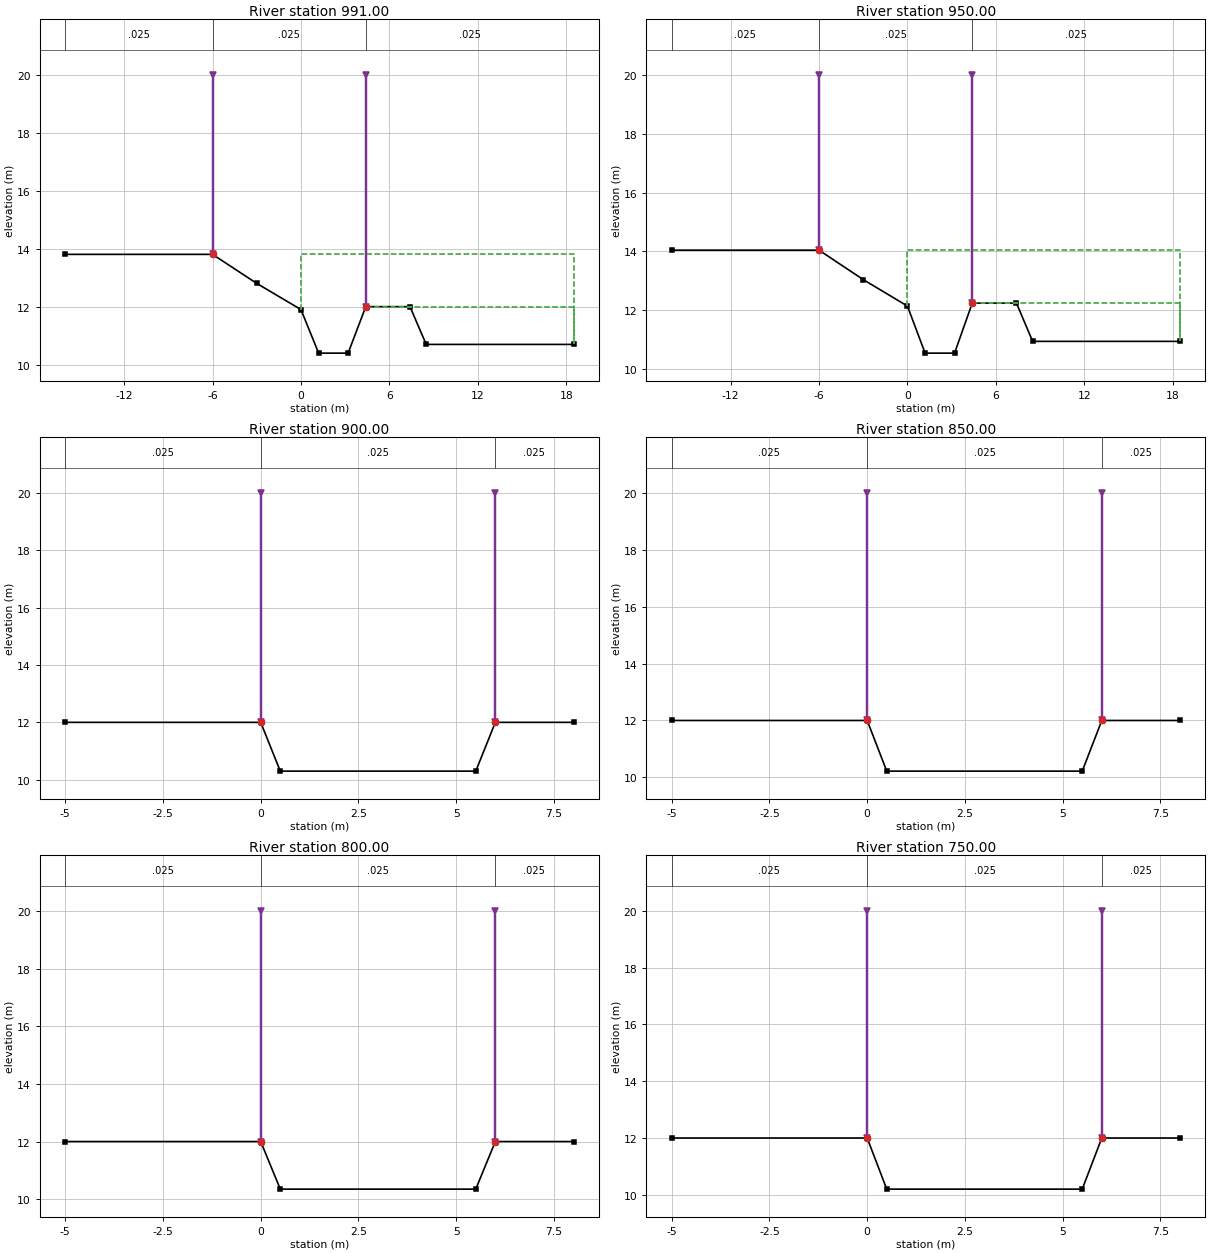
Type RM Length L Ch R = 1 ,991.00  ,41,41,41
BEGIN DESCRIPTION:
19.041
END DESCRIPTION:
#Sta/Elev= 10
     -16   13.82      -6   13.82      -3   12.82       0   11.92     1.2   10.42
     3.2   10.42     4.4   12.02     7.4   12.02     8.5   10.72    18.5   10.72
#Mann= 3 , 0 , 0
     -16    .025       0      -6    .025       0     4.4    .025       0
Levee=-1,-6,20,-1,4.4,20,,
#XS Ineff= 2 , 0
       0      -6   13.82     4.4       0   12.02
Permanent Ineff=
       F       F
Bank Sta=-6,4.4
XS Rating Curve= 0
Exp/Cntr=.3,.1

Type RM Length L Ch R = 1 ,950.00  ,50,50,50
BEGIN DESCRIPTION:
19
END DESCRIPTION:
#Sta/Elev= 10
     -16   14.04      -6   14.04      -3   13.04       0   12.14     1.2   10.54
     3.2   10.54     4.4   12.24     7.4   12.24     8.5   10.94    18.5   10.94
#Mann= 3 , 0 , 0
     -16    .025       0      -6    .025       0     4.4    .025       0
Levee=-1,-6,20,-1,4.4,20,,
#XS Ineff= 2 , 0
       0      -6   14.04     4.4       0   12.24
Permanent Ineff=
       F       F
Bank Sta=-6,4.4
XS Rating Curve= 0
Exp/Cntr=.3,.1

Type RM Length L Ch R = 1 ,900.00  ,50,50,50
BEGIN DESCRIPTION:
18
END DESCRIPTION:
#Sta/Elev= 6
      -5      12       0      12      .5    10.3     5.5    10.3       6      12
       8      12
#Mann= 3 , 0 , 0
      -5    .025       0       0    .025       0       6    .025       0
Levee=-1,0,20,-1,6,20,,
Bank Sta=0,6
XS Rating Curve= 0
Exp/Cntr=.3,.1

Type RM Length L Ch R = 1 ,850.00  ,50,50,50
BEGIN DESCRIPTION:
17
END DESCRIPTION:
#Sta/Elev= 6
      -5      12       0      12      .5   10.22     5.5   10.22       6      12
       8      12
#Mann= 3 , 0 , 0
      -5    .025       0       0    .025       0       6    .025       0
Levee=-1,0,20,-1,6,20,,
Bank Sta=0,6
XS Rating Curve= 0
Exp/Cntr=.3,.1

Type RM Length L Ch R = 1 ,800.00  ,50,50,50
BEGIN DESCRIPTION:
16
END DESCRIPTION:
#Sta/Elev= 6
      -5      12       0      12      .5   10.35     5.5   10.35       6      12
       8      12
#Mann= 3 , 0 , 0
      -5    .025       0       0    .025       0       6    .025       0
Levee=-1,0,20,-1,6,20,,
Bank Sta=0,6
XS Rating Curve= 0
Exp/Cntr=.3,.1

Type RM Length L Ch R = 1 ,750.00  ,50,50,50
BEGIN DESCRIPTION:
15
END DESCRIPTION:
#Sta/Elev= 6
      -5      12       0      12      .5    10.2     5.5    10.2       6      12
       8      12
#Mann= 3 , 0 , 0
      -5    .025       0       0    .025       0       6    .025       0
Levee=-1,0,20,-1,6,20,,
Bank Sta=0,6
XS Rating Curve= 0
Exp/Cntr=.3,.1

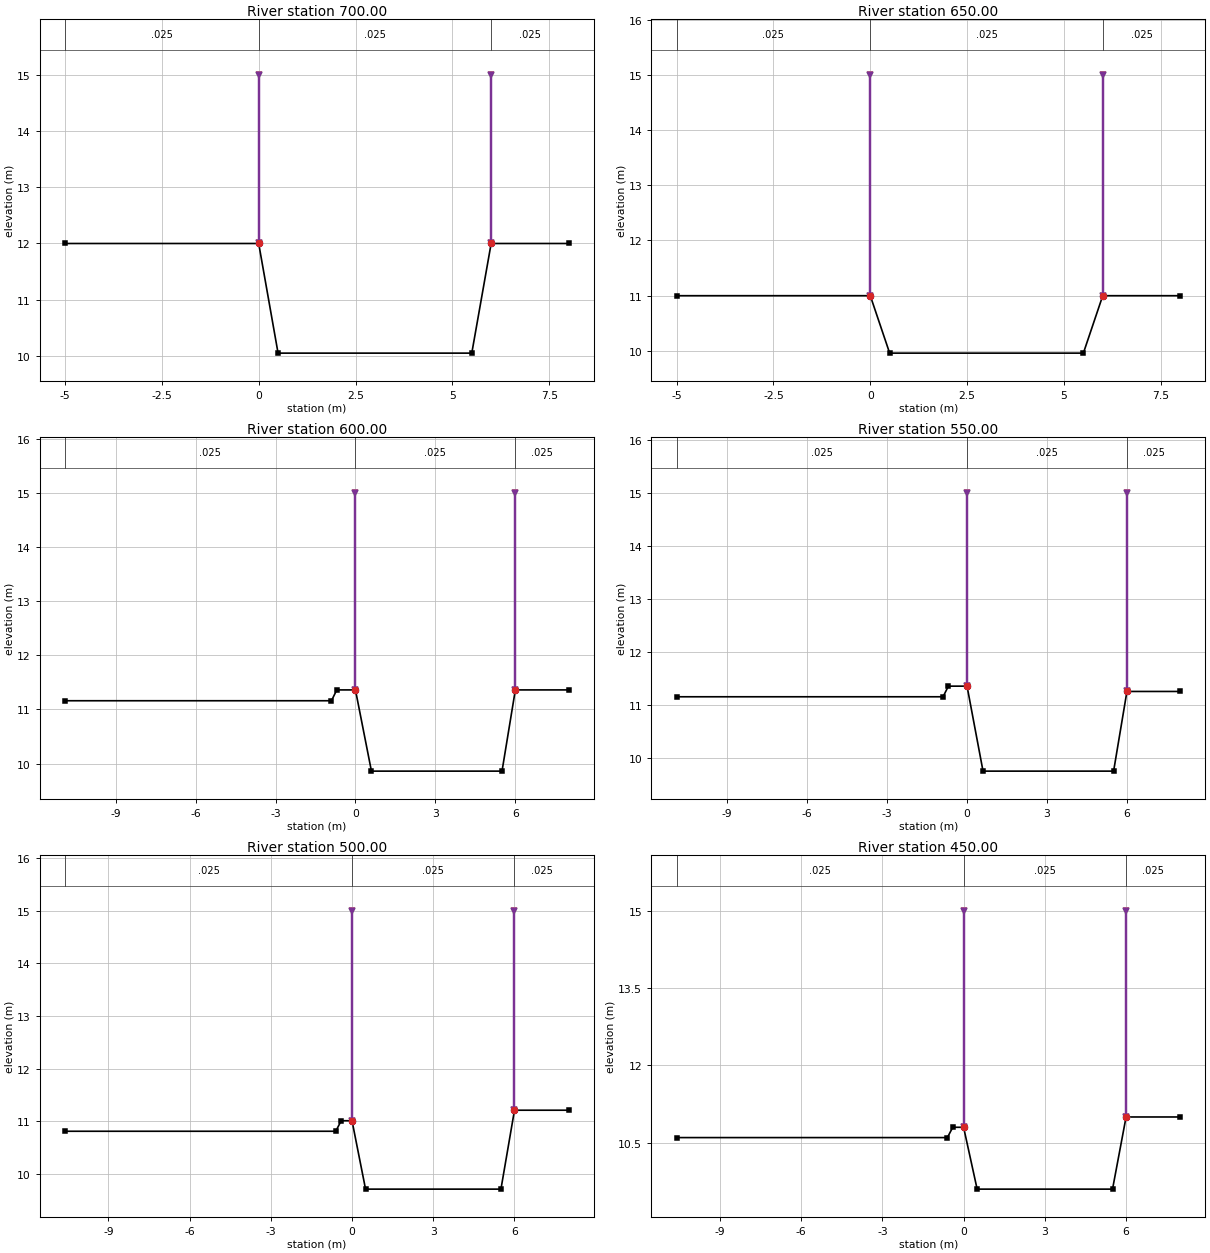
Type RM Length L Ch R = 1 ,700.00  ,50,50,50
BEGIN DESCRIPTION:
14
END DESCRIPTION:
#Sta/Elev= 6
      -5      12       0      12      .5   10.05     5.5   10.05       6      12
       8      12
#Mann= 3 , 0 , 0
      -5    .025       0       0    .025       0       6    .025       0
Levee=-1,0,15,-1,6,15,,
Bank Sta=0,6
XS Rating Curve= 0
Exp/Cntr=.3,.1

Type RM Length L Ch R = 1 ,650.00  ,50,50,50
BEGIN DESCRIPTION:
13
END DESCRIPTION:
#Sta/Elev= 6
      -5      11       0      11      .5    9.96     5.5    9.96       6      11
       8      11
#Mann= 3 , 0 , 0
      -5    .025       0       0    .025       0       6    .025       0
Levee=-1,0,15,-1,6,15,,
Bank Sta=0,6
XS Rating Curve= 0
Exp/Cntr=.3,.1

Type RM Length L Ch R = 1 ,600.00  ,50,50,50
BEGIN DESCRIPTION:
12
END DESCRIPTION:
#Sta/Elev= 8
   -10.9   11.16     -.9   11.16     -.7   11.36       0   11.36      .6    9.86
     5.5    9.86       6   11.36       8   11.36
#Mann= 3 , 0 , 0
   -10.9    .025       0       0    .025       0       6    .025       0
Levee=-1,0,15,-1,6,15,,
Bank Sta=0,6
XS Rating Curve= 0
Exp/Cntr=.3,.1

Type RM Length L Ch R = 1 ,550.00  ,50,50,50
BEGIN DESCRIPTION:
11
END DESCRIPTION:
#Sta/Elev= 8
   -10.9   11.16     -.9   11.16     -.7   11.36       0   11.36      .6    9.76
     5.5    9.76       6   11.26       8   11.26
#Mann= 3 , 0 , 0
   -10.9    .025       0       0    .025       0       6    .025       0
Levee=-1,0,15,-1,6,15,,
Bank Sta=0,6
XS Rating Curve= 0
Exp/Cntr=.3,.1

Type RM Length L Ch R = 1 ,500.00  ,50,50,50
BEGIN DESCRIPTION:
10
END DESCRIPTION:
#Sta/Elev= 8
   -10.6   10.81     -.6   10.81     -.4   11.01       0   11.01      .5    9.71
     5.5    9.71       6   11.21       8   11.21
#Mann= 3 , 0 , 0
   -10.6    .025       0       0    .025       0       6    .025       0
Levee=-1,0,15,-1,6,15,,
Bank Sta=0,6
XS Rating Curve= 0
Exp/Cntr=.3,.1

Type RM Length L Ch R = 1 ,450.00  ,31,31,31
BEGIN DESCRIPTION:
9
END DESCRIPTION:
#Sta/Elev= 8
   -10.6    10.6     -.6    10.6     -.4    10.8       0    10.8      .5     9.6
     5.5     9.6       6      11       8      11
#Mann= 3 , 0 , 0
   -10.6    .025       0       0    .025       0       6    .025       0
Levee=-1,0,15,-1,6,15,,
Bank Sta=0,6
XS Rating Curve= 0
Exp/Cntr=.3,.1

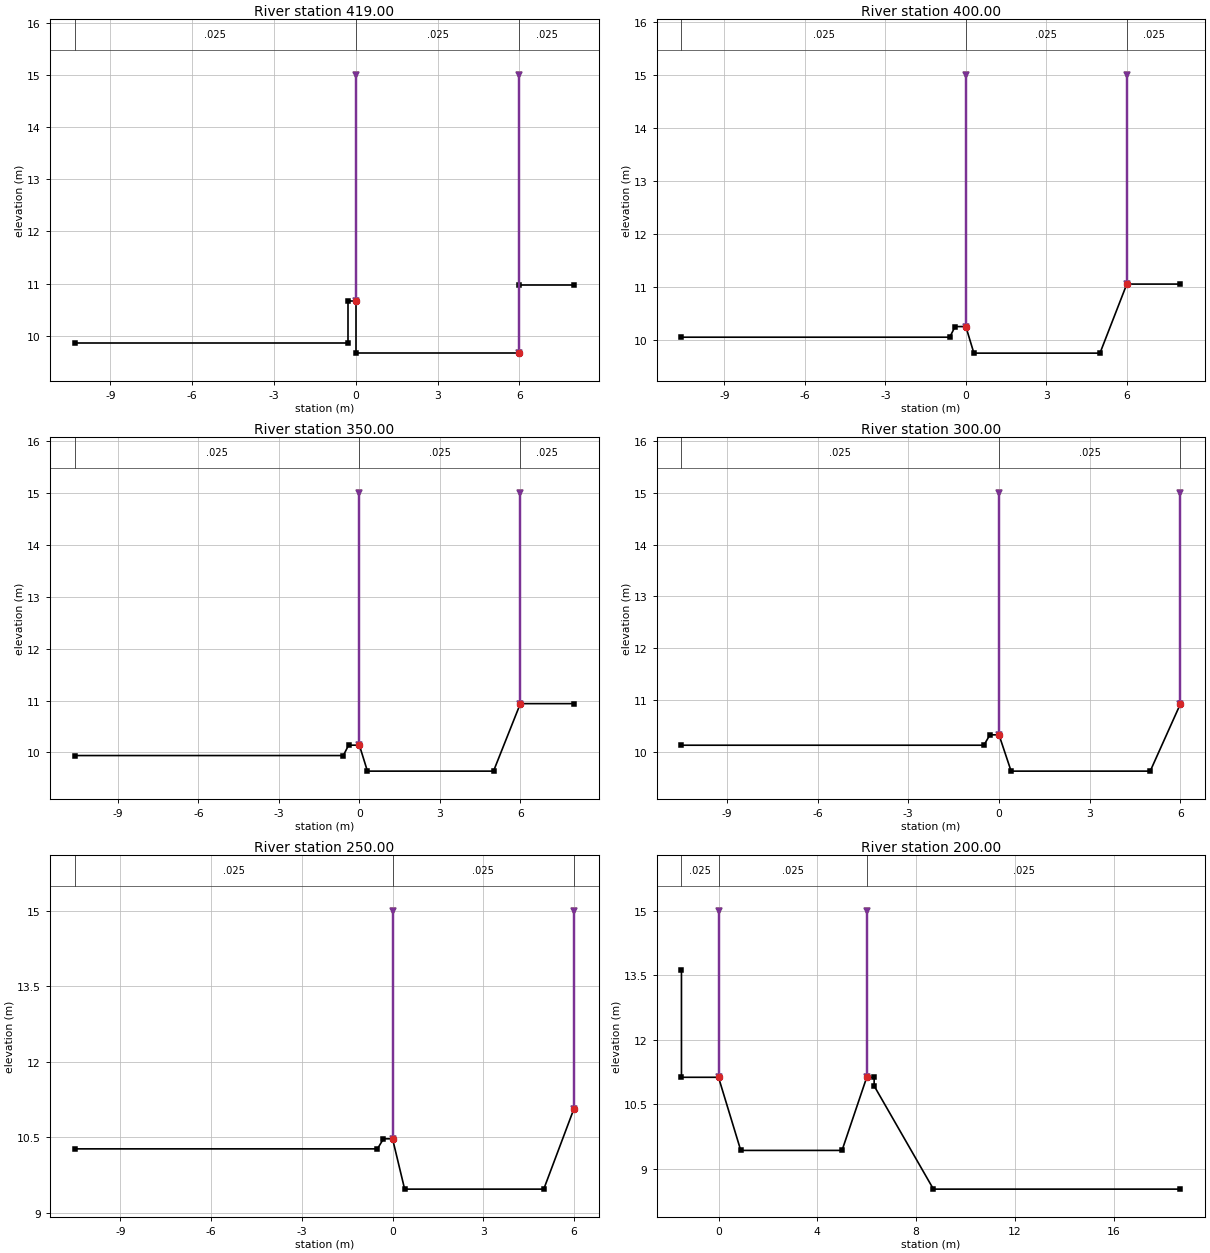
Type RM Length L Ch R = 1 ,419.00  ,19,19,19
BEGIN DESCRIPTION:
8.019
END DESCRIPTION:
#Sta/Elev= 8
   -10.3    9.87     -.3    9.87     -.3   10.67       0   10.67       0    9.67
       6    9.67       6   10.97       8   10.97
#Mann= 3 , 0 , 0
   -10.3    .025       0       0    .025       0       6    .025       0
Levee=-1,0,15,-1,6,15,,
Bank Sta=0,6
XS Rating Curve= 0
Exp/Cntr=.3,.1

Type RM Length L Ch R = 1 ,400.00  ,50,50,50
BEGIN DESCRIPTION:
8
END DESCRIPTION:
#Sta/Elev= 8
   -10.6   10.06     -.6   10.06     -.4   10.26       0   10.26      .3    9.76
       5    9.76       6   11.06       8   11.06
#Mann= 3 , 0 , 0
   -10.6    .025       0       0    .025       0       6    .025       0
Levee=-1,0,15,-1,6,15,,
Bank Sta=0,6
XS Rating Curve= 0
Exp/Cntr=.3,.1

Type RM Length L Ch R = 1 ,350.00  ,50,50,50
BEGIN DESCRIPTION:
7
END DESCRIPTION:
#Sta/Elev= 8
   -10.6    9.94     -.6    9.94     -.4   10.14       0   10.14      .3    9.64
       5    9.64       6   10.94       8   10.94
#Mann= 3 , 0 , 0
   -10.6    .025       0       0    .025       0       6    .025       0
Levee=-1,0,15,-1,6,15,,
Bank Sta=0,6
XS Rating Curve= 0
Exp/Cntr=.3,.1

Type RM Length L Ch R = 1 ,300.00  ,50,50,50
BEGIN DESCRIPTION:
6
END DESCRIPTION:
#Sta/Elev= 7
   -10.5   10.13     -.5   10.13     -.3   10.33       0   10.33      .4    9.63
       5    9.63       6   10.93
#Mann= 3 , 0 , 0
   -10.5    .025       0       0    .025       0       6    .025       0
Levee=-1,0,15,-1,6,15,,
Bank Sta=0,6
XS Rating Curve= 0
Exp/Cntr=.3,.1

Type RM Length L Ch R = 1 ,250.00  ,50,50,50
BEGIN DESCRIPTION:
5
END DESCRIPTION:
#Sta/Elev= 7
   -10.5   10.27     -.5   10.27     -.3   10.47       0   10.47      .4    9.47
       5    9.47       6   11.07
#Mann= 3 , 0 , 0
   -10.5    .025       0       0    .025       0       6    .025       0
Levee=-1,0,15,-1,6,15,,
Bank Sta=0,6
XS Rating Curve= 0
Exp/Cntr=.3,.1

Type RM Length L Ch R = 1 ,200.00  ,23,23,23
BEGIN DESCRIPTION:
4
END DESCRIPTION:
#Sta/Elev= 10
    -1.5   13.63    -1.5   11.13       0   11.13      .9    9.43       5    9.43
       6   11.13     6.3   11.13     6.3   10.93     8.7    8.53    18.7    8.53
#Mann= 3 , 0 , 0
    -1.5    .025       0       0    .025       0       6    .025       0
Levee=-1,0,15,-1,6,15,,
Bank Sta=0,6
XS Rating Curve= 0
Exp/Cntr=.3,.1

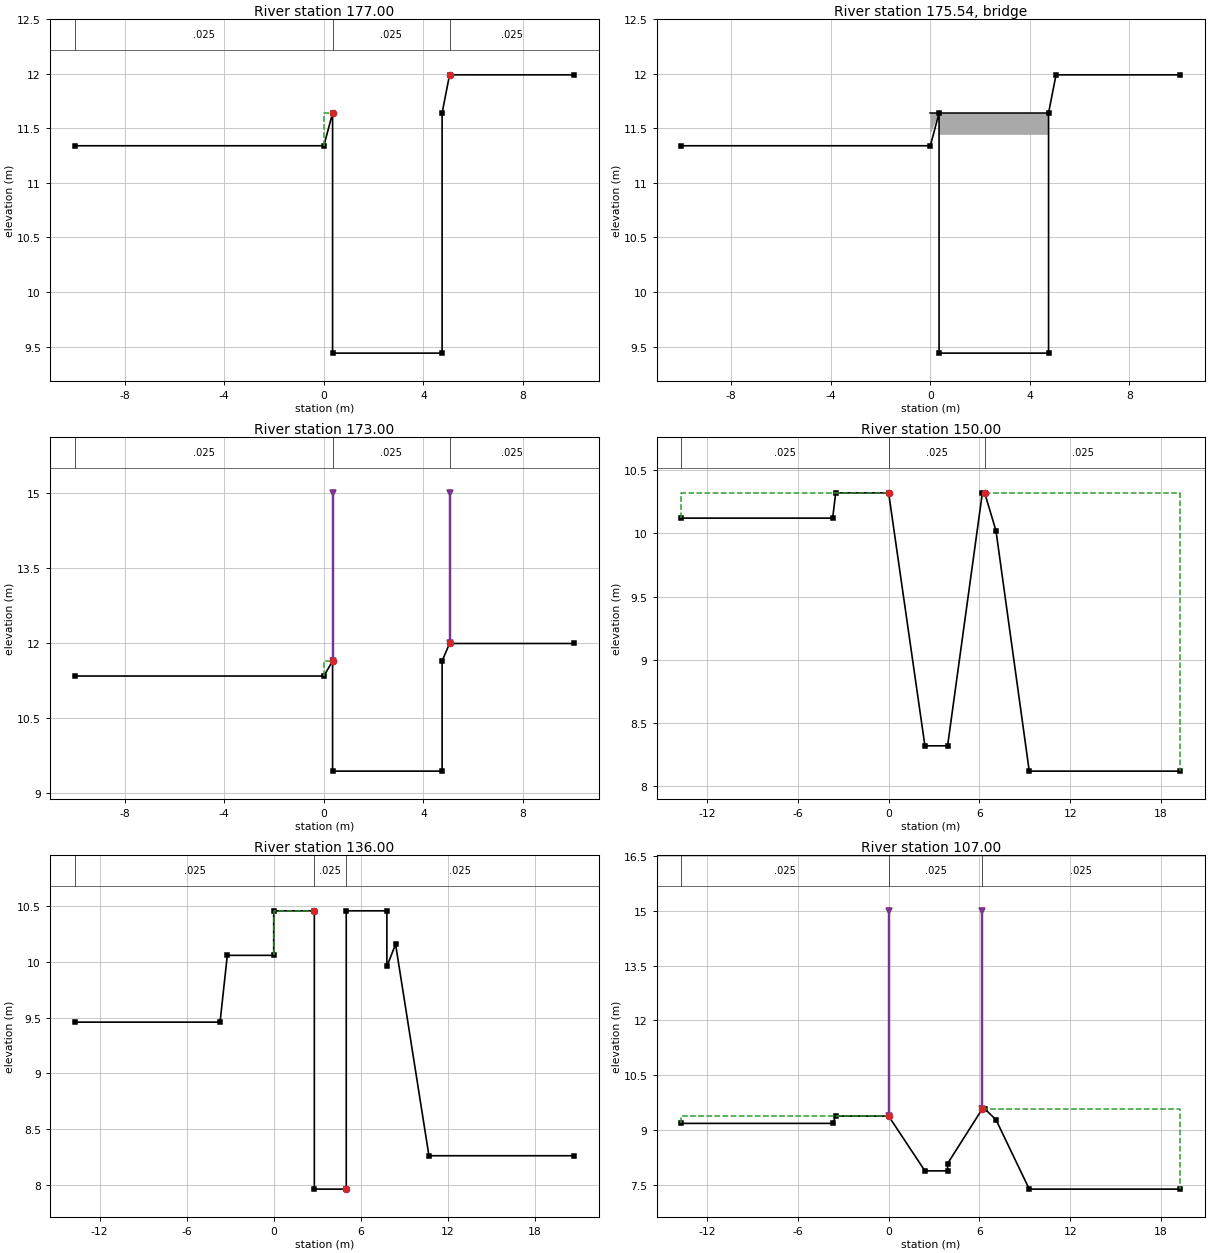
Type RM Length L Ch R = 1 ,177.00  ,4,4,4
BEGIN DESCRIPTION:
3.027
END DESCRIPTION:
#Sta/Elev= 8
     -10   11.34       0   11.34     .35   11.64     .35    9.44    4.75    9.44
    4.75   11.64    5.05   11.99   10.05   11.99
#Mann= 3 , 0 , 0
     -10    .025       0     .35    .025       0    5.05    .025       0
#XS Ineff= 2 , 0
       0     .35   11.64    5.05       0   11.99
Permanent Ineff=
       F       F
Bank Sta=.35,5.05
XS Rating Curve= 0
Exp/Cntr=.3,.1

Type RM Length L Ch R = 3 ,175.54  ,,,
BEGIN DESCRIPTION:
3.025
END DESCRIPTION:
Bridge Culvert--1,0,-1,-1, 0
Deck Dist Width WeirC Skew NumUp NumDn MinLoCord MaxHiCord MaxSubmerge Is_Ogee
.01,2.9,1.44,0, 2, 2, , , .95, 0, 0,0,,
       0    4.75
   11.64   11.64
   11.44   11.44
       0    4.75
   11.64   11.64
   11.44   11.44
BR Coef=-1 , 1 , 0 ,, 0 ,,,.8,-1,1.2,0,
WSPro=,,,, 1 ,,,, 0 ,,,, 0 ,,,,-1 ,-1 ,-1 , 0 , 0 , 0 , 0 , 0
BC Design=,, 0 ,, 0 ,,,,,,

Type RM Length L Ch R = 1 ,173.00  ,23,23,23
BEGIN DESCRIPTION:
3.023
END DESCRIPTION:
#Sta/Elev= 8
     -10   11.34       0   11.34     .35   11.64     .35    9.44    4.75    9.44
    4.75   11.64    5.05   11.99   10.05   11.99
#Mann= 3 , 0 , 0
     -10    .025       0     .35    .025       0    5.05    .025       0
Levee=-1,.35,15,-1,5.05,15,,
#XS Ineff= 2 , 0
       0     .35   11.64    5.05       0   11.99
Permanent Ineff=
       F       F
Bank Sta=.35,5.05
XS Rating Curve= 0
Exp/Cntr=.3,.1

Type RM Length L Ch R = 1 ,150.00  ,14,14,14
BEGIN DESCRIPTION:
3
END DESCRIPTION:
#Sta/Elev= 11
   -13.7   10.12    -3.7   10.12    -3.5   10.32       0   10.32     2.4    8.32
     3.9    8.32     6.2   10.32    6.35   10.32     7.1   10.02     9.3    8.12
    19.3    8.12
#Mann= 3 , 0 , 0
   -13.7    .025       0       0    .025       0    6.35    .025       0
#XS Ineff= 2 , 0
               0   10.32    6.35           10.32
Permanent Ineff=
       F       F
Bank Sta=0,6.35
XS Rating Curve= 0
Exp/Cntr=.3,.1

Type RM Length L Ch R = 1 ,136.00  ,29,29,29
BEGIN DESCRIPTION:
2.036
END DESCRIPTION:
#Sta/Elev= 14
   -13.7    9.46    -3.7    9.46    -3.2   10.06       0   10.06       0   10.46
     2.8   10.46     2.8    7.96       5    7.96       5   10.46     7.8   10.46
     7.8    9.96     8.4   10.16    10.7    8.26    20.7    8.26
#Mann= 3 , 0 , 0
   -13.7    .025       0     2.8    .025       0       5    .025       0
#XS Ineff= 2 , 0
       0     2.8   10.46       5       0    7.96
Permanent Ineff=
       F       F
Bank Sta=2.8,5
XS Rating Curve= 0
Exp/Cntr=.3,.1

Type RM Length L Ch R = 1 ,107.00  ,7,7,7
BEGIN DESCRIPTION:
2.007
END DESCRIPTION:
#Sta/Elev= 12
   -13.7    9.18    -3.7    9.18    -3.5    9.38       0    9.38     2.4    7.88
     3.9    7.88     3.9    8.08     6.2    9.58    6.35    9.58     7.1    9.28
     9.3    7.38    19.3    7.38
#Mann= 3 , 0 , 0
   -13.7    .025       0       0    .025       0     6.2    .025       0
Levee=-1,0,15,-1,6.2,15,,
#XS Ineff= 2 , 0
               0    9.38     6.2            9.58
Permanent Ineff=
       F       F
Bank Sta=0,6.2
XS Rating Curve= 0
Exp/Cntr=.3,.1

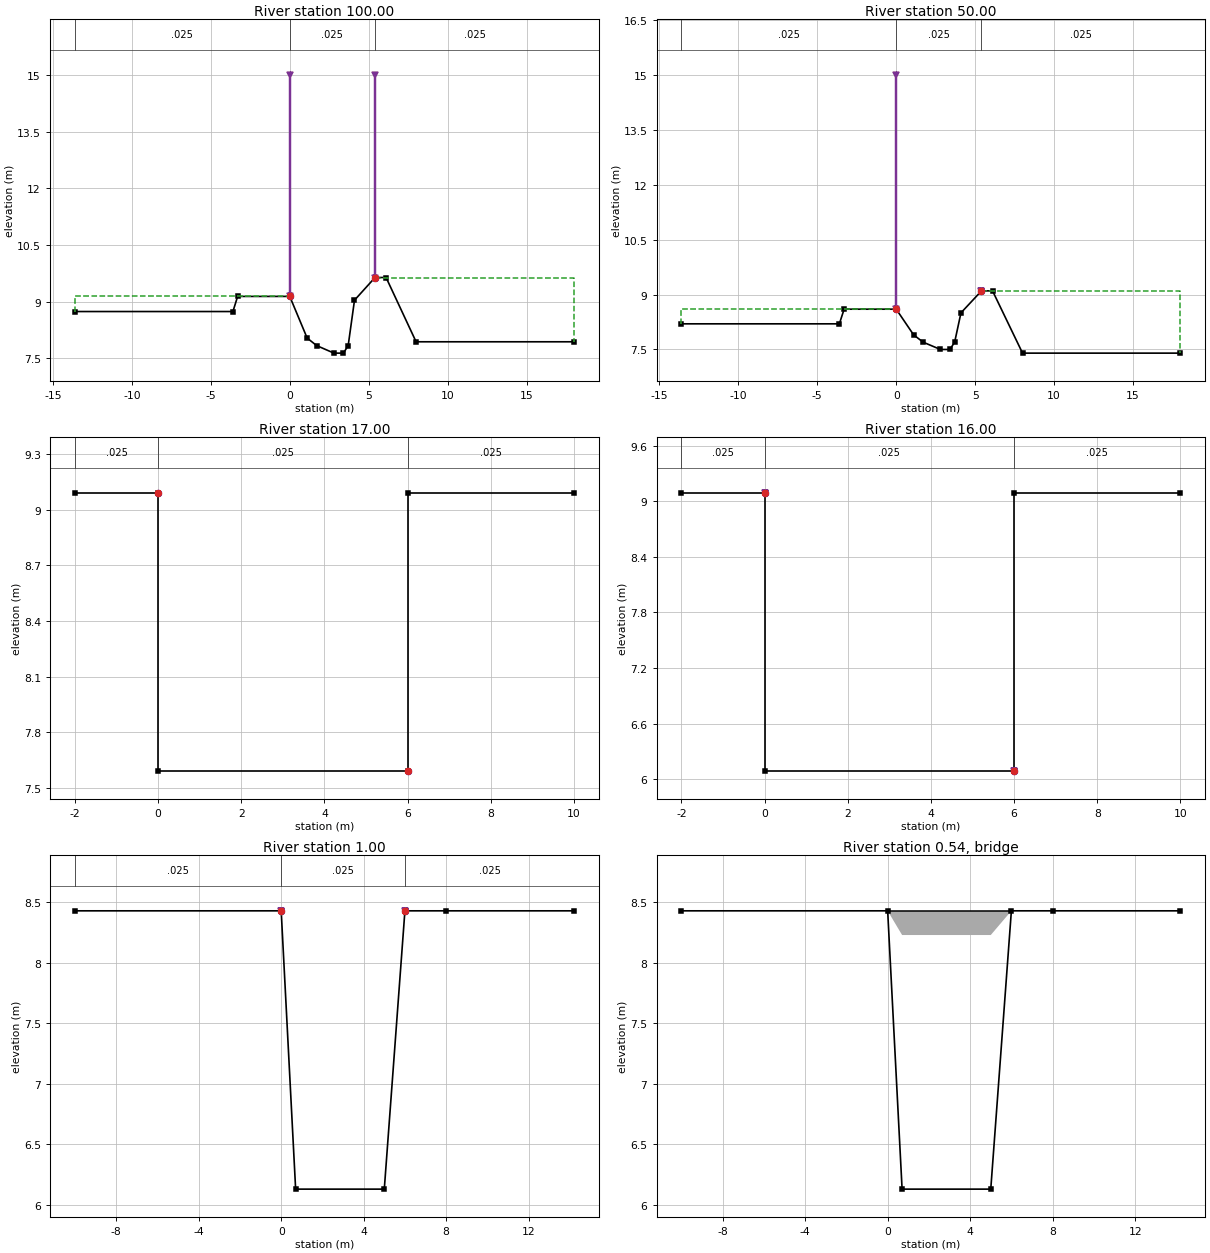
Type RM Length L Ch R = 1 ,100.00  ,50,50,50
BEGIN DESCRIPTION:
2
END DESCRIPTION:
#Sta/Elev= 14
   -13.6    8.74    -3.6    8.74    -3.3    9.14       0    9.14     1.1    8.04
     1.7    7.84     2.8    7.64     3.4    7.64     3.7    7.84     4.1    9.04
     5.4    9.64     6.1    9.64       8    7.94      18    7.94
#Mann= 3 , 0 , 0
   -13.6    .025       0       0    .025       0     5.4    .025       0
Levee=-1,0,15,-1,5.4,15,,
#XS Ineff= 2 , 0
               0    9.14     5.4            9.64
Permanent Ineff=
       F       F
Bank Sta=0,5.4
XS Rating Curve= 0
Exp/Cntr=.3,.1

Type RM Length L Ch R = 1 ,50.00   ,33,33,33
BEGIN DESCRIPTION:
1
END DESCRIPTION:
#Sta/Elev= 14
   -13.6     8.2    -3.6     8.2    -3.3     8.6       0     8.6     1.1     7.9
     1.7     7.7     2.8     7.5     3.4     7.5     3.7     7.7     4.1     8.5
     5.4     9.1     6.1     9.1       8     7.4      18     7.4
#Mann= 3 , 0 , 0
   -13.6    .025       0       0    .025       0     5.4    .025       0
Levee=-1,0,15,-1,5.4,9.1,,
#XS Ineff= 2 , 0
               0     8.6     5.4             9.1
Permanent Ineff=
       F       F
Bank Sta=0,5.4
XS Rating Curve= 0
Exp/Cntr=.3,.1

Type RM Length L Ch R = 1 ,17.00   ,1,1,1
BEGIN DESCRIPTION:
0.017
END DESCRIPTION:
#Sta/Elev= 6
      -2    9.09       0    9.09       0    7.59       6    7.59       6    9.09
      10    9.09
#Mann= 3 , 0 , 0
      -2    .025       0       0    .025       0       6    .025       0
Bank Sta=0,6
XS Rating Curve= 0
Exp/Cntr=.3,.1

Type RM Length L Ch R = 1 ,16.00   ,15,15,15
BEGIN DESCRIPTION:
0.016
END DESCRIPTION:
#Sta/Elev= 6
      -2    9.09       0    9.09       0    6.09       6    6.09       6    9.09
      10    9.09
#Mann= 3 , 0 , 0
      -2    .025       0       0    .025       0       6    .025       0
Levee=-1,0,9.09,-1,6,6.09,,
Bank Sta=0,6
XS Rating Curve= 0
Exp/Cntr=.3,.1

Type RM Length L Ch R = 1 ,1.00    ,1,1,1
BEGIN DESCRIPTION:
0.001
END DESCRIPTION:
#Sta/Elev= 7
     -10    8.43       0    8.43      .7    6.13       5    6.13       6    8.43
       8    8.43    14.2    8.43
#Mann= 3 , 0 , 0
     -10    .025       0       0    .025       0       6    .025       0
Levee=-1,0,8.43,-1,6,8.43,,
Bank Sta=0,6
XS Rating Curve= 0
Exp/Cntr=.3,.1

Type RM Length L Ch R = 3 ,0.54    ,,,
BEGIN DESCRIPTION:
0.0005
END DESCRIPTION:
Bridge Culvert--1,0,-1,-1, 0
Deck Dist Width WeirC Skew NumUp NumDn MinLoCord MaxHiCord MaxSubmerge Is_Ogee
.01,.9,1.44,0, 2, 2, , , .95, 0, 0,0,,
       0       6
    8.43    8.43
    8.23    8.23
       0       6
    8.43    8.43
    8.23    8.23
BR Coef=-1 , 1 , 0 ,, 0 ,,,.8,-1,1.2,0,
WSPro=,,,, 1 ,,,, 0 ,,,, 0 ,,,,-1 ,-1 ,-1 , 0 , 0 , 0 , 0 , 0
BC Design=,, 0 ,, 0 ,,,,,,

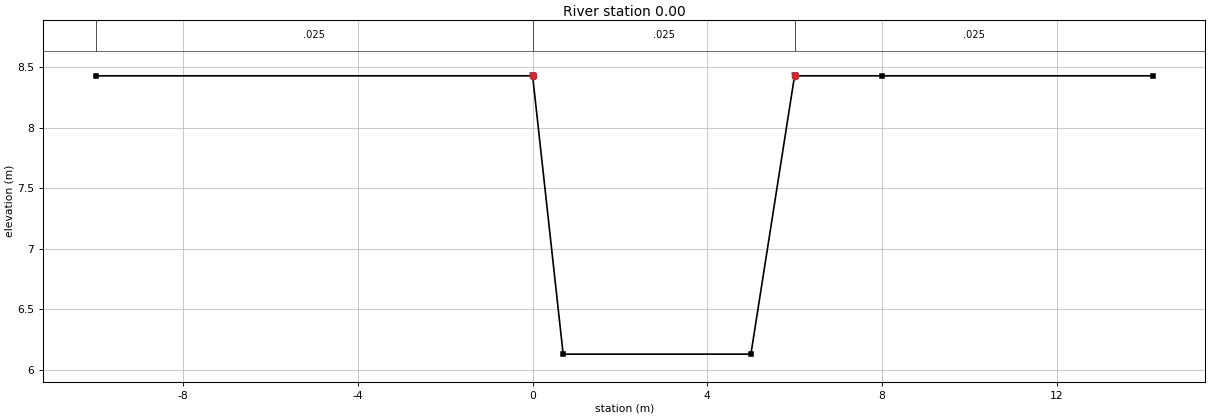
Type RM Length L Ch R = 1 ,0.00    ,0,0,0
BEGIN DESCRIPTION:
0
END DESCRIPTION:
#Sta/Elev= 7
     -10    8.43       0    8.43      .7    6.13       5    6.13       6    8.43
       8    8.43    14.2    8.43
#Mann= 3 , 0 , 0
     -10    .025       0       0    .025       0       6    .025       0
Levee=-1,0,8.43,-1,6,8.43,,
Bank Sta=0,6
XS Rating Curve= 0
Exp/Cntr=.3,.1

Chan Stop Cuts=-1