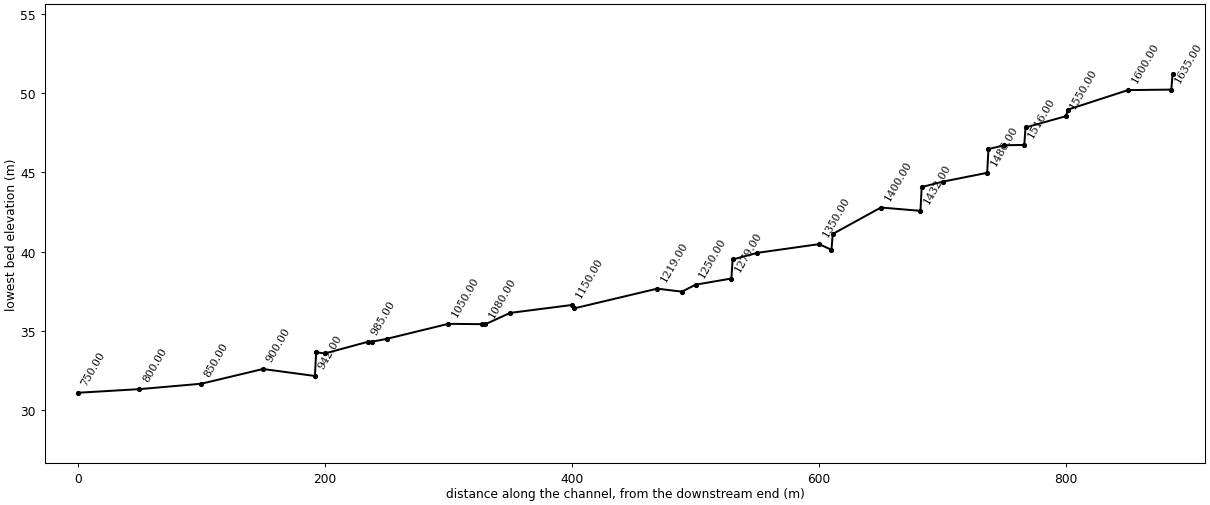
--- hgc.prj (project) ---

Proj Title=hagoo-ch
Current Plan=p01
Default Exp/Contr=.3,.1
SI Units
Geom File=g01
Flow File=f01
Plan File=p01
Y Axis Title=Elevation
X Axis Title(PF)=Main Channel Distance
X Axis Title(XS)=Station
BEGIN DESCRIPTION:
           BACK WATER COMPUTATION
      APPLICATION OF HEC-2 BY Samju Construction Engineering
      ÇÏ±¸Ãµ(¿ËÃµÀ¾): 30,50,80,100,150³âºóµµ °³¼öÀü
END DESCRIPTION:
DSS Export Rating Curves= 0
DSS Export Rating Curve Sorted= 0
DSS Export Volume Flow Curves= 0
DXF OffsetX= 0
DXF OffsetY= 0
DXF ScaleX= 1
DXF ScaleY= 10

--- hgc.p01 (plan) ---

Plan Title=Imported Plan 01
Version=Version 3.0.1  Mar 2001
Short Identifier=Imported Pla
Geom File=g01
Flow File=f01
Subcritical Flow
K Sum by GR= 0
Std Step Tol= 0.003
Critical Tol= 0.003
Num of Std Step Trials= 20
Max Error Tol= 0.1
Flow Tol Ratio= 0.001
Split Flow NTrial= 30
Split Flow Tol= 0.02
Split Flow Ratio= 0.02
Log Output Level= 0
Friction Slope Method= 1
Unsteady Friction Slope Method= 2
Parabolic Critical Depth
Global Vel Dist= 0 , 0 , 0
Global Log Level= 0
CheckData=True
Encroach Param=-1 ,0,0, 0
Computation Interval=1HOUR
Output Interval=1HOUR
Run HTab= 0
Run UNet= 0
Run PostProcess= 0
UNET Theta= 1
UNET ZTol= 0.02
UNET ZSATol= 0.1
UNET MxIter= 20
UNET MaxInSteps= 20
UNET DtIC= 0
UNET DtMin= 0
UNET MaxCRTS= 20
UNET WFStab= 2
UNET SFStab= 1
UNET WFX= 1
UNET SFX= 1
UNET Convert EG Bridges=-1
UNET Use Existing IB Tables=-1
Instantaneous Interval=1HOUR
Write IC File= 0
Write Velocity= 0
Write Detailed= 0

--- hgc.f01 (steady flow) ---

Flow Title=Imported Flow 01
Version=Version 3.0.1  Mar 2001
Number of Profiles= 5
Profile Names=10yr,20yr,30yr,50yr,80yr
River Rch & RM=RIVER-1,Reach-1         ,32.036
    6.98    7.68     8.1    8.62    9.09
River Rch & RM=RIVER-1,Reach-1         ,12
    8.57    9.45    9.96   10.61   11.21
River Rch & RM=hagu,hagu            ,1636.00
    6.98    7.68     8.1    8.62    9.09
River Rch & RM=hagu,hagu            ,600.00
    8.57    9.45    9.96   10.61   11.21
Boundary for River Rch & Prof#=hagu,hagu            , 1
Up Type= 0
Dn Type= 3
Dn Slope=.01818
Boundary for River Rch & Prof#=hagu,hagu            , 2
Up Type= 0
Dn Type= 3
Dn Slope=.01818
Boundary for River Rch & Prof#=hagu,hagu            , 3
Up Type= 0
Dn Type= 3
Dn Slope=.01818
Boundary for River Rch & Prof#=hagu,hagu            , 4
Up Type= 0
Dn Type= 3
Dn Slope=.01818
Boundary for River Rch & Prof#=hagu,hagu            , 5
Up Type= 0
Dn Type= 3
Dn Slope=.01818
DSS Import GetInterval= 0
DSS Import GetPeak= 0
DSS Import FillOption= 0

--- hgc.g01 (geometry) ---

Geom Title=Imported Geom 01
Version=Version 3.0.1  Mar 2001

River Reach=hagu            ,hagu
Reach XY= 2
              .5             .95              .5             .05

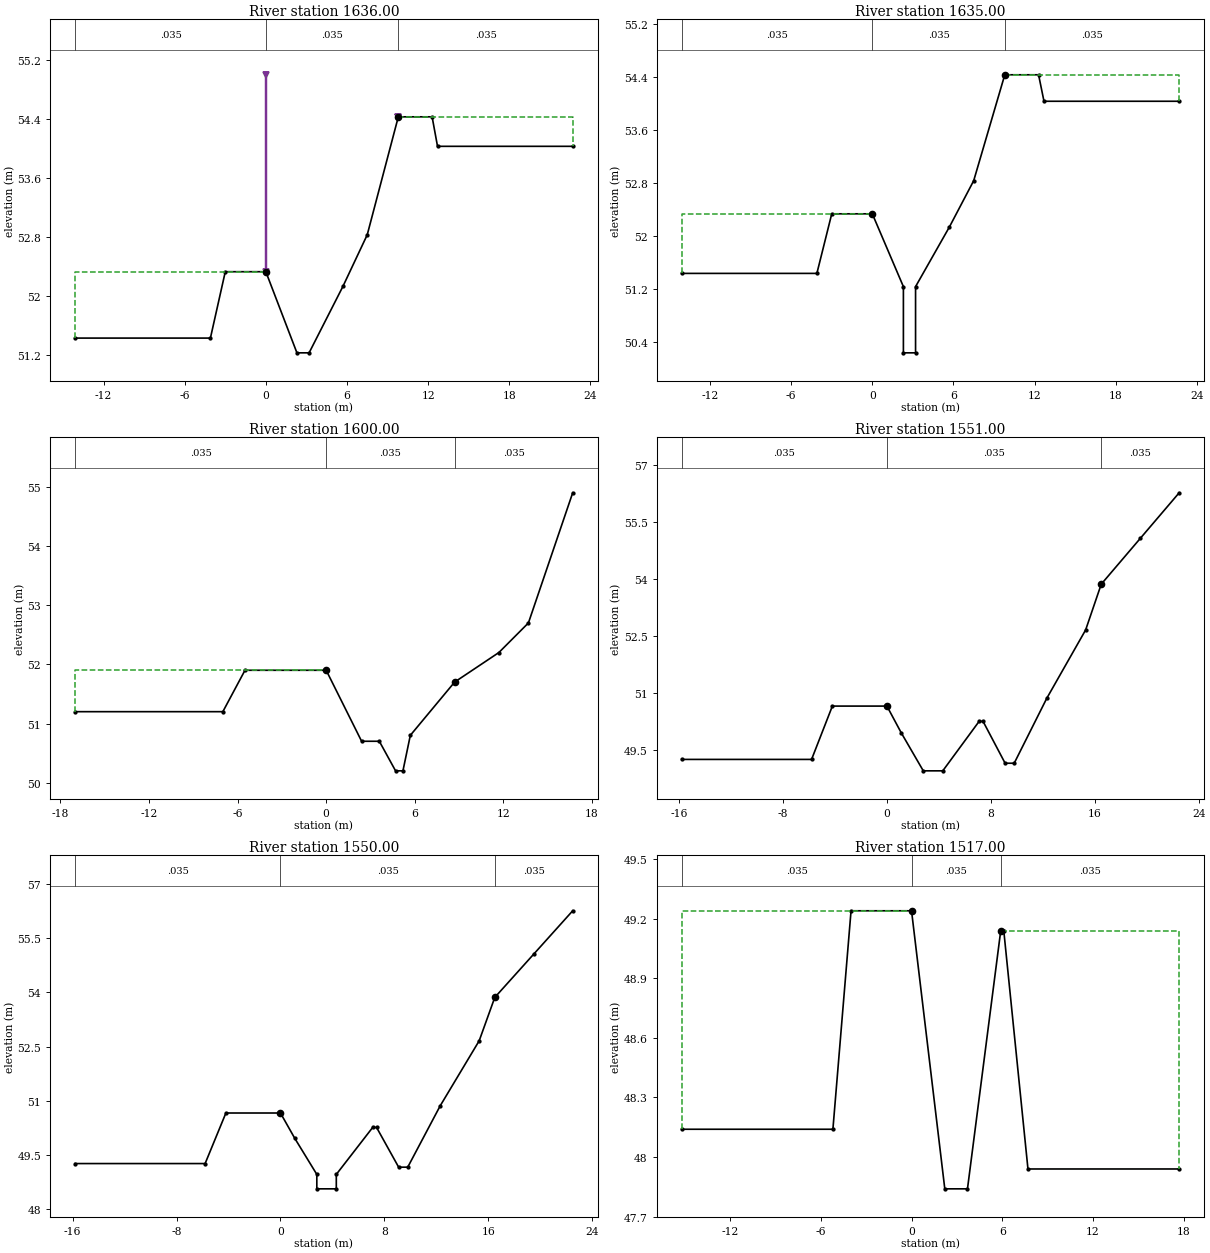
Type RM Length L Ch R = 1 ,1636.00 ,1,1,1
BEGIN DESCRIPTION:
32.036
END DESCRIPTION:
#Sta/Elev= 12
   -14.1   51.43    -4.1   51.43      -3   52.33       0   52.33     2.3   51.23
     3.2   51.23     5.7   52.13     7.5   52.83     9.8   54.43    12.3   54.43
    12.7   54.03    22.7   54.03
#Mann= 3 , 0 , 0
   -14.1    .035       0       0    .035       0     9.8    .035       0
Levee=-1,0,55,-1,9.8,54.43,,
#XS Ineff= 2 , 0
               0   52.33     9.8           54.43
Permanent Ineff=
       F       F
Bank Sta=0,9.8
XS Rating Curve= 0
Exp/Cntr=.3,.1

Type RM Length L Ch R = 1 ,1635.00 ,35,35,35
BEGIN DESCRIPTION:
32.035
END DESCRIPTION:
#Sta/Elev= 14
   -14.1   51.43    -4.1   51.43      -3   52.33       0   52.33     2.3   51.23
     2.3   50.23     3.2   50.23     3.2   51.23     5.7   52.13     7.5   52.83
     9.8   54.43    12.3   54.43    12.7   54.03    22.7   54.03
#Mann= 3 , 0 , 0
   -14.1    .035       0       0    .035       0     9.8    .035       0
#XS Ineff= 2 , 0
               0   52.33     9.8           54.43
Permanent Ineff=
       F       F
Bank Sta=0,9.8
XS Rating Curve= 0
Exp/Cntr=.3,.1

Type RM Length L Ch R = 1 ,1600.00 ,49,49,49
BEGIN DESCRIPTION:
32
END DESCRIPTION:
#Sta/Elev= 13
     -17    51.2      -7    51.2    -5.5    51.9       0    51.9     2.4    50.7
     3.6    50.7     4.7    50.2     5.2    50.2     5.7    50.8     8.7    51.7
    11.7    52.2    13.7    52.7    16.7    54.9
#Mann= 3 , 0 , 0
     -17    .035       0       0    .035       0     8.7    .035       0
#XS Ineff= 2 , 0
               0    51.9     8.7            51.7
Permanent Ineff=
       F       F
Bank Sta=0,8.7
XS Rating Curve= 0
Exp/Cntr=.3,.1

Type RM Length L Ch R = 1 ,1551.00 ,1,1,1
BEGIN DESCRIPTION:
31.001
END DESCRIPTION:
#Sta/Elev= 16
   -15.8   49.26    -5.8   49.26    -4.2   50.66       0   50.66     1.1   49.96
     2.8   48.96     4.3   48.96     7.1   50.26     7.4   50.26     9.1   49.16
     9.8   49.16    12.3   50.86    15.3   52.66    16.5   53.86    19.5   55.06
    22.5   56.26
#Mann= 3 , 0 , 0
   -15.8    .035       0       0    .035       0    16.5    .035       0
#XS Ineff= 2 , 0
       0       0   50.66    16.5       0   53.86
Permanent Ineff=
       F       F
Bank Sta=0,16.5
XS Rating Curve= 0
Exp/Cntr=.3,.1

Type RM Length L Ch R = 1 ,1550.00 ,33,33,33
BEGIN DESCRIPTION:
31
END DESCRIPTION:
#Sta/Elev= 18
   -15.8   49.26    -5.8   49.26    -4.2   50.66       0   50.66     1.1   49.96
     2.8   48.96     2.8   48.56     4.3   48.56     4.3   48.96     7.1   50.26
     7.4   50.26     9.1   49.16     9.8   49.16    12.3   50.86    15.3   52.66
    16.5   53.86    19.5   55.06    22.5   56.26
#Mann= 3 , 0 , 0
   -15.8    .035       0       0    .035       0    16.5    .035       0
#XS Ineff= 2 , 0
       0       0   50.66    16.5       0   53.86
Permanent Ineff=
       F       F
Bank Sta=0,16.5
XS Rating Curve= 0
Exp/Cntr=.3,.1

Type RM Length L Ch R = 1 ,1517.00 ,1,1,1
BEGIN DESCRIPTION:
30.017
END DESCRIPTION:
#Sta/Elev= 10
   -15.2   48.14    -5.2   48.14      -4   49.24       0   49.24     2.2   47.84
     3.7   47.84     5.9   49.14     6.1   49.14     7.7   47.94    17.7   47.94
#Mann= 3 , 0 , 0
   -15.2    .035       0       0    .035       0     5.9    .035       0
#XS Ineff= 2 , 0
               0   49.24     5.9           49.14
Permanent Ineff=
       F       F
Bank Sta=0,5.9
XS Rating Curve= 0
Exp/Cntr=.3,.1

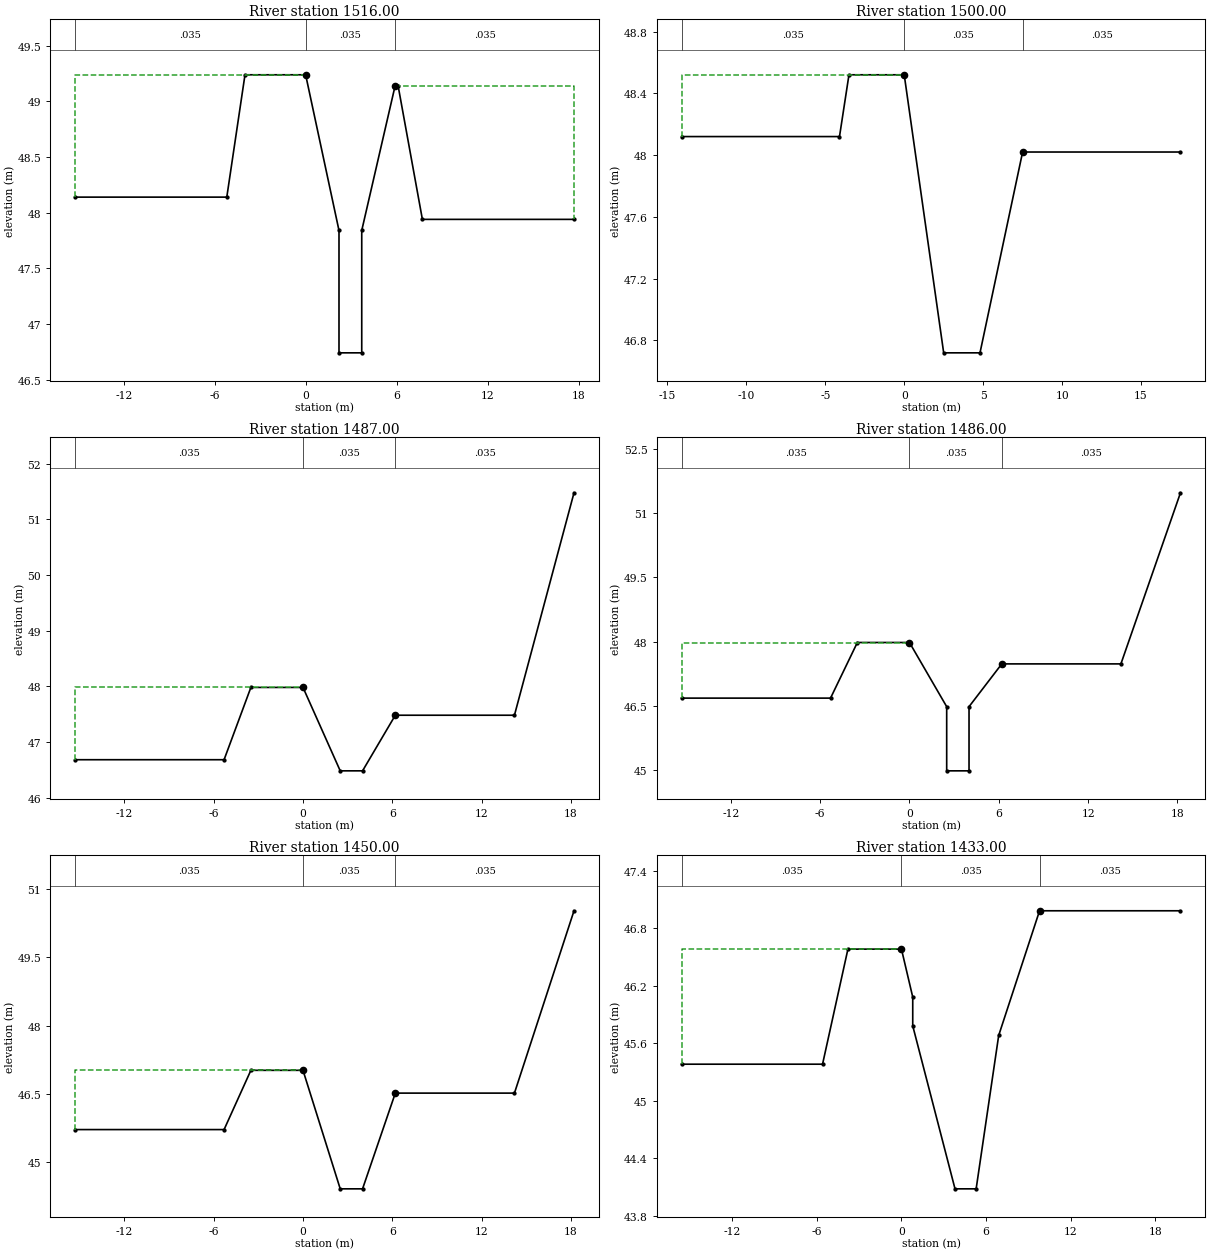
Type RM Length L Ch R = 1 ,1516.00 ,16,16,16
BEGIN DESCRIPTION:
30.016
END DESCRIPTION:
#Sta/Elev= 12
   -15.2   48.14    -5.2   48.14      -4   49.24       0   49.24     2.2   47.84
     2.2   46.74     3.7   46.74     3.7   47.84     5.9   49.14     6.1   49.14
     7.7   47.94    17.7   47.94
#Mann= 3 , 0 , 0
   -15.2    .035       0       0    .035       0     5.9    .035       0
#XS Ineff= 2 , 0
               0   49.24     5.9           49.14
Permanent Ineff=
       F       F
Bank Sta=0,5.9
XS Rating Curve= 0
Exp/Cntr=.3,.1

Type RM Length L Ch R = 1 ,1500.00 ,13,13,13
BEGIN DESCRIPTION:
30
END DESCRIPTION:
#Sta/Elev= 8
   -14.1   48.12    -4.1   48.12    -3.5   48.52       0   48.52     2.5   46.72
     4.8   46.72     7.5   48.02    17.5   48.02
#Mann= 3 , 0 , 0
   -14.1    .035       0       0    .035       0     7.5    .035       0
#XS Ineff= 2 , 0
               0   48.52     7.5           48.02
Permanent Ineff=
       F       F
Bank Sta=0,7.5
XS Rating Curve= 0
Exp/Cntr=.3,.1

Type RM Length L Ch R = 1 ,1487.00 ,1,1,1
BEGIN DESCRIPTION:
29.037
END DESCRIPTION:
#Sta/Elev= 9
   -15.3   46.68    -5.3   46.68    -3.5   47.98       0   47.98     2.5   46.48
       4   46.48     6.2   47.48    14.2   47.48    18.2   51.48
#Mann= 3 , 0 , 0
   -15.3    .035       0       0    .035       0     6.2    .035       0
#XS Ineff= 2 , 0
               0   47.98     6.2           47.48
Permanent Ineff=
       F       F
Bank Sta=0,6.2
XS Rating Curve= 0
Exp/Cntr=.3,.1

Type RM Length L Ch R = 1 ,1486.00 ,36,36,36
BEGIN DESCRIPTION:
29.036
END DESCRIPTION:
#Sta/Elev= 11
   -15.3   46.68    -5.3   46.68    -3.5   47.98       0   47.98     2.5   46.48
     2.5   44.98       4   44.98       4   46.48     6.2   47.48    14.2   47.48
    18.2   51.48
#Mann= 3 , 0 , 0
   -15.3    .035       0       0    .035       0     6.2    .035       0
#XS Ineff= 2 , 0
               0   47.98     6.2           47.48
Permanent Ineff=
       F       F
Bank Sta=0,6.2
XS Rating Curve= 0
Exp/Cntr=.3,.1

Type RM Length L Ch R = 1 ,1450.00 ,17,17,17
BEGIN DESCRIPTION:
29
END DESCRIPTION:
#Sta/Elev= 9
   -15.3   45.72    -5.3   45.72    -3.5   47.02       0   47.02     2.5   44.42
       4   44.42     6.2   46.52    14.2   46.52    18.2   50.52
#Mann= 3 , 0 , 0
   -15.3    .035       0       0    .035       0     6.2    .035       0
#XS Ineff= 2 , 0
               0   47.02     6.2           46.52
Permanent Ineff=
       F       F
Bank Sta=0,6.2
XS Rating Curve= 0
Exp/Cntr=.3,.1

Type RM Length L Ch R = 1 ,1433.00 ,1,1,1
BEGIN DESCRIPTION:
28.033
END DESCRIPTION:
#Sta/Elev= 11
   -15.6   45.38    -5.6   45.38    -3.8   46.58       0   46.58      .8   46.08
      .8   45.78     3.8   44.08     5.3   44.08     6.9   45.68     9.8   46.98
    19.8   46.98
#Mann= 3 , 0 , 0
   -15.6    .035       0       0    .035       0     9.8    .035       0
#XS Ineff= 2 , 0
               0   46.58     9.8           46.98
Permanent Ineff=
       F       F
Bank Sta=0,9.8
XS Rating Curve= 0
Exp/Cntr=.3,.1

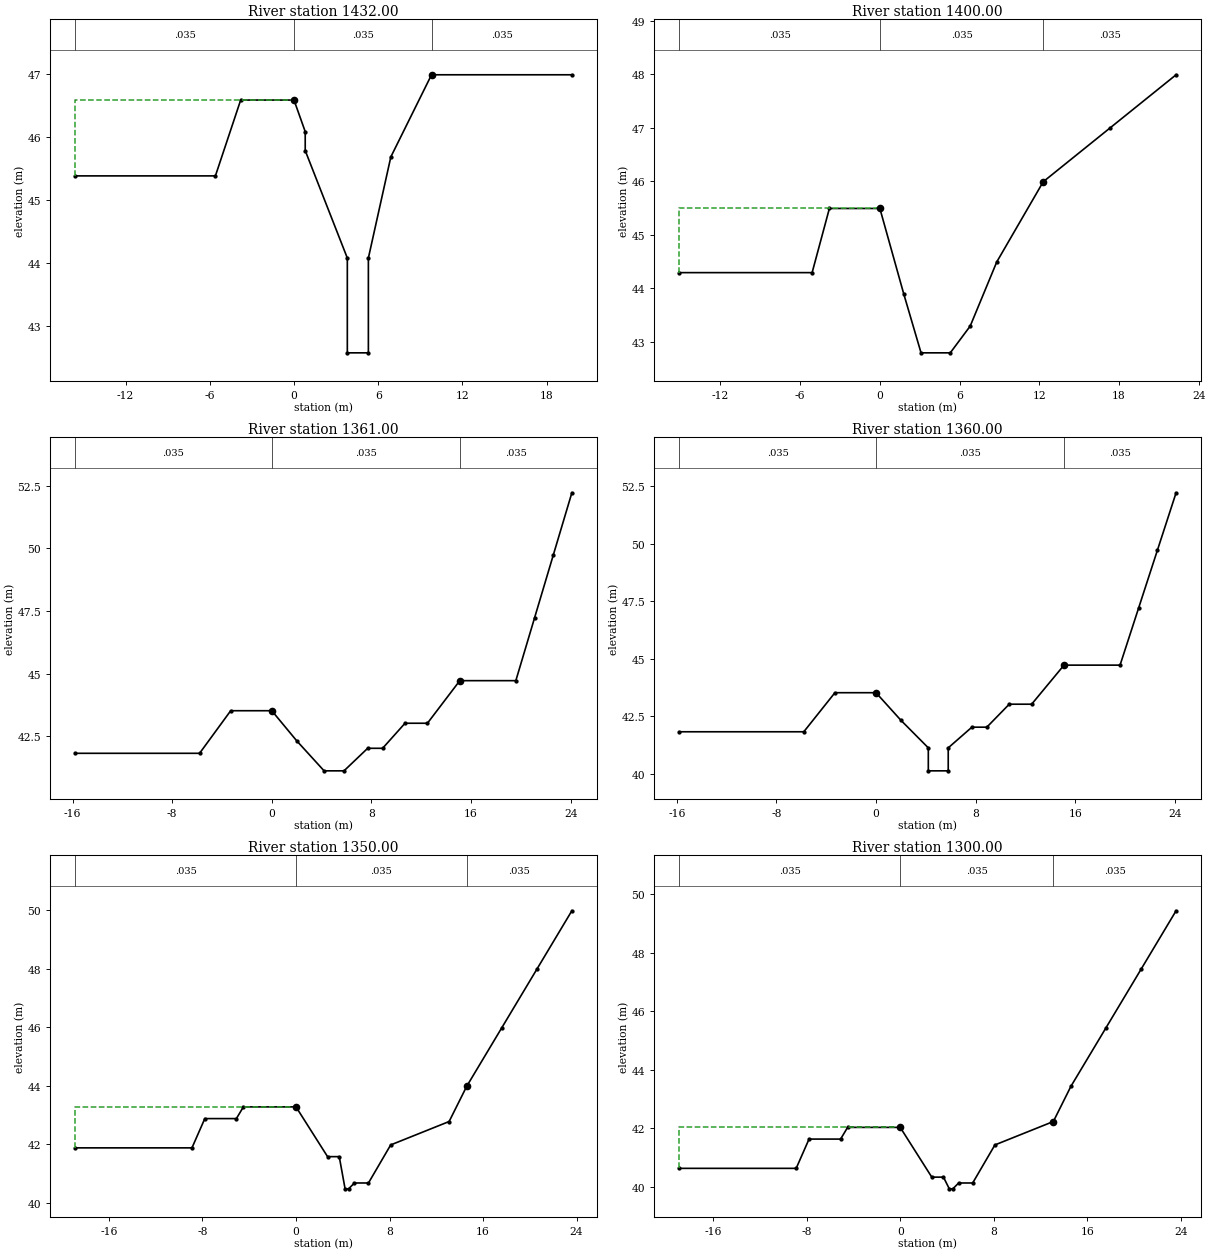
Type RM Length L Ch R = 1 ,1432.00 ,32,32,32
BEGIN DESCRIPTION:
28.032
END DESCRIPTION:
#Sta/Elev= 13
   -15.6   45.38    -5.6   45.38    -3.8   46.58       0   46.58      .8   46.08
      .8   45.78     3.8   44.08     3.8   42.58     5.3   42.58     5.3   44.08
     6.9   45.68     9.8   46.98    19.8   46.98
#Mann= 3 , 0 , 0
   -15.6    .035       0       0    .035       0     9.8    .035       0
#XS Ineff= 2 , 0
               0   46.58     9.8           46.98
Permanent Ineff=
       F       F
Bank Sta=0,9.8
XS Rating Curve= 0
Exp/Cntr=.3,.1

Type RM Length L Ch R = 1 ,1400.00 ,39,39,39
BEGIN DESCRIPTION:
28
END DESCRIPTION:
#Sta/Elev= 12
   -15.1   44.29    -5.1   44.29    -3.8   45.49       0   45.49     1.8   43.89
     3.1   42.79     5.3   42.79     6.8   43.29     8.8   44.49    12.3   45.99
    17.3   46.99    22.3   47.99
#Mann= 3 , 0 , 0
   -15.1    .035       0       0    .035       0    12.3    .035       0
#XS Ineff= 2 , 0
               0   45.49    12.3           45.99
Permanent Ineff=
       F       F
Bank Sta=0,12.3
XS Rating Curve= 0
Exp/Cntr=.3,.1

Type RM Length L Ch R = 1 ,1361.00 ,1,1,1
BEGIN DESCRIPTION:
27.011
END DESCRIPTION:
#Sta/Elev= 16
   -15.8   41.82    -5.8   41.82    -3.3   43.52       0   43.52       2   42.32
     4.2   41.12     5.8   41.12     7.7   42.02     8.9   42.02    10.7   43.02
    12.5   43.02    15.1   44.72    19.6   44.72    21.1   47.22    22.6   49.72
    24.1   52.22
#Mann= 3 , 0 , 0
   -15.8    .035       0       0    .035       0    15.1    .035       0
#XS Ineff= 2 , 0
       0       0   43.52    15.1       0   44.72
Permanent Ineff=
       F       F
Bank Sta=0,15.1
XS Rating Curve= 0
Exp/Cntr=.3,.1

Type RM Length L Ch R = 1 ,1360.00 ,10,10,10
BEGIN DESCRIPTION:
27.01
END DESCRIPTION:
#Sta/Elev= 18
   -15.8   41.82    -5.8   41.82    -3.3   43.52       0   43.52       2   42.32
     4.2   41.12     4.2   40.12     5.8   40.12     5.8   41.12     7.7   42.02
     8.9   42.02    10.7   43.02    12.5   43.02    15.1   44.72    19.6   44.72
    21.1   47.22    22.6   49.72    24.1   52.22
#Mann= 3 , 0 , 0
   -15.8    .035       0       0    .035       0    15.1    .035       0
#XS Ineff= 2 , 0
       0       0   43.52    15.1       0   44.72
Permanent Ineff=
       F       F
Bank Sta=0,15.1
XS Rating Curve= 0
Exp/Cntr=.3,.1

Type RM Length L Ch R = 1 ,1350.00 ,50,50,50
BEGIN DESCRIPTION:
27
END DESCRIPTION:
#Sta/Elev= 18
   -18.9   41.88    -8.9   41.88    -7.8   42.88    -5.1   42.88    -4.5   43.28
       0   43.28     2.7   41.58     3.7   41.58     4.2   40.48     4.5   40.48
       5   40.68     6.2   40.68     8.1   41.98    13.1   42.78    14.6   43.98
    17.6   45.98    20.6   47.98    23.6   49.98
#Mann= 3 , 0 , 0
   -18.9    .035       0       0    .035       0    14.6    .035       0
#XS Ineff= 2 , 0
               0   43.28    14.6           43.98
Permanent Ineff=
       F       F
Bank Sta=0,14.6
XS Rating Curve= 0
Exp/Cntr=.3,.1

Type RM Length L Ch R = 1 ,1300.00 ,20,20,20
BEGIN DESCRIPTION:
26
END DESCRIPTION:
#Sta/Elev= 18
   -18.9   40.63    -8.9   40.63    -7.8   41.63    -5.1   41.63    -4.5   42.03
       0   42.03     2.7   40.33     3.7   40.33     4.2   39.93     4.5   39.93
       5   40.13     6.2   40.13     8.1   41.43    13.1   42.23    14.6   43.43
    17.6   45.43    20.6   47.43    23.6   49.43
#Mann= 3 , 0 , 0
   -18.9    .035       0       0    .035       0    13.1    .035       0
#XS Ineff= 2 , 0
               0   42.03    13.1           42.23
Permanent Ineff=
       F       F
Bank Sta=0,13.1
XS Rating Curve= 0
Exp/Cntr=.3,.1

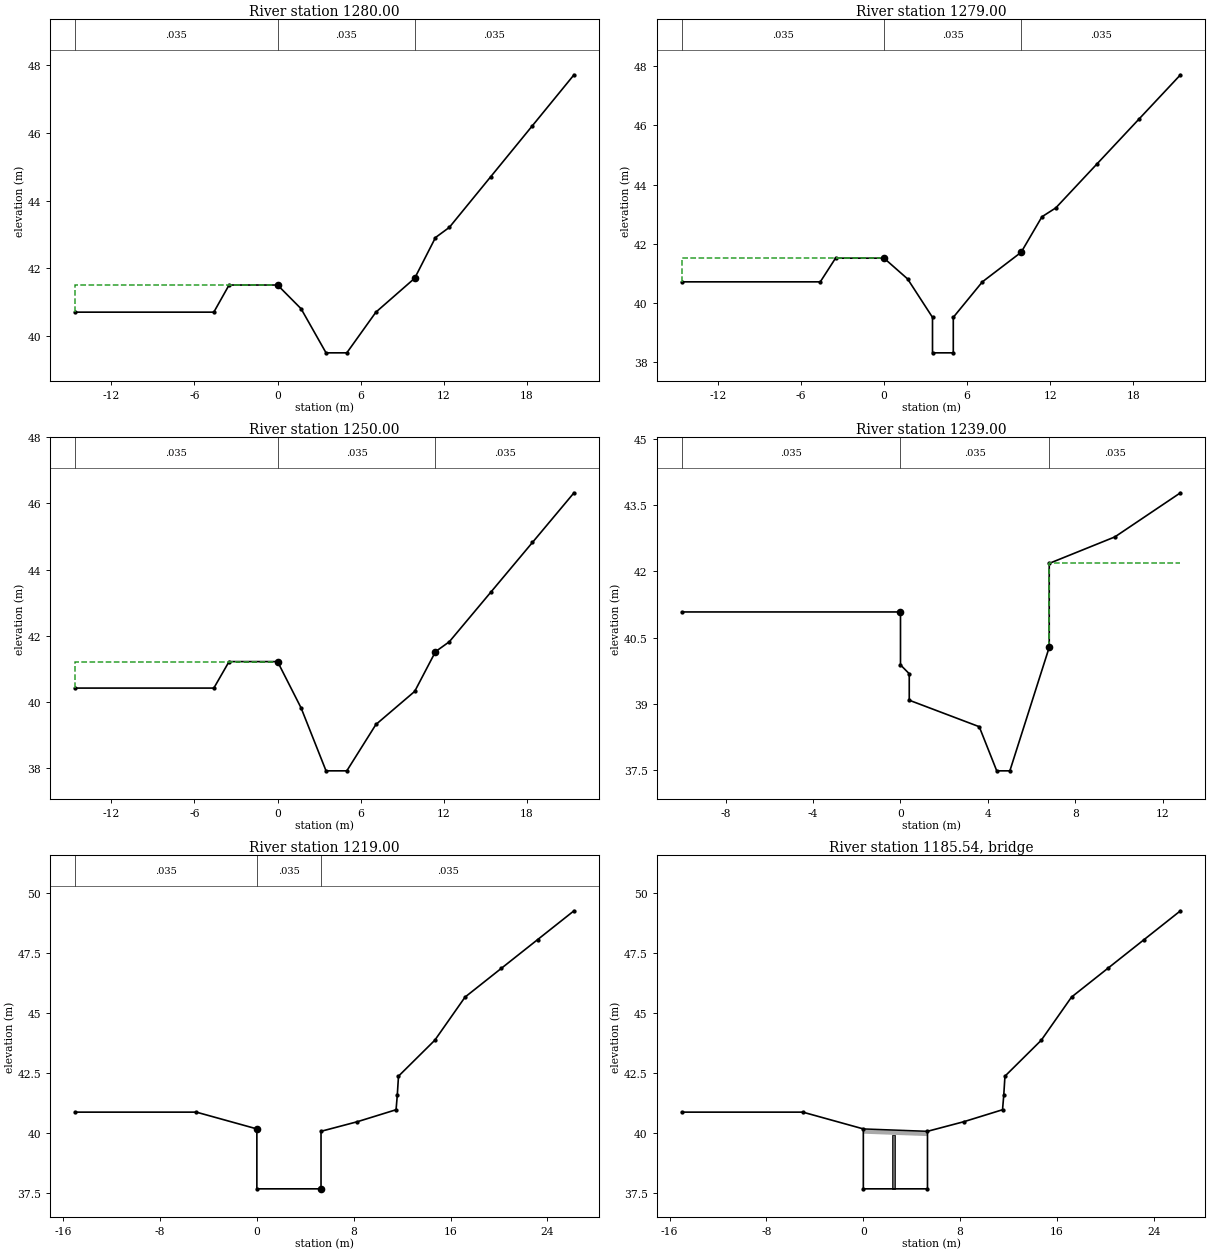
Type RM Length L Ch R = 1 ,1280.00 ,1,1,1
BEGIN DESCRIPTION:
25.03
END DESCRIPTION:
#Sta/Elev= 14
   -14.6   40.71    -4.6   40.71    -3.5   41.51       0   41.51     1.7   40.81
     3.5   39.51       5   39.51     7.1   40.71     9.9   41.71    11.4   42.91
    12.4   43.21    15.4   44.71    18.4   46.21    21.4   47.71
#Mann= 3 , 0 , 0
   -14.6    .035       0       0    .035       0     9.9    .035       0
#XS Ineff= 2 , 0
               0   41.51     9.9           41.71
Permanent Ineff=
       F       F
Bank Sta=0,9.9
XS Rating Curve= 0
Exp/Cntr=.3,.1

Type RM Length L Ch R = 1 ,1279.00 ,29,29,29
BEGIN DESCRIPTION:
25.029
END DESCRIPTION:
#Sta/Elev= 16
   -14.6   40.71    -4.6   40.71    -3.5   41.51       0   41.51     1.7   40.81
     3.5   39.51     3.5   38.31       5   38.31       5   39.51     7.1   40.71
     9.9   41.71    11.4   42.91    12.4   43.21    15.4   44.71    18.4   46.21
    21.4   47.71
#Mann= 3 , 0 , 0
   -14.6    .035       0       0    .035       0     9.9    .035       0
#XS Ineff= 2 , 0
               0   41.51     9.9           41.71
Permanent Ineff=
       F       F
Bank Sta=0,9.9
XS Rating Curve= 0
Exp/Cntr=.3,.1

Type RM Length L Ch R = 1 ,1250.00 ,11,11,11
BEGIN DESCRIPTION:
25
END DESCRIPTION:
#Sta/Elev= 14
   -14.6   40.42    -4.6   40.42    -3.5   41.22       0   41.22     1.7   39.82
     3.5   37.92       5   37.92     7.1   39.32     9.9   40.32    11.4   41.52
    12.4   41.82    15.4   43.32    18.4   44.82    21.4   46.32
#Mann= 3 , 0 , 0
   -14.6    .035       0       0    .035       0    11.4    .035       0
#XS Ineff= 2 , 0
               0   41.22    11.4           41.52
Permanent Ineff=
       F       F
Bank Sta=0,11.4
XS Rating Curve= 0
Exp/Cntr=.3,.1

Type RM Length L Ch R = 1 ,1239.00 ,20,20,20
BEGIN DESCRIPTION:
24.039
END DESCRIPTION:
#Sta/Elev= 12
     -10   41.08       0   41.08       0   39.88      .4   39.68      .4   39.08
     3.6   38.48     4.4   37.48       5   37.48     6.8   40.28     6.8   42.18
     9.8   42.78    12.8   43.78
#Mann= 3 , 0 , 0
     -10    .035       0       0    .035       0     6.8    .035       0
#XS Ineff= 2 , 0
               0   41.08     6.8           42.18
Permanent Ineff=
       F       F
Bank Sta=0,6.8
XS Rating Curve= 0
Exp/Cntr=.3,.1

Type RM Length L Ch R = 1 ,1219.00 ,67,67,67
BEGIN DESCRIPTION:
24.019
END DESCRIPTION:
#Sta/Elev= 15
     -15   40.87      -5   40.87       0   40.17       0   37.67     5.3   37.67
     5.3   40.07     8.3   40.47    11.5   40.97    11.6   41.57    11.7   42.37
    14.7   43.87    17.2   45.67    20.2   46.87    23.2   48.07    26.2   49.27
#Mann= 3 , 0 , 0
     -15    .035       0       0    .035       0     5.3    .035       0
Bank Sta=0,5.3
XS Rating Curve= 0
Exp/Cntr=.3,.1

Type RM Length L Ch R = 3 ,1185.54 ,,,
BEGIN DESCRIPTION:
23.0355
END DESCRIPTION:
Bridge Culvert--1,0,-1,-1, 0
Deck Dist Width WeirC Skew NumUp NumDn MinLoCord MaxHiCord MaxSubmerge Is_Ogee
.01,66.9,1.44,0, 2, 2, , , .95, 0, 0,0,,
       0     5.3
   40.17   40.07
   39.97   39.87
       0     5.3
   38.73   38.63
   38.53   38.43
Pier Skew, UpSta & Num, DnSta & Num=  ,2.5, 2 ,2.5, 2 , 0 , 0 , 0 ,,
      .3      .3
   37.67   40.17
      .3      .3
   36.43   38.73
BR Coef=-1 , 1 , 0 ,, 0 ,,,.8,-1,1.2,0,
WSPro=,,,, 1 ,,,, 0 ,,,, 0 ,,,,-1 ,-1 ,-1 , 0 , 0 , 0 , 0 , 0
BC Design=,, 0 ,, 0 ,,,,,,

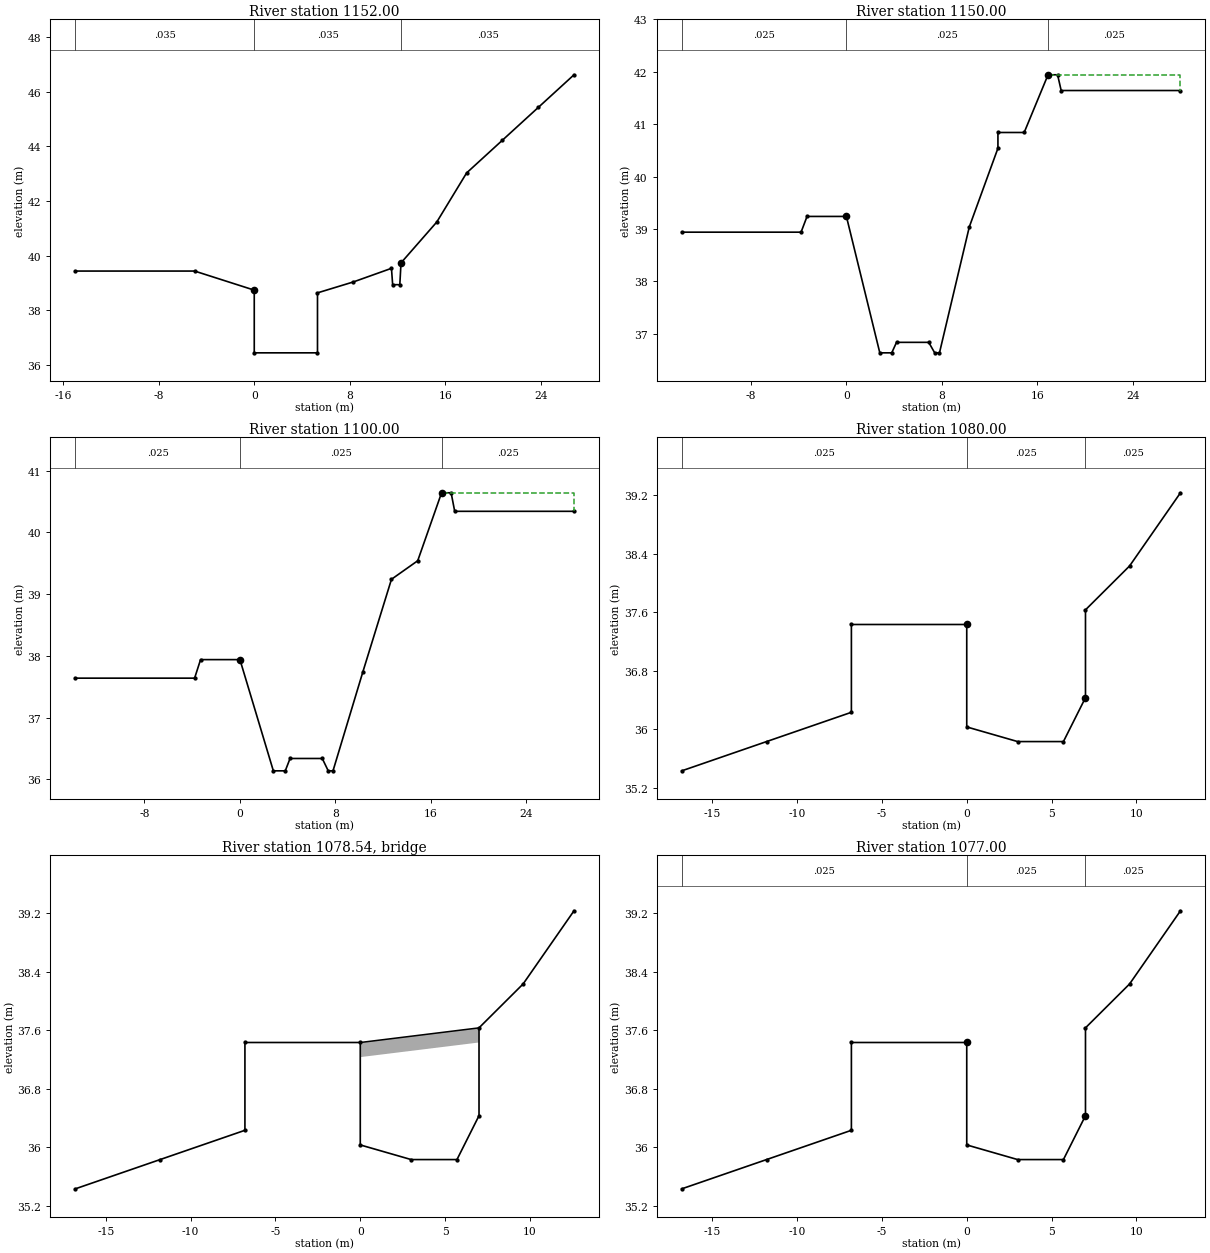
Type RM Length L Ch R = 1 ,1152.00 ,2,2,2
BEGIN DESCRIPTION:
23.002
END DESCRIPTION:
#Sta/Elev= 16
     -15   39.43      -5   39.43       0   38.73       0   36.43     5.3   36.43
     5.3   38.63     8.3   39.03    11.5   39.53    11.6   38.93    12.2   38.93
    12.3   39.73    15.3   41.23    17.8   43.03    20.8   44.23    23.8   45.43
    26.8   46.63
#Mann= 3 , 0 , 0
     -15    .035       0       0    .035       0    12.3    .035       0
#XS Ineff= 2 , 0
       0       0   38.73    12.3       0   39.73
Permanent Ineff=
       F       F
Bank Sta=0,12.3
XS Rating Curve= 0
Exp/Cntr=.3,.1

Type RM Length L Ch R = 1 ,1150.00 ,50,50,50
BEGIN DESCRIPTION:
23
END DESCRIPTION:
#Sta/Elev= 18
   -13.8   38.94    -3.8   38.94    -3.3   39.24       0   39.24     2.8   36.64
     3.8   36.64     4.2   36.84     6.9   36.84     7.4   36.64     7.8   36.64
    10.3   39.04    12.7   40.54    12.7   40.84    14.9   40.84    16.9   41.94
    17.7   41.94      18   41.64      28   41.64
#Mann= 3 , 0 , 0
   -13.8    .025       0       0    .025       0    16.9    .025       0
#XS Ineff= 2 , 0
       0       0   39.24    16.9       0   41.94
Permanent Ineff=
       F       F
Bank Sta=0,16.9
XS Rating Curve= 0
Exp/Cntr=.3,.1

Type RM Length L Ch R = 1 ,1100.00 ,20,20,20
BEGIN DESCRIPTION:
22
END DESCRIPTION:
#Sta/Elev= 17
   -13.8   37.64    -3.8   37.64    -3.3   37.94       0   37.94     2.8   36.14
     3.8   36.14     4.2   36.34     6.9   36.34     7.4   36.14     7.8   36.14
    10.3   37.74    12.7   39.24    14.9   39.54    16.9   40.64    17.7   40.64
      18   40.34      28   40.34
#Mann= 3 , 0 , 0
   -13.8    .025       0       0    .025       0    16.9    .025       0
#XS Ineff= 2 , 0
       0       0   37.94    16.9       0   40.64
Permanent Ineff=
       F       F
Bank Sta=0,16.9
XS Rating Curve= 0
Exp/Cntr=.3,.1

Type RM Length L Ch R = 1 ,1080.00 ,3,3,3
BEGIN DESCRIPTION:
21.030
END DESCRIPTION:
#Sta/Elev= 12
   -16.8   35.43   -11.8   35.83    -6.8   36.23    -6.8   37.43       0   37.43
       0   36.03       3   35.83     5.7   35.83       7   36.43       7   37.63
     9.6   38.23    12.6   39.23
#Mann= 3 , 0 , 0
   -16.8    .025       0       0    .025       0       7    .025       0
Bank Sta=0,7
XS Rating Curve= 0
Exp/Cntr=.3,.1

Type RM Length L Ch R = 3 ,1078.54 ,,,
BEGIN DESCRIPTION:
21.0285
END DESCRIPTION:
Bridge Culvert--1,0,-1,-1, 0
Deck Dist Width WeirC Skew NumUp NumDn MinLoCord MaxHiCord MaxSubmerge Is_Ogee
.01,2.9,1.44,0, 2, 2, , , .95, 0, 0,0,,
       0       7
   37.43   37.63
   37.23   37.43
       0       7
   37.43   37.63
   37.23   37.43
BR Coef=-1 , 1 , 0 ,, 0 ,,,.8,-1,1.2,0,
WSPro=,,,, 1 ,,,, 0 ,,,, 0 ,,,,-1 ,-1 ,-1 , 0 , 0 , 0 , 0 , 0
BC Design=,, 0 ,, 0 ,,,,,,

Type RM Length L Ch R = 1 ,1077.00 ,27,27,27
BEGIN DESCRIPTION:
21.027
END DESCRIPTION:
#Sta/Elev= 12
   -16.8   35.43   -11.8   35.83    -6.8   36.23    -6.8   37.43       0   37.43
       0   36.03       3   35.83     5.7   35.83       7   36.43       7   37.63
     9.6   38.23    12.6   39.23
#Mann= 3 , 0 , 0
   -16.8    .025       0       0    .025       0       7    .025       0
Bank Sta=0,7
XS Rating Curve= 0
Exp/Cntr=.3,.1

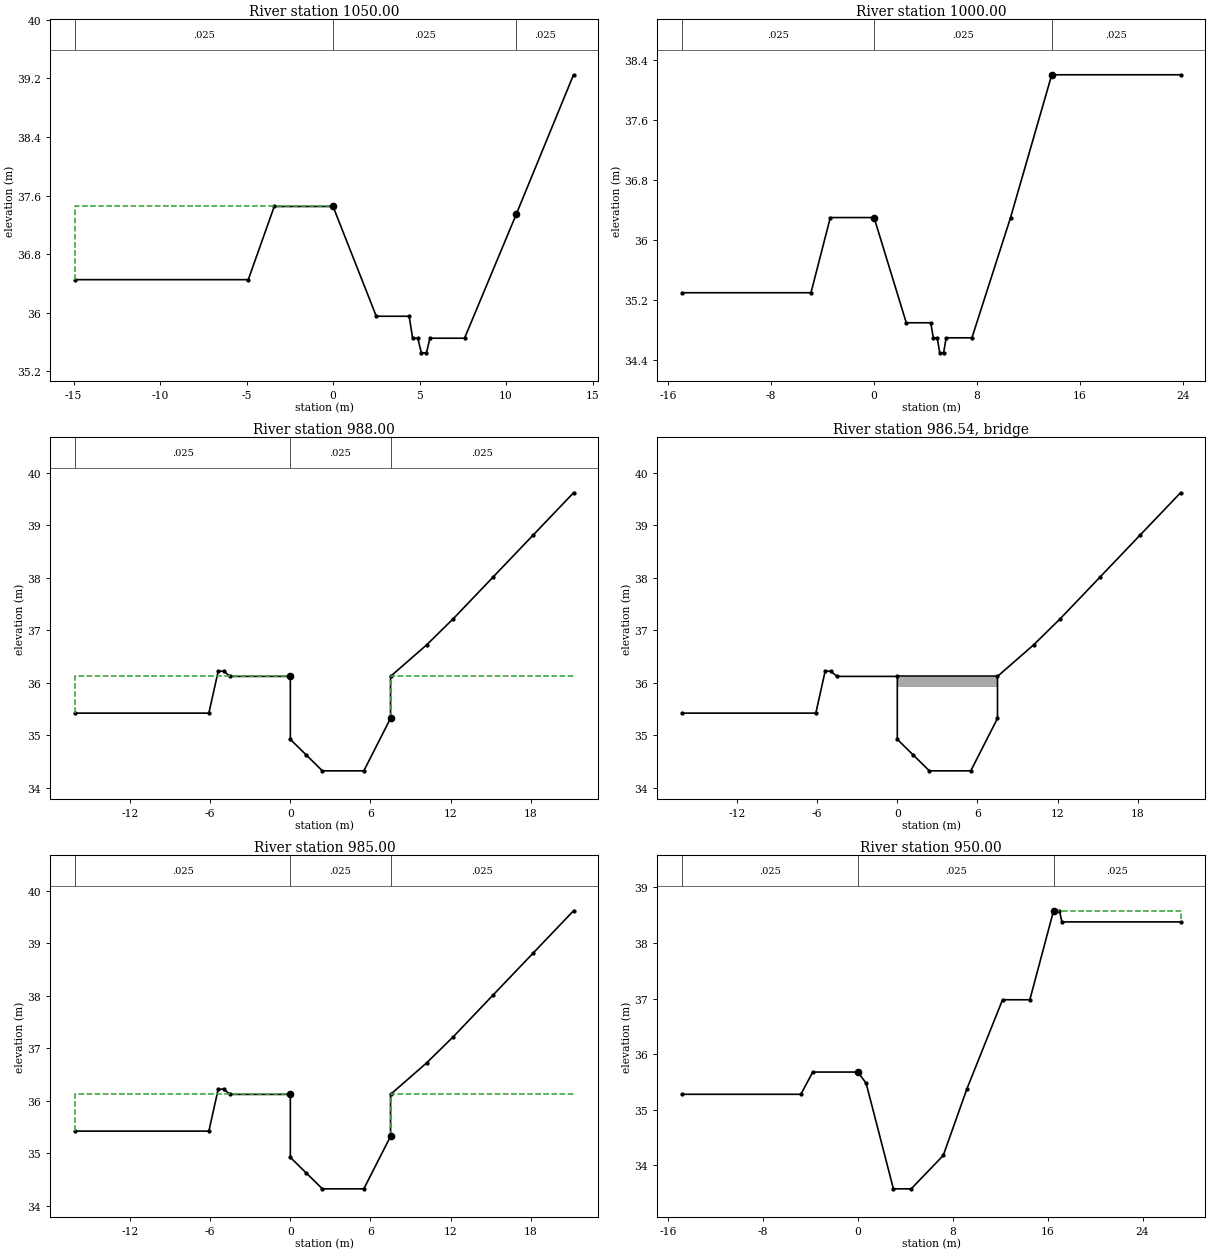
Type RM Length L Ch R = 1 ,1050.00 ,50,50,50
BEGIN DESCRIPTION:
21
END DESCRIPTION:
#Sta/Elev= 14
   -14.9   36.45    -4.9   36.45    -3.4   37.45       0   37.45     2.5   35.95
     4.4   35.95     4.6   35.65     4.9   35.65     5.1   35.45     5.4   35.45
     5.6   35.65     7.6   35.65    10.6   37.35    13.9   39.25
#Mann= 3 , 0 , 0
   -14.9    .025       0       0    .025       0    10.6    .025       0
#XS Ineff= 2 , 0
               0   37.45    10.6           37.35
Permanent Ineff=
       F       F
Bank Sta=0,10.6
XS Rating Curve= 0
Exp/Cntr=.3,.1

Type RM Length L Ch R = 1 ,1000.00 ,12,12,12
BEGIN DESCRIPTION:
20
END DESCRIPTION:
#Sta/Elev= 15
   -14.9    35.3    -4.9    35.3    -3.4    36.3       0    36.3     2.5    34.9
     4.4    34.9     4.6    34.7     4.9    34.7     5.1    34.5     5.4    34.5
     5.6    34.7     7.6    34.7    10.6    36.3    13.8    38.2    23.8    38.2
#Mann= 3 , 0 , 0
   -14.9    .025       0       0    .025       0    13.8    .025       0
#XS Ineff= 2 , 0
       0       0    36.3    13.8       0    38.2
Permanent Ineff=
       F       F
Bank Sta=0,13.8
XS Rating Curve= 0
Exp/Cntr=.3,.1

Type RM Length L Ch R = 1 ,988.00  ,3,3,3
BEGIN DESCRIPTION:
19.038
END DESCRIPTION:
#Sta/Elev= 17
   -16.1   35.42    -6.1   35.42    -5.4   36.22      -5   36.22    -4.5   36.12
       0   36.12       0   34.92     1.2   34.62     2.4   34.32     5.5   34.32
     7.5   35.32     7.5   36.12    10.2   36.72    12.2   37.22    15.2   38.02
    18.2   38.82    21.2   39.62
#Mann= 3 , 0 , 0
   -16.1    .025       0       0    .025       0     7.5    .025       0
#XS Ineff= 2 , 0
               0   36.12     7.5           36.12
Permanent Ineff=
       F       F
Bank Sta=0,7.5
XS Rating Curve= 0
Exp/Cntr=.3,.1

Type RM Length L Ch R = 3 ,986.54  ,,,
BEGIN DESCRIPTION:
19.0365
END DESCRIPTION:
Bridge Culvert--1,0,-1,-1, 0
Deck Dist Width WeirC Skew NumUp NumDn MinLoCord MaxHiCord MaxSubmerge Is_Ogee
.01,2.9,1.44,0, 2, 2, , , .95, 0, 0,0,,
       0     7.5
   36.12   36.12
   35.92   35.92
       0     7.5
   36.12   36.12
   35.92   35.92
BR Coef=-1 , 1 , 0 ,, 0 ,,,.8,-1,1.2,0,
WSPro=,,,, 1 ,,,, 0 ,,,, 0 ,,,,-1 ,-1 ,-1 , 0 , 0 , 0 , 0 , 0
BC Design=,, 0 ,, 0 ,,,,,,

Type RM Length L Ch R = 1 ,985.00  ,35,35,35
BEGIN DESCRIPTION:
19.035
END DESCRIPTION:
#Sta/Elev= 17
   -16.1   35.42    -6.1   35.42    -5.4   36.22      -5   36.22    -4.5   36.12
       0   36.12       0   34.92     1.2   34.62     2.4   34.32     5.5   34.32
     7.5   35.32     7.5   36.12    10.2   36.72    12.2   37.22    15.2   38.02
    18.2   38.82    21.2   39.62
#Mann= 3 , 0 , 0
   -16.1    .025       0       0    .025       0     7.5    .025       0
#XS Ineff= 2 , 0
               0   36.12     7.5           36.12
Permanent Ineff=
       F       F
Bank Sta=0,7.5
XS Rating Curve= 0
Exp/Cntr=.3,.1

Type RM Length L Ch R = 1 ,950.00  ,7,7,7
BEGIN DESCRIPTION:
19
END DESCRIPTION:
#Sta/Elev= 15
   -14.8   35.28    -4.8   35.28    -3.8   35.68       0   35.68      .7   35.48
       3   33.58     4.5   33.58     7.2   34.18     9.2   35.38    12.2   36.98
    14.5   36.98    16.5   38.58      17   38.58    17.2   38.38    27.2   38.38
#Mann= 3 , 0 , 0
   -14.8    .025       0       0    .025       0    16.5    .025       0
#XS Ineff= 2 , 0
       0       0   35.68    16.5       0   38.58
Permanent Ineff=
       F       F
Bank Sta=0,16.5
XS Rating Curve= 0
Exp/Cntr=.3,.1

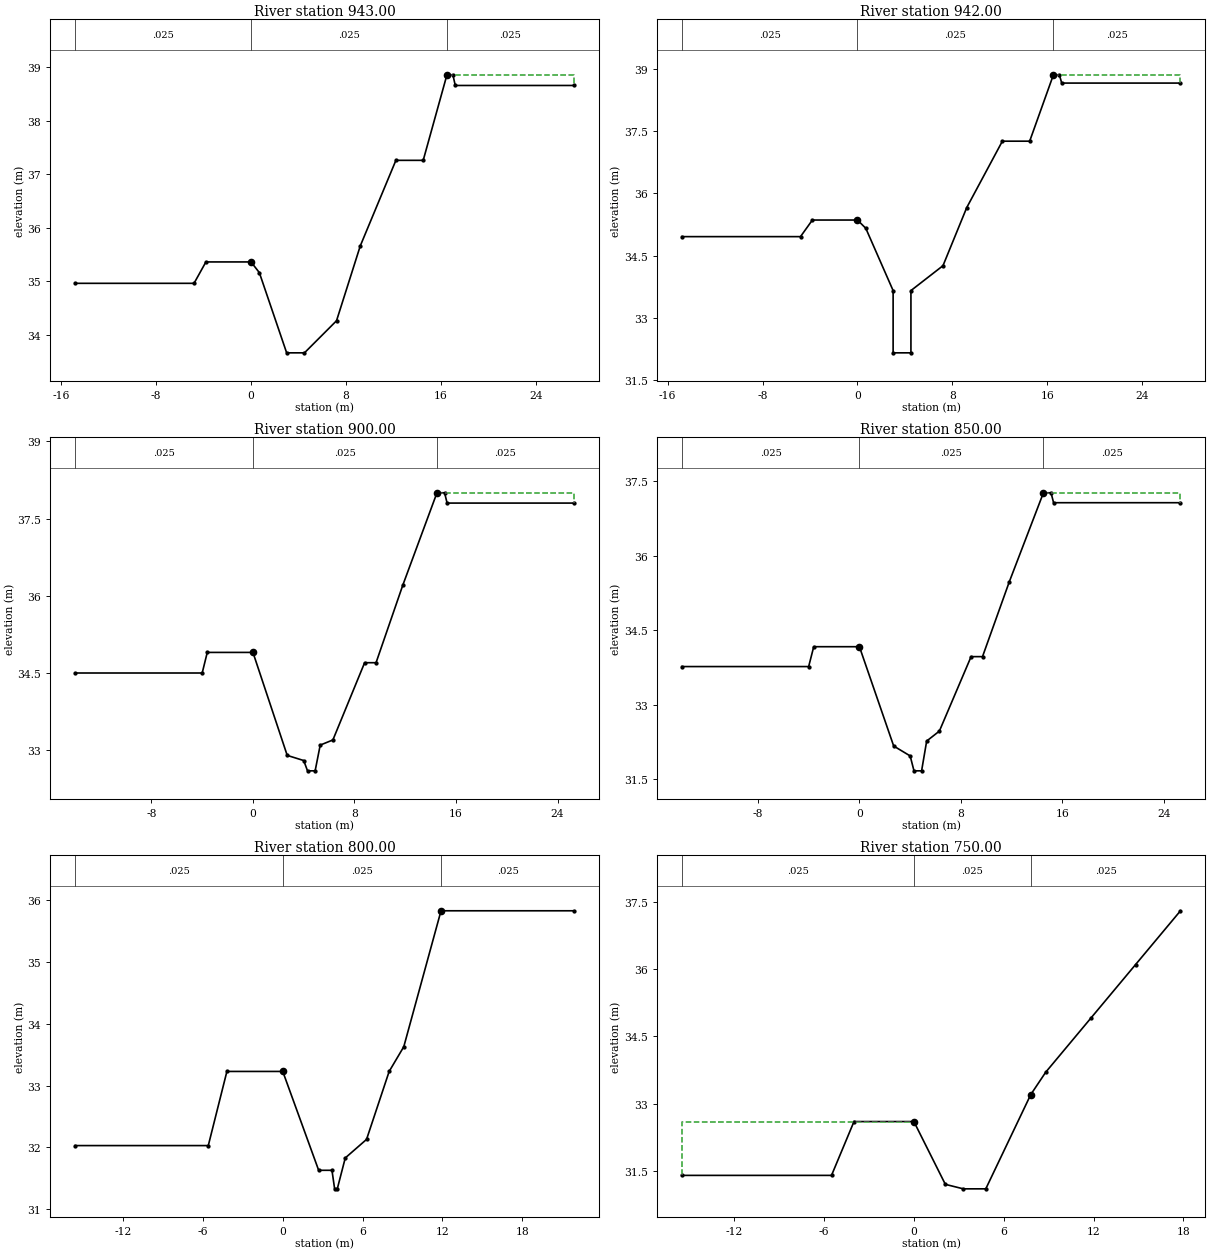
Type RM Length L Ch R = 1 ,943.00  ,1,1,1
BEGIN DESCRIPTION:
18.043
END DESCRIPTION:
#Sta/Elev= 15
   -14.8   34.96    -4.8   34.96    -3.8   35.36       0   35.36      .7   35.16
       3   33.66     4.5   33.66     7.2   34.26     9.2   35.66    12.2   37.26
    14.5   37.26    16.5   38.86      17   38.86    17.2   38.66    27.2   38.66
#Mann= 3 , 0 , 0
   -14.8    .025       0       0    .025       0    16.5    .025       0
#XS Ineff= 2 , 0
       0       0   35.36    16.5       0   38.86
Permanent Ineff=
       F       F
Bank Sta=0,16.5
XS Rating Curve= 0
Exp/Cntr=.3,.1

Type RM Length L Ch R = 1 ,942.00  ,42,42,42
BEGIN DESCRIPTION:
18.042
END DESCRIPTION:
#Sta/Elev= 17
   -14.8   34.96    -4.8   34.96    -3.8   35.36       0   35.36      .7   35.16
       3   33.66       3   32.16     4.5   32.16     4.5   33.66     7.2   34.26
     9.2   35.66    12.2   37.26    14.5   37.26    16.5   38.86      17   38.86
    17.2   38.66    27.2   38.66
#Mann= 3 , 0 , 0
   -14.8    .025       0       0    .025       0    16.5    .025       0
#XS Ineff= 2 , 0
       0       0   35.36    16.5       0   38.86
Permanent Ineff=
       F       F
Bank Sta=0,16.5
XS Rating Curve= 0
Exp/Cntr=.3,.1

Type RM Length L Ch R = 1 ,900.00  ,50,50,50
BEGIN DESCRIPTION:
18
END DESCRIPTION:
#Sta/Elev= 17
     -14    34.5      -4    34.5    -3.6    34.9       0    34.9     2.7    32.9
       4    32.8     4.3    32.6     4.9    32.6     5.3    33.1     6.3    33.2
     8.8    34.7     9.7    34.7    11.8    36.2    14.5      38    15.1      38
    15.3    37.8    25.3    37.8
#Mann= 3 , 0 , 0
     -14    .025       0       0    .025       0    14.5    .025       0
#XS Ineff= 2 , 0
       0       0    34.9    14.5       0      38
Permanent Ineff=
       F       F
Bank Sta=0,14.5
XS Rating Curve= 0
Exp/Cntr=.3,.1

Type RM Length L Ch R = 1 ,850.00  ,50,50,50
BEGIN DESCRIPTION:
17
END DESCRIPTION:
#Sta/Elev= 17
     -14   33.77      -4   33.77    -3.6   34.17       0   34.17     2.7   32.17
       4   31.97     4.3   31.67     4.9   31.67     5.3   32.27     6.3   32.47
     8.8   33.97     9.7   33.97    11.8   35.47    14.5   37.27    15.1   37.27
    15.3   37.07    25.3   37.07
#Mann= 3 , 0 , 0
     -14    .025       0       0    .025       0    14.5    .025       0
#XS Ineff= 2 , 0
       0       0   34.17    14.5       0   37.27
Permanent Ineff=
       F       F
Bank Sta=0,14.5
XS Rating Curve= 0
Exp/Cntr=.3,.1

Type RM Length L Ch R = 1 ,800.00  ,50,50,50
BEGIN DESCRIPTION:
16
END DESCRIPTION:
#Sta/Elev= 14
   -15.6   32.03    -5.6   32.03    -4.2   33.23       0   33.23     2.7   31.63
     3.7   31.63     3.9   31.33     4.1   31.33     4.7   31.83     6.3   32.13
       8   33.23     9.1   33.63    11.9   35.83    21.9   35.83
#Mann= 3 , 0 , 0
   -15.6    .025       0       0    .025       0    11.9    .025       0
#XS Ineff= 2 , 0
       0       0   33.23    11.9       0   35.83
Permanent Ineff=
       F       F
Bank Sta=0,11.9
XS Rating Curve= 0
Exp/Cntr=.3,.1

Type RM Length L Ch R = 1 ,750.00  ,50,50,50
BEGIN DESCRIPTION:
15
END DESCRIPTION:
#Sta/Elev= 12
   -15.5    31.4    -5.5    31.4      -4    32.6       0    32.6     2.1    31.2
     3.3    31.1     4.8    31.1     7.8    33.2     8.8    33.7    11.8    34.9
    14.8    36.1    17.8    37.3
#Mann= 3 , 0 , 0
   -15.5    .025       0       0    .025       0     7.8    .025       0
#XS Ineff= 2 , 0
               0    32.6     7.8            33.2
Permanent Ineff=
       F       F
Bank Sta=0,7.8
XS Rating Curve= 0
Exp/Cntr=.3,.1