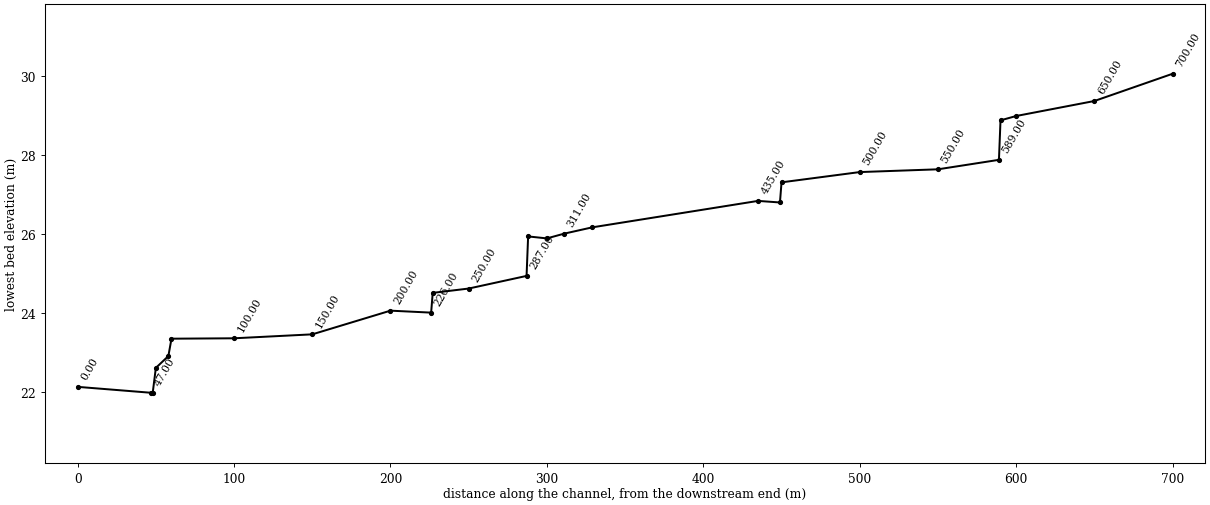
HEC-RAS study hgc.prj: hagoo-ch

--- hgc.g01 (geometry) --- (continued)

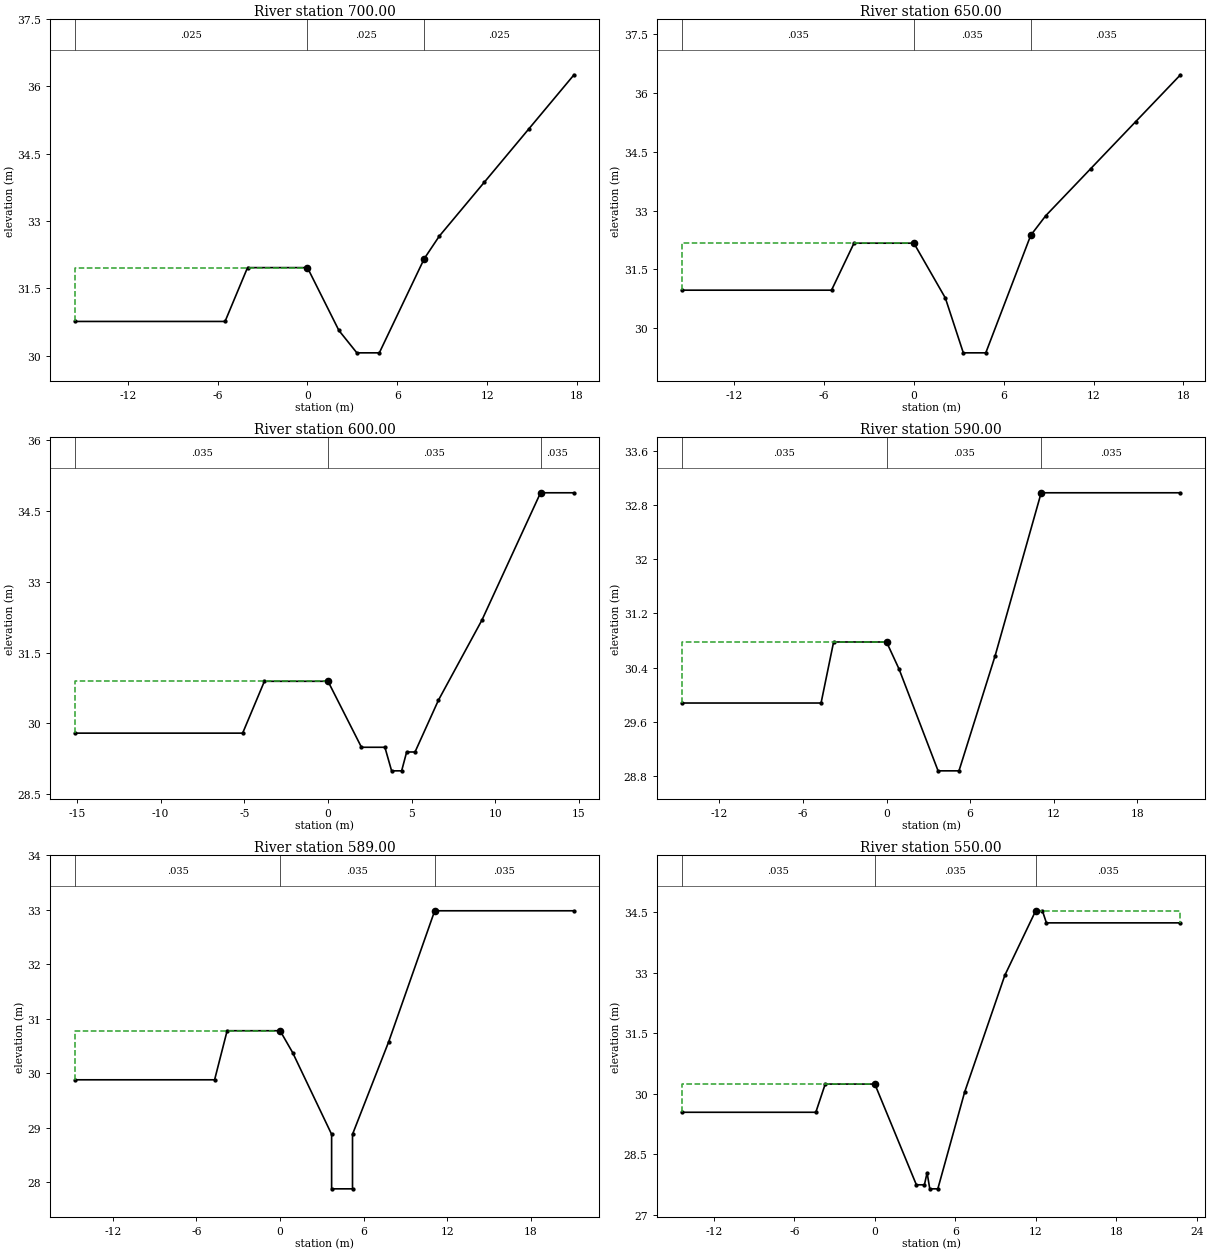
Type RM Length L Ch R = 1 ,700.00  ,50,50,50
BEGIN DESCRIPTION:
14
END DESCRIPTION:
#Sta/Elev= 12
   -15.5   30.76    -5.5   30.76      -4   31.96       0   31.96     2.1   30.56
     3.3   30.06     4.8   30.06     7.8   32.16     8.8   32.66    11.8   33.86
    14.8   35.06    17.8   36.26
#Mann= 3 , 0 , 0
   -15.5    .025       0       0    .025       0     7.8    .025       0
#XS Ineff= 2 , 0
               0   31.96     7.8           32.16
Permanent Ineff=
       F       F
Bank Sta=0,7.8
XS Rating Curve= 0
Exp/Cntr=.3,.1

Type RM Length L Ch R = 1 ,650.00  ,50,50,50
BEGIN DESCRIPTION:
13
END DESCRIPTION:
#Sta/Elev= 12
   -15.5   30.97    -5.5   30.97      -4   32.17       0   32.17     2.1   30.77
     3.3   29.37     4.8   29.37     7.8   32.37     8.8   32.87    11.8   34.07
    14.8   35.27    17.8   36.47
#Mann= 3 , 0 , 0
   -15.5    .035       0       0    .035       0     7.8    .035       0
#XS Ineff= 2 , 0
               0   32.17     7.8           32.37
Permanent Ineff=
       F       F
Bank Sta=0,7.8
XS Rating Curve= 0
Exp/Cntr=.3,.1

Type RM Length L Ch R = 1 ,600.00  ,10,10,10
BEGIN DESCRIPTION:
12
END DESCRIPTION:
#Sta/Elev= 14
   -15.1   29.79    -5.1   29.79    -3.8   30.89       0   30.89       2   29.49
     3.4   29.49     3.8   28.99     4.4   28.99     4.7   29.39     5.2   29.39
     6.6   30.49     9.2   32.19    12.7   34.89    14.7   34.89
#Mann= 3 , 0 , 0
   -15.1    .035       0       0    .035       0    12.7    .035       0
#XS Ineff= 2 , 0
               0   30.89    12.7           34.89
Permanent Ineff=
       F       F
Bank Sta=0,12.7
XS Rating Curve= 0
Exp/Cntr=.3,.1

Type RM Length L Ch R = 1 ,590.00  ,1,1,1
BEGIN DESCRIPTION:
11.040
END DESCRIPTION:
#Sta/Elev= 10
   -14.7   29.88    -4.7   29.88    -3.8   30.78       0   30.78      .9   30.38
     3.7   28.88     5.2   28.88     7.8   30.58    11.1   32.98    21.1   32.98
#Mann= 3 , 0 , 0
   -14.7    .035       0       0    .035       0    11.1    .035       0
#XS Ineff= 2 , 0
               0   30.78    11.1           32.98
Permanent Ineff=
       F       F
Bank Sta=0,11.1
XS Rating Curve= 0
Exp/Cntr=.3,.1

Type RM Length L Ch R = 1 ,589.00  ,39,39,39
BEGIN DESCRIPTION:
11.039
END DESCRIPTION:
#Sta/Elev= 12
   -14.7   29.88    -4.7   29.88    -3.8   30.78       0   30.78      .9   30.38
     3.7   28.88     3.7   27.88     5.2   27.88     5.2   28.88     7.8   30.58
    11.1   32.98    21.1   32.98
#Mann= 3 , 0 , 0
   -14.7    .035       0       0    .035       0    11.1    .035       0
#XS Ineff= 2 , 0
               0   30.78    11.1           32.98
Permanent Ineff=
       F       F
Bank Sta=0,11.1
XS Rating Curve= 0
Exp/Cntr=.3,.1

Type RM Length L Ch R = 1 ,550.00  ,50,50,50
BEGIN DESCRIPTION:
11
END DESCRIPTION:
#Sta/Elev= 15
   -14.4   29.54    -4.4   29.54    -3.7   30.24       0   30.24     3.1   27.74
     3.7   27.74     3.9   28.04     4.1   27.64     4.7   27.64     6.7   30.04
     9.7   32.94      12   34.54    12.5   34.54    12.8   34.24    22.8   34.24
#Mann= 3 , 0 , 0
   -14.4    .035       0       0    .035       0      12    .035       0
#XS Ineff= 2 , 0
               0   30.24      12           34.54
Permanent Ineff=
       F       F
Bank Sta=0,12
XS Rating Curve= 0
Exp/Cntr=.3,.1

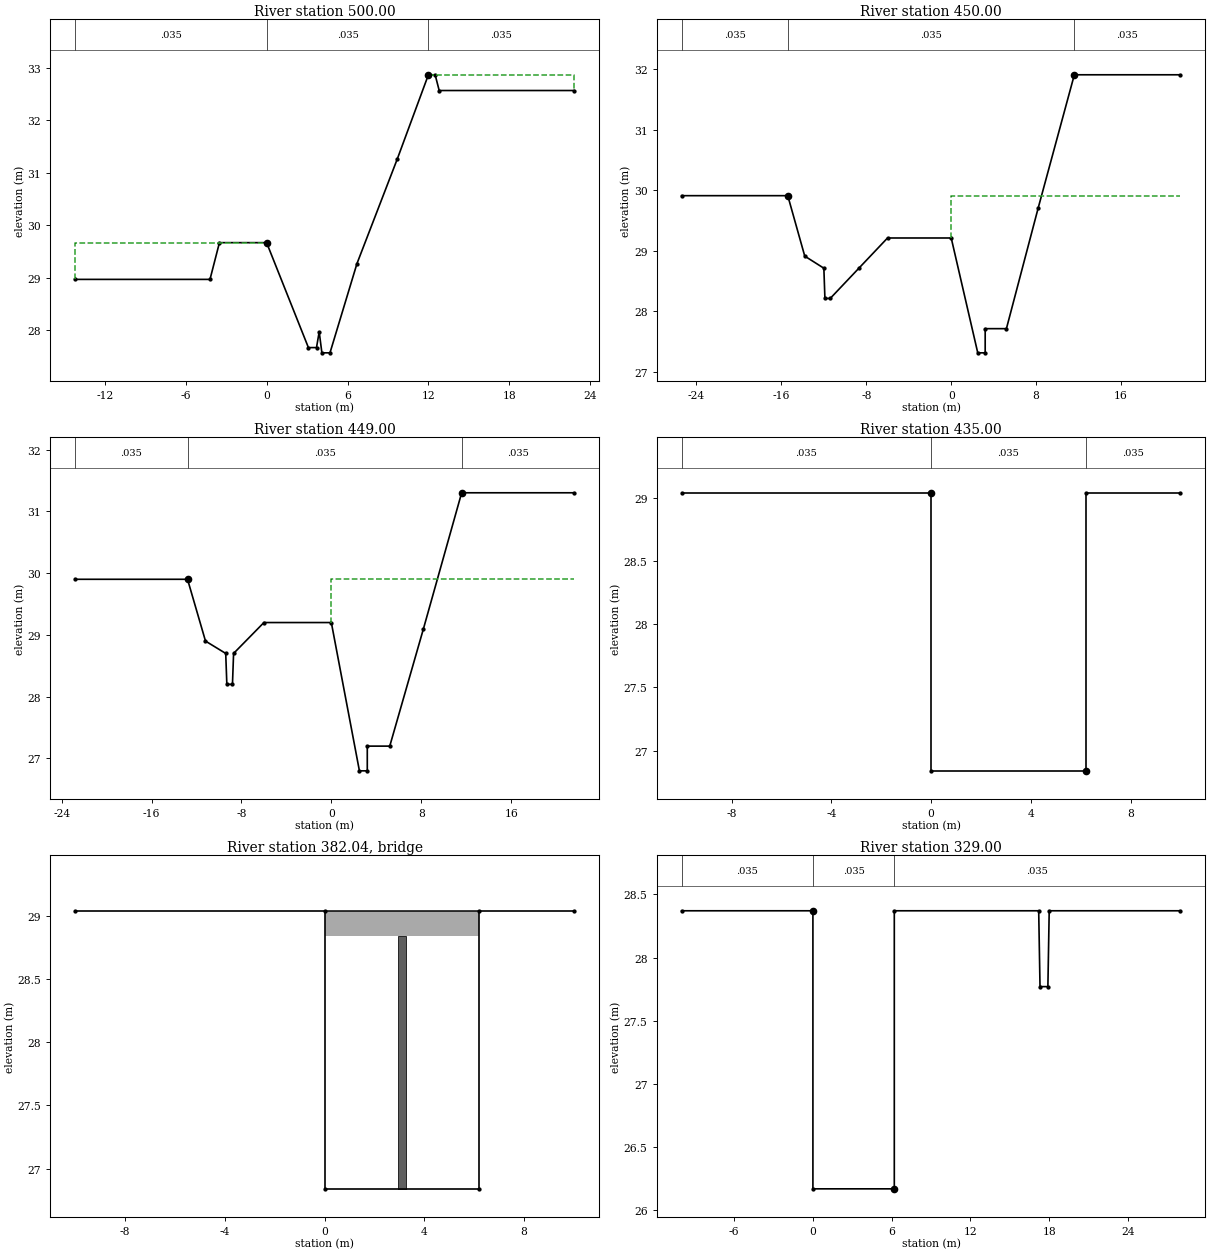
Type RM Length L Ch R = 1 ,500.00  ,50,50,50
BEGIN DESCRIPTION:
10
END DESCRIPTION:
#Sta/Elev= 15
   -14.2   28.97    -4.2   28.97    -3.5   29.67       0   29.67     3.1   27.67
     3.7   27.67     3.9   27.97     4.1   27.57     4.7   27.57     6.7   29.27
     9.7   31.27      12   32.87    12.5   32.87    12.8   32.57    22.8   32.57
#Mann= 3 , 0 , 0
   -14.2    .035       0       0    .035       0      12    .035       0
#XS Ineff= 2 , 0
               0   29.67      12           32.87
Permanent Ineff=
       F       F
Bank Sta=0,12
XS Rating Curve= 0
Exp/Cntr=.3,.1

Type RM Length L Ch R = 1 ,450.00  ,1,1,1
BEGIN DESCRIPTION:
9
END DESCRIPTION:
#Sta/Elev= 16
   -25.4   29.91   -15.4   29.91   -13.8   28.91     -12   28.71   -11.9   28.21
   -11.4   28.21    -8.7   28.71      -6   29.21       0   29.21     2.5   27.31
     3.2   27.31     3.2   27.71     5.2   27.71     8.2   29.71    11.6   31.91
    21.6   31.91
#Mann= 3 , 0 , 0
   -25.4    .035       0   -15.4    .035       0    11.6    .035       0
#XS Ineff= 2 , 0
       0   -15.4   29.91    11.6       0   31.91
Permanent Ineff=
       F       F
Bank Sta=-15.4,11.6
XS Rating Curve= 0
Exp/Cntr=.3,.1

Type RM Length L Ch R = 1 ,449.00  ,14,14,14
BEGIN DESCRIPTION:
8.049
END DESCRIPTION:
#Sta/Elev= 16
   -22.8    29.9   -12.8    29.9   -11.2    28.9    -9.4    28.7    -9.3    28.2
    -8.8    28.2    -8.7    28.7      -6    29.2       0    29.2     2.5    26.8
     3.2    26.8     3.2    27.2     5.2    27.2     8.2    29.1    11.6    31.3
    21.6    31.3
#Mann= 3 , 0 , 0
   -22.8    .035       0   -12.8    .035       0    11.6    .035       0
#XS Ineff= 2 , 0
       0   -12.8    29.9    11.6       0    31.3
Permanent Ineff=
       F       F
Bank Sta=-12.8,11.6
XS Rating Curve= 0
Exp/Cntr=.3,.1

Type RM Length L Ch R = 1 ,435.00  ,106,106,106
BEGIN DESCRIPTION:
8.035
END DESCRIPTION:
#Sta/Elev= 6
     -10   29.04       0   29.04       0   26.84     6.2   26.84     6.2   29.04
      10   29.04
#Mann= 3 , 0 , 0
     -10    .035       0       0    .035       0     6.2    .035       0
#XS Ineff= 2 , 0
       0       0   29.04     6.2       0   26.84
Permanent Ineff=
       F       F
Bank Sta=0,6.2
XS Rating Curve= 0
Exp/Cntr=.3,.1

Type RM Length L Ch R = 3 ,382.04  ,,,
BEGIN DESCRIPTION:
7.032
END DESCRIPTION:
Bridge Culvert--1,0,-1,-1, 0
Deck Dist Width WeirC Skew NumUp NumDn MinLoCord MaxHiCord MaxSubmerge Is_Ogee
.01,105.9,1.44,0, 2, 2, , , .95, 0, 0,0,,
       0     6.2
   29.04   29.04
   28.84   28.84
       0     6.2
   28.37   28.37
   28.17   28.17
Pier Skew, UpSta & Num, DnSta & Num=  ,3.1, 2 ,3.1, 2 , 0 , 0 , 0 ,,
      .3      .3
   26.84   29.04
      .3      .3
   26.17   28.37
BR Coef=-1 , 1 , 1 ,.9, 0 ,,,.8,-1,1.2,0,
WSPro=,,,, 1 ,,,, 0 ,,,, 0 ,,,,-1 ,-1 ,-1 , 0 , 0 , 0 , 0 , 0
BC Design=,, 0 ,, 0 ,,,,,,

Type RM Length L Ch R = 1 ,329.00  ,18,18,18
BEGIN DESCRIPTION:
6.029
END DESCRIPTION:
#Sta/Elev= 10
     -10   28.37       0   28.37       0   26.17     6.2   26.17     6.2   28.37
    17.2   28.37    17.3   27.77    17.9   27.77      18   28.37      28   28.37
#Mann= 3 , 0 , 0
     -10    .035       0       0    .035       0     6.2    .035       0
#XS Ineff= 2 , 0
       0       0   28.37     6.2       0   26.17
Permanent Ineff=
       F       F
Bank Sta=0,6.2
XS Rating Curve= 0
Exp/Cntr=.3,.1

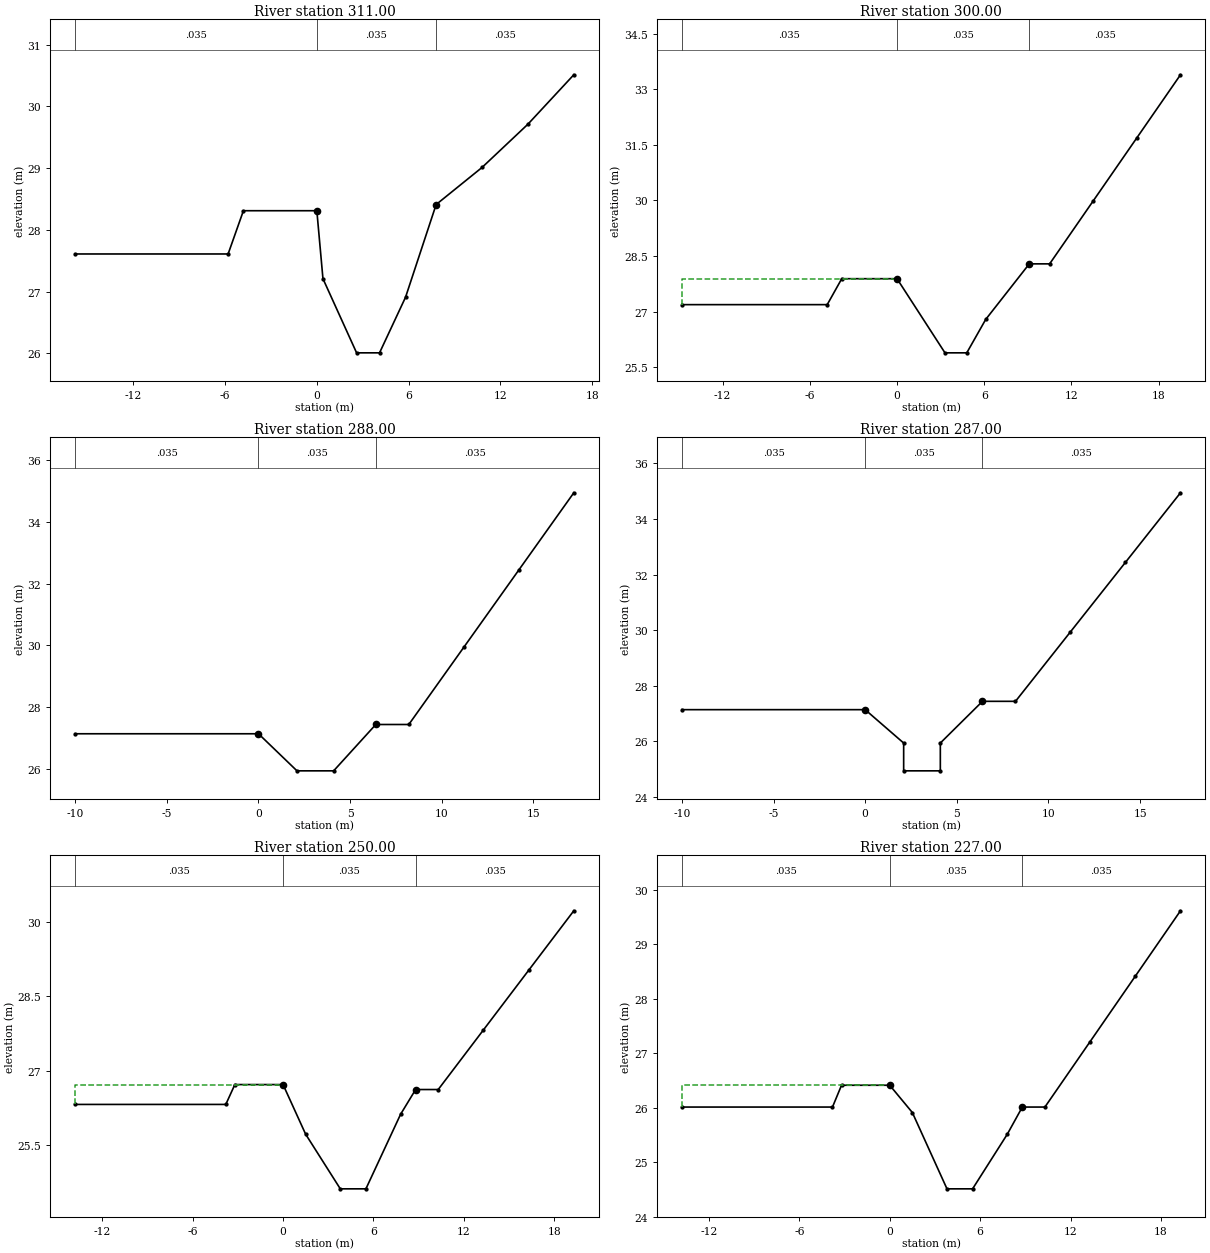
Type RM Length L Ch R = 1 ,311.00  ,11,11,11
BEGIN DESCRIPTION:
6.011
END DESCRIPTION:
#Sta/Elev= 12
   -15.8   27.61    -5.8   27.61    -4.8   28.31       0   28.31      .4   27.21
     2.6   26.01     4.1   26.01     5.8   26.91     7.8   28.41    10.8   29.01
    13.8   29.71    16.8   30.51
#Mann= 3 , 0 , 0
   -15.8    .035       0       0    .035       0     7.8    .035       0
#XS Ineff= 2 , 0
       0       0   28.31     7.8       0   28.41
Permanent Ineff=
       F       F
Bank Sta=0,7.8
XS Rating Curve= 0
Exp/Cntr=.3,.1

Type RM Length L Ch R = 1 ,300.00  ,12,12,12
BEGIN DESCRIPTION:
6
END DESCRIPTION:
#Sta/Elev= 12
   -14.8   27.19    -4.8   27.19    -3.8   27.89       0   27.89     3.3   25.89
     4.8   25.89     6.1   26.79     9.1   28.29    10.5   28.29    13.5   29.99
    16.5   31.69    19.5   33.39
#Mann= 3 , 0 , 0
   -14.8    .035       0       0    .035       0     9.1    .035       0
#XS Ineff= 2 , 0
               0   27.89     9.1           28.29
Permanent Ineff=
       F       F
Bank Sta=0,9.1
XS Rating Curve= 0
Exp/Cntr=.3,.1

Type RM Length L Ch R = 1 ,288.00  ,1,1,1
BEGIN DESCRIPTION:
5.038
END DESCRIPTION:
#Sta/Elev= 9
     -10   27.14       0   27.14     2.1   25.94     4.1   25.94     6.4   27.44
     8.2   27.44    11.2   29.94    14.2   32.44    17.2   34.94
#Mann= 3 , 0 , 0
     -10    .035       0       0    .035       0     6.4    .035       0
#XS Ineff= 2 , 0
               0   27.14     6.4           27.44
Permanent Ineff=
       F       F
Bank Sta=0,6.4
XS Rating Curve= 0
Exp/Cntr=.3,.1

Type RM Length L Ch R = 1 ,287.00  ,37,37,37
BEGIN DESCRIPTION:
5.037
END DESCRIPTION:
#Sta/Elev= 11
     -10   27.14       0   27.14     2.1   25.94     2.1   24.94     4.1   24.94
     4.1   25.94     6.4   27.44     8.2   27.44    11.2   29.94    14.2   32.44
    17.2   34.94
#Mann= 3 , 0 , 0
     -10    .035       0       0    .035       0     6.4    .035       0
#XS Ineff= 2 , 0
               0   27.14     6.4           27.44
Permanent Ineff=
       F       F
Bank Sta=0,6.4
XS Rating Curve= 0
Exp/Cntr=.3,.1

Type RM Length L Ch R = 1 ,250.00  ,23,23,23
BEGIN DESCRIPTION:
5
END DESCRIPTION:
#Sta/Elev= 13
   -13.8   26.32    -3.8   26.32    -3.2   26.72       0   26.72     1.5   25.72
     3.8   24.62     5.5   24.62     7.8   26.12     8.8   26.62    10.3   26.62
    13.3   27.82    16.3   29.02    19.3   30.22
#Mann= 3 , 0 , 0
   -13.8    .035       0       0    .035       0     8.8    .035       0
#XS Ineff= 2 , 0
               0   26.72     8.8           26.62
Permanent Ineff=
       F       F
Bank Sta=0,8.8
XS Rating Curve= 0
Exp/Cntr=.3,.1

Type RM Length L Ch R = 1 ,227.00  ,1,1,1
BEGIN DESCRIPTION:
4.027
END DESCRIPTION:
#Sta/Elev= 13
   -13.8   26.01    -3.8   26.01    -3.2   26.41       0   26.41     1.5   25.91
     3.8   24.51     5.5   24.51     7.8   25.51     8.8   26.01    10.3   26.01
    13.3   27.21    16.3   28.41    19.3   29.61
#Mann= 3 , 0 , 0
   -13.8    .035       0       0    .035       0     8.8    .035       0
#XS Ineff= 2 , 0
               0   26.41     8.8           26.01
Permanent Ineff=
       F       F
Bank Sta=0,8.8
XS Rating Curve= 0
Exp/Cntr=.3,.1

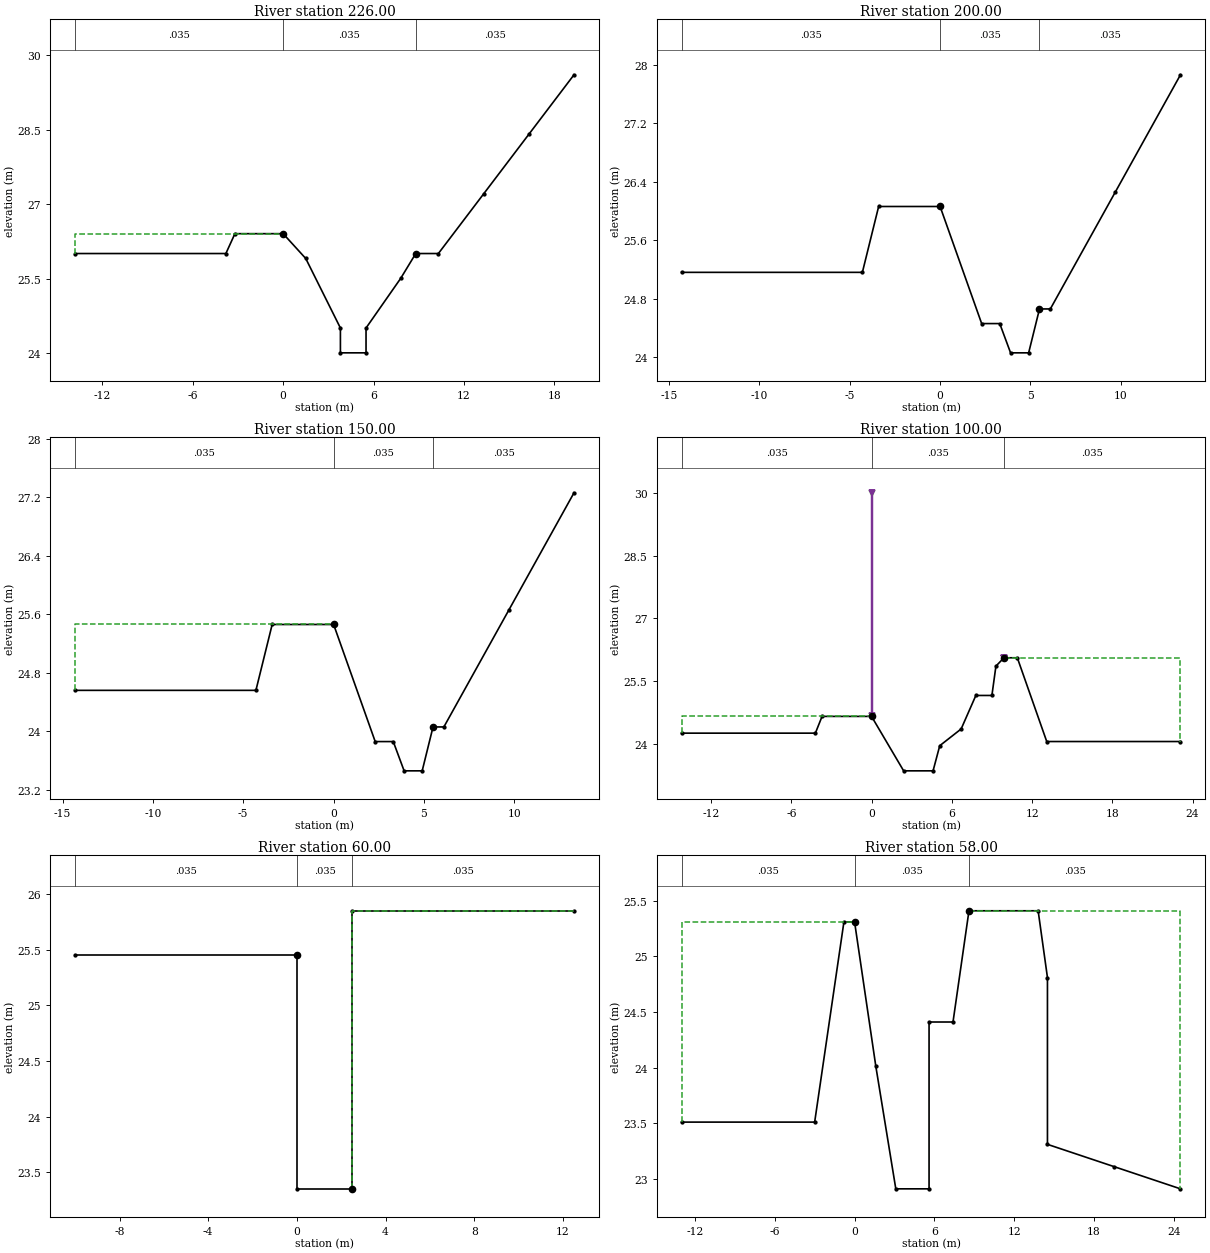
Type RM Length L Ch R = 1 ,226.00  ,26,26,26
BEGIN DESCRIPTION:
4.026
END DESCRIPTION:
#Sta/Elev= 15
   -13.8   26.01    -3.8   26.01    -3.2   26.41       0   26.41     1.5   25.91
     3.8   24.51     3.8   24.01     5.5   24.01     5.5   24.51     7.8   25.51
     8.8   26.01    10.3   26.01    13.3   27.21    16.3   28.41    19.3   29.61
#Mann= 3 , 0 , 0
   -13.8    .035       0       0    .035       0     8.8    .035       0
#XS Ineff= 2 , 0
               0   26.41     8.8           26.01
Permanent Ineff=
       F       F
Bank Sta=0,8.8
XS Rating Curve= 0
Exp/Cntr=.3,.1

Type RM Length L Ch R = 1 ,200.00  ,50,50,50
BEGIN DESCRIPTION:
4
END DESCRIPTION:
#Sta/Elev= 12
   -14.3   25.16    -4.3   25.16    -3.4   26.06       0   26.06     2.3   24.46
     3.3   24.46     3.9   24.06     4.9   24.06     5.5   24.66     6.1   24.66
     9.7   26.26    13.3   27.86
#Mann= 3 , 0 , 0
   -14.3    .035       0       0    .035       0     5.5    .035       0
#XS Ineff= 2 , 0
       0       0   26.06     5.5       0   24.66
Permanent Ineff=
       F       F
Bank Sta=0,5.5
XS Rating Curve= 0
Exp/Cntr=.3,.1

Type RM Length L Ch R = 1 ,150.00  ,50,50,50
BEGIN DESCRIPTION:
3
END DESCRIPTION:
#Sta/Elev= 12
   -14.3   24.56    -4.3   24.56    -3.4   25.46       0   25.46     2.3   23.86
     3.3   23.86     3.9   23.46     4.9   23.46     5.5   24.06     6.1   24.06
     9.7   25.66    13.3   27.26
#Mann= 3 , 0 , 0
   -14.3    .035       0       0    .035       0     5.5    .035       0
#XS Ineff= 2 , 0
               0   25.46     5.5           24.06
Permanent Ineff=
       F       F
Bank Sta=0,5.5
XS Rating Curve= 0
Exp/Cntr=.3,.1

Type RM Length L Ch R = 1 ,100.00  ,40,40,40
BEGIN DESCRIPTION:
2
END DESCRIPTION:
#Sta/Elev= 15
   -14.2   24.26    -4.2   24.26    -3.7   24.66       0   24.66     2.4   23.36
     4.6   23.36     5.1   23.96     6.7   24.36     7.8   25.16       9   25.16
     9.3   25.86     9.9   26.06    10.9   26.06    13.1   24.06    23.1   24.06
#Mann= 3 , 0 , 0
   -14.2    .035       0       0    .035       0     9.9    .035       0
Levee=-1,0,30,-1,9.9,26.06,,
#XS Ineff= 2 , 0
               0   24.66     9.9           26.06
Permanent Ineff=
       F       F
Bank Sta=0,9.9
XS Rating Curve= 0
Exp/Cntr=.3,.1

Type RM Length L Ch R = 1 ,60.00   ,2,2,2
BEGIN DESCRIPTION:
1.01
END DESCRIPTION:
#Sta/Elev= 6
     -10   25.45       0   25.45       0   23.35     2.5   23.35     2.5   25.85
    12.5   25.85
#Mann= 3 , 0 , 0
     -10    .035       0       0    .035       0     2.5    .035       0
#XS Ineff= 2 , 0
               0   25.45     2.5           25.85
Permanent Ineff=
       F       F
Bank Sta=0,2.5
XS Rating Curve= 0
Exp/Cntr=.3,.1

Type RM Length L Ch R = 1 ,58.00   ,8,8,8
BEGIN DESCRIPTION:
1.008
END DESCRIPTION:
#Sta/Elev= 15
     -13   23.51      -3   23.51     -.8   25.31       0   25.31     1.6   24.01
     3.1   22.91     5.6   22.91     5.6   24.41     7.4   24.41     8.6   25.41
    13.8   25.41    14.5   24.81    14.5   23.31    19.5   23.11    24.5   22.91
#Mann= 3 , 0 , 0
     -13    .035       0       0    .035       0     8.6    .035       0
#XS Ineff= 2 , 0
               0   25.31     8.6           25.41
Permanent Ineff=
       F       F
Bank Sta=0,8.6
XS Rating Curve= 0
Exp/Cntr=.3,.1

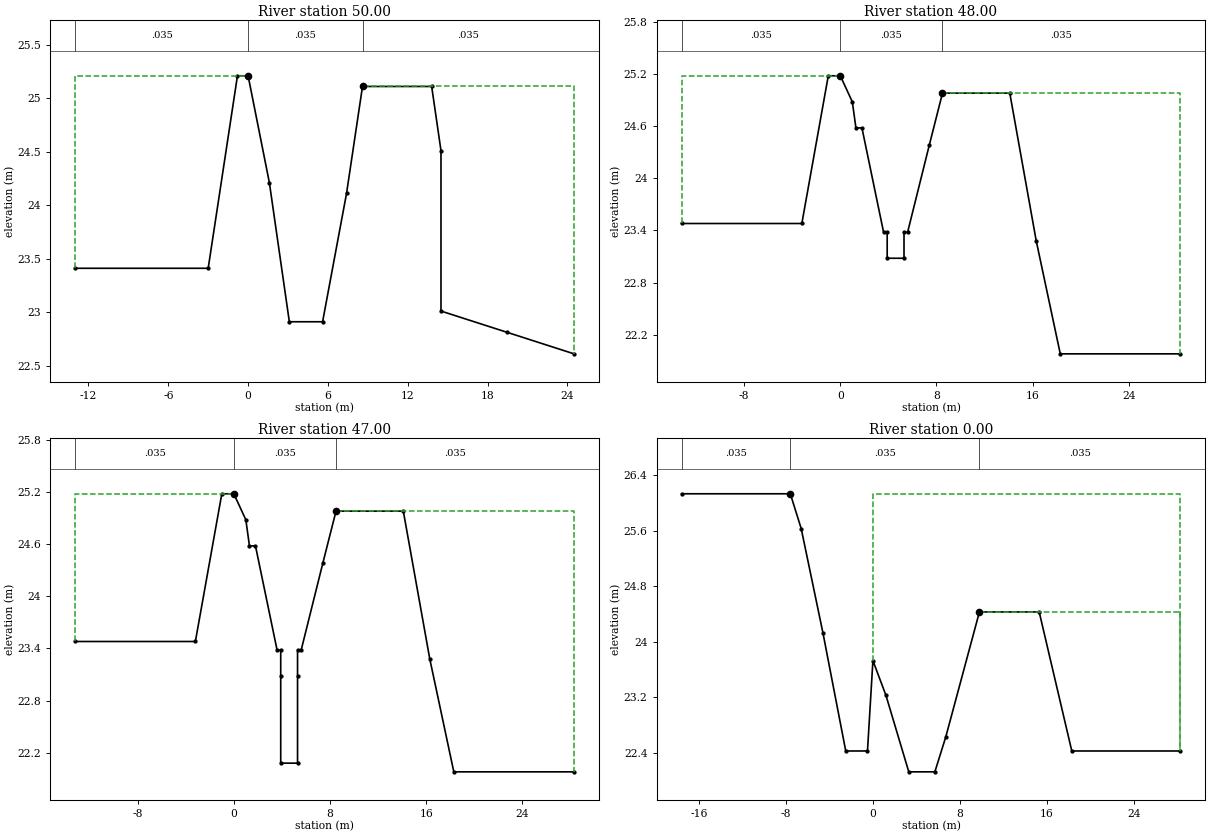
Type RM Length L Ch R = 1 ,50.00   ,2,2,2
BEGIN DESCRIPTION:
1
END DESCRIPTION:
#Sta/Elev= 14
     -13   23.41      -3   23.41     -.8   25.21       0   25.21     1.6   24.21
     3.1   22.91     5.6   22.91     7.4   24.11     8.6   25.11    13.8   25.11
    14.5   24.51    14.5   23.01    19.5   22.81    24.5   22.61
#Mann= 3 , 0 , 0
     -13    .035       0       0    .035       0     8.6    .035       0
#XS Ineff= 2 , 0
               0   25.21     8.6           25.11
Permanent Ineff=
       F       F
Bank Sta=0,8.6
XS Rating Curve= 0
Exp/Cntr=.3,.1

Type RM Length L Ch R = 1 ,48.00   ,1,1,1
BEGIN DESCRIPTION:
0.048
END DESCRIPTION:
#Sta/Elev= 19
   -13.2   23.48    -3.2   23.48      -1   25.18       0   25.18       1   24.88
     1.3   24.58     1.8   24.58     3.6   23.38     3.9   23.38     3.9   23.08
     5.3   23.08     5.3   23.38     5.6   23.38     7.4   24.38     8.5   24.98
    14.1   24.98    16.3   23.28    18.3   21.98    28.3   21.98
#Mann= 3 , 0 , 0
   -13.2    .035       0       0    .035       0     8.5    .035       0
#XS Ineff= 2 , 0
               0   25.18     8.5           24.98
Permanent Ineff=
       F       F
Bank Sta=0,8.5
XS Rating Curve= 0
Exp/Cntr=.3,.1

Type RM Length L Ch R = 1 ,47.00   ,47,47,47
BEGIN DESCRIPTION:
0.047
END DESCRIPTION:
#Sta/Elev= 21
   -13.2   23.48    -3.2   23.48      -1   25.18       0   25.18       1   24.88
     1.3   24.58     1.8   24.58     3.6   23.38     3.9   23.38     3.9   23.08
     3.9   22.08     5.3   22.08     5.3   23.08     5.3   23.38     5.6   23.38
     7.4   24.38     8.5   24.98    14.1   24.98    16.3   23.28    18.3   21.98
    28.3   21.98
#Mann= 3 , 0 , 0
   -13.2    .035       0       0    .035       0     8.5    .035       0
#XS Ineff= 2 , 0
               0   25.18     8.5           24.98
Permanent Ineff=
       F       F
Bank Sta=0,8.5
XS Rating Curve= 0
Exp/Cntr=.3,.1

Type RM Length L Ch R = 1 ,0.00    ,0,0,0
BEGIN DESCRIPTION:
0
END DESCRIPTION:
#Sta/Elev= 15
   -17.6   26.13    -7.6   26.13    -6.6   25.63    -4.6   24.13    -2.5   22.43
     -.5   22.43       0   23.73     1.2   23.23     3.3   22.13     5.7   22.13
     6.7   22.63     9.8   24.43    15.3   24.43    18.3   22.43    28.3   22.43
#Mann= 3 , 0 , 0
   -17.6    .035       0    -7.6    .035       0     9.8    .035       0
#XS Ineff= 2 , 0
       0    -7.6   26.13     9.8       0   24.43
Permanent Ineff=
       F       F
Bank Sta=-7.6,9.8
XS Rating Curve= 0
Exp/Cntr=.3,.1

Chan Stop Cuts=-1