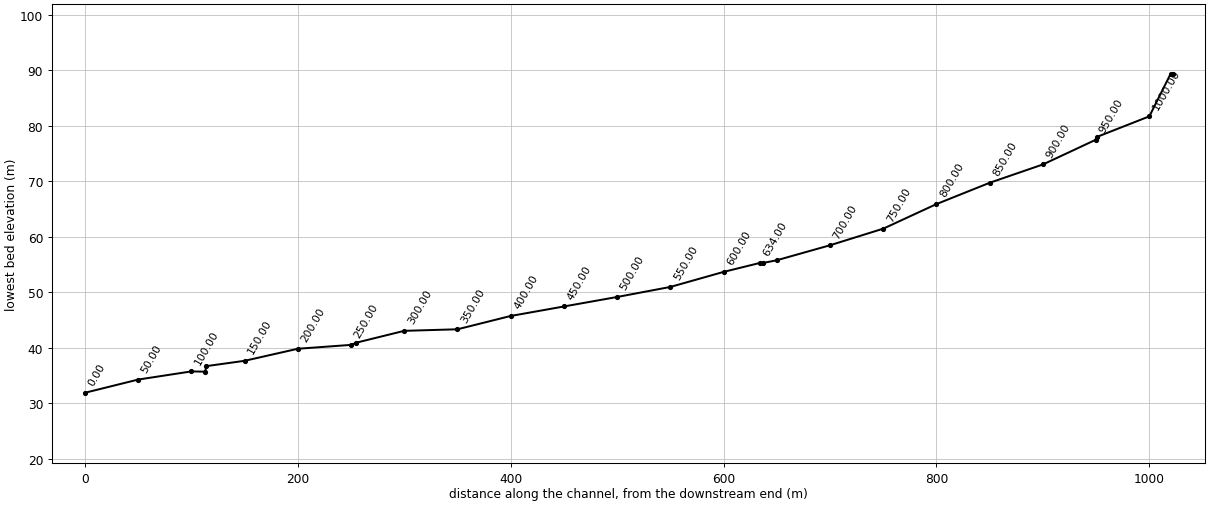
--- hpc.prj (project) ---

Proj Title=hapung-ch
Current Plan=p01
Default Exp/Contr=.3,.1
SI Units
Geom File=g01
Flow File=f01
Plan File=p01
Y Axis Title=Elevation
X Axis Title(PF)=Main Channel Distance
X Axis Title(XS)=Station
BEGIN DESCRIPTION:
           BACK WATER COMPUTATION
      APPLICATION OF HEC-2 BY Samju Construction Engineering
      ÇÏÆòÃµ(¿ËÃµÀ¾): 30,50,80,100,150³âºóµµ °³¼öÀü
END DESCRIPTION:
DSS Export Rating Curves= 0
DSS Export Rating Curve Sorted= 0
DSS Export Volume Flow Curves= 0
DXF OffsetX= 0
DXF OffsetY= 0
DXF ScaleX= 1
DXF ScaleY= 10

--- hpc.p01 (plan) ---

Plan Title=Imported Plan 01
Version=Version 3.0.1  Mar 2001
Short Identifier=Imported Pla
Geom File=g01
Flow File=f01
Subcritical Flow
K Sum by GR= 0
Std Step Tol= 0.003
Critical Tol= 0.003
Num of Std Step Trials= 20
Max Error Tol= 0.1
Flow Tol Ratio= 0.001
Split Flow NTrial= 30
Split Flow Tol= 0.02
Split Flow Ratio= 0.02
Log Output Level= 0
Friction Slope Method= 1
Unsteady Friction Slope Method= 2
Parabolic Critical Depth
Global Vel Dist= 0 , 0 , 0
Global Log Level= 0
CheckData=True
Encroach Param=-1 ,0,0, 0
Computation Interval=1HOUR
Output Interval=1HOUR
Run HTab= 0
Run UNet= 0
Run PostProcess= 0
UNET Theta= 1
UNET ZTol= 0.02
UNET ZSATol= 0.1
UNET MxIter= 20
UNET MaxInSteps= 20
UNET DtIC= 0
UNET DtMin= 0
UNET MaxCRTS= 20
UNET WFStab= 2
UNET SFStab= 1
UNET WFX= 1
UNET SFX= 1
UNET Convert EG Bridges=-1
UNET Use Existing IB Tables=-1
Instantaneous Interval=1HOUR
Write IC File= 0
Write Velocity= 0
Write Detailed= 0

--- hpc.f01 (steady flow) ---

Flow Title=Imported Flow 01
Version=Version 3.0.1  Mar 2001
Number of Profiles= 5
Profile Names=10yr,20yr,30yr,50yr,80yr
River Rch & RM=RIVER-1,Reach-1         ,21.022
   15.49   17.06   17.99   19.15   20.22
River Rch & RM=hapyung,hapyung         ,1022.00
   15.49   17.06   17.99   19.15   20.22
Boundary for River Rch & Prof#=hapyung,hapyung         , 1
Up Type= 0
Dn Type= 3
Dn Slope=.0547
Boundary for River Rch & Prof#=hapyung,hapyung         , 2
Up Type= 0
Dn Type= 3
Dn Slope=.0547
Boundary for River Rch & Prof#=hapyung,hapyung         , 3
Up Type= 0
Dn Type= 3
Dn Slope=.0547
Boundary for River Rch & Prof#=hapyung,hapyung         , 4
Up Type= 0
Dn Type= 3
Dn Slope=.0547
Boundary for River Rch & Prof#=hapyung,hapyung         , 5
Up Type= 0
Dn Type= 3
Dn Slope=.0547
DSS Import GetInterval= 0
DSS Import GetPeak= 0
DSS Import FillOption= 0

--- hpc.g01 (geometry) ---

Geom Title=Imported Geom 01
Version=Version 3.0.1  Mar 2001

River Reach=hapyung         ,hapyung
Reach XY= 2
              .5             .95              .5             .05

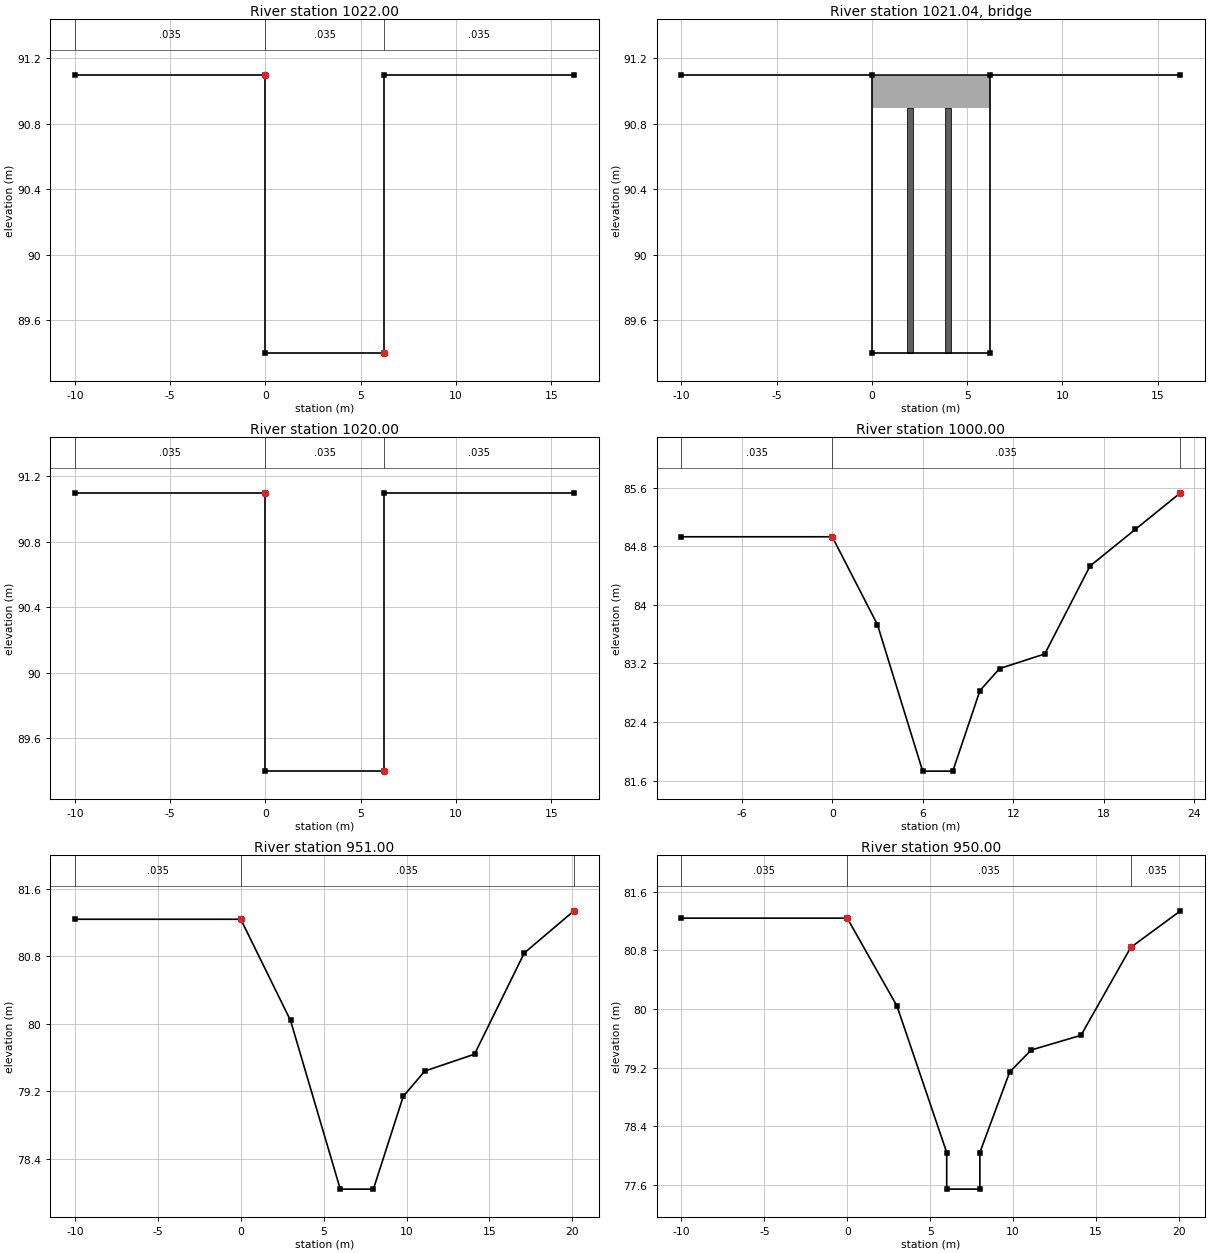
Type RM Length L Ch R = 1 ,1022.00 ,2,2,2
BEGIN DESCRIPTION:
21.022
END DESCRIPTION:
#Sta/Elev= 6
     -10    91.1       0    91.1       0    89.4     6.2    89.4     6.2    91.1
    16.2    91.1
#Mann= 3 , 0 , 0
     -10    .035       0       0    .035       0     6.2    .035       0
#XS Ineff= 2 , 0
       0       0    91.1     6.2       0    89.4
Permanent Ineff=
       F       F
Bank Sta=0,6.2
XS Rating Curve= 0
Exp/Cntr=.3,.1

Type RM Length L Ch R = 3 ,1021.04 ,,,
BEGIN DESCRIPTION:
21.021
END DESCRIPTION:
Bridge Culvert--1,0,-1,-1, 0
Deck Dist Width WeirC Skew NumUp NumDn MinLoCord MaxHiCord MaxSubmerge Is_Ogee
.01,1.9,1.44,0, 2, 2, , , .95, 0, 0,0,,
       0     6.2
    91.1    91.1
    90.9    90.9
       0     6.2
    91.1    91.1
    90.9    90.9
Pier Skew, UpSta & Num, DnSta & Num=  ,2, 2 ,2, 2 , 0 , 0 , 0 ,,
      .3      .3
    89.4    91.1
      .3      .3
    89.4    91.1
Pier Skew, UpSta & Num, DnSta & Num=  ,4, 2 ,4, 2 , 0 , 0 , 0 ,,
      .3      .3
    89.4    91.1
      .3      .3
    89.4    91.1
BR Coef=-1 , 1 , 1 ,.9, 0 ,,,.8,-1,1.2,0,
WSPro=,,,, 1 ,,,, 0 ,,,, 0 ,,,,-1 ,-1 ,-1 , 0 , 0 , 0 , 0 , 0
BC Design=,, 0 ,, 0 ,,,,,,

Type RM Length L Ch R = 1 ,1020.00 ,20,20,20
BEGIN DESCRIPTION:
21.020
END DESCRIPTION:
#Sta/Elev= 6
     -10    91.1       0    91.1       0    89.4     6.2    89.4     6.2    91.1
    16.2    91.1
#Mann= 3 , 0 , 0
     -10    .035       0       0    .035       0     6.2    .035       0
#XS Ineff= 2 , 0
       0       0    91.1     6.2       0    89.4
Permanent Ineff=
       F       F
Bank Sta=0,6.2
XS Rating Curve= 0
Exp/Cntr=.3,.1

Type RM Length L Ch R = 1 ,1000.00 ,49,49,49
BEGIN DESCRIPTION:
20
END DESCRIPTION:
#Sta/Elev= 11
     -10   84.93       0   84.93       3   83.73       6   81.73       8   81.73
     9.8   82.83    11.1   83.13    14.1   83.33    17.1   84.53    20.1   85.03
    23.1   85.53
#Mann= 3 , 0 , 0
     -10    .035       0       0    .035       0    23.1    .035       0
#XS Ineff= 2 , 0
       0       0   84.93    23.1       0   85.53
Permanent Ineff=
       F       F
Bank Sta=0,23.1
XS Rating Curve= 0
Exp/Cntr=.3,.1

Type RM Length L Ch R = 1 ,951.00  ,1,1,1
BEGIN DESCRIPTION:
19.001
END DESCRIPTION:
#Sta/Elev= 10
     -10   81.24       0   81.24       3   80.04       6   78.04       8   78.04
     9.8   79.14    11.1   79.44    14.1   79.64    17.1   80.84    20.1   81.34
#Mann= 3 , 0 , 0
     -10    .035       0       0    .035       0    20.1    .035       0
#XS Ineff= 2 , 0
               0   81.24    20.1           81.34
Permanent Ineff=
       F       F
Bank Sta=0,20.1
XS Rating Curve= 0
Exp/Cntr=.3,.1

Type RM Length L Ch R = 1 ,950.00  ,50,50,50
BEGIN DESCRIPTION:
19
END DESCRIPTION:
#Sta/Elev= 12
     -10   81.24       0   81.24       3   80.04       6   78.04       6   77.54
       8   77.54       8   78.04     9.8   79.14    11.1   79.44    14.1   79.64
    17.1   80.84    20.1   81.34
#Mann= 3 , 0 , 0
     -10    .035       0       0    .035       0    17.1    .035       0
#XS Ineff= 2 , 0
               0   81.24    17.1           80.84
Permanent Ineff=
       F       F
Bank Sta=0,17.1
XS Rating Curve= 0
Exp/Cntr=.3,.1

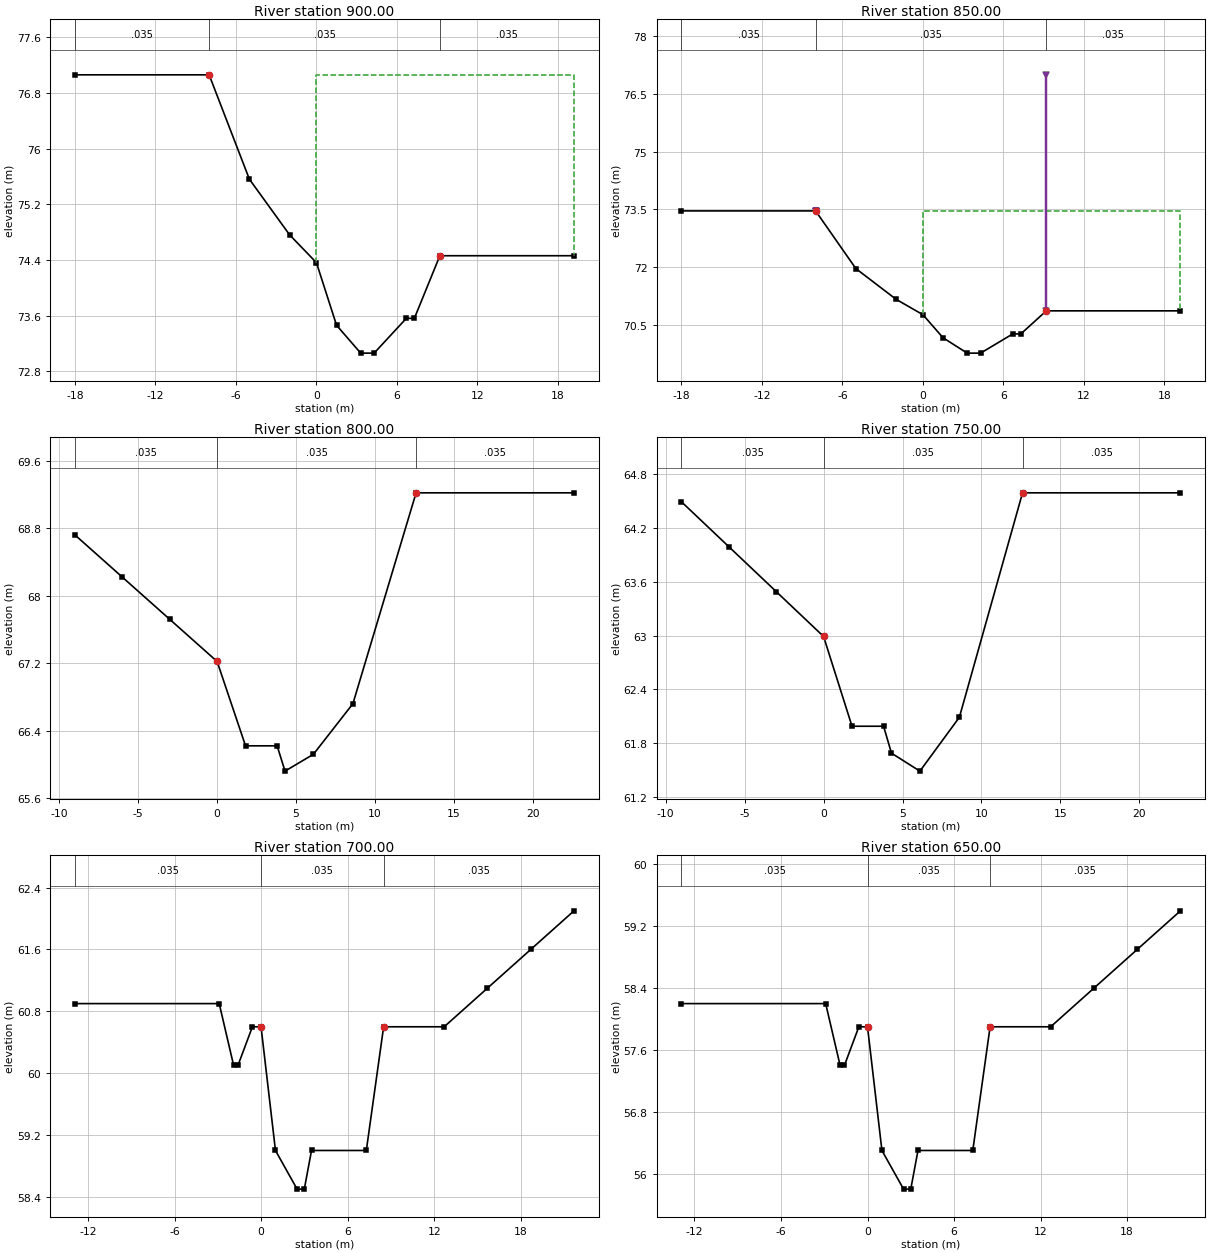
Type RM Length L Ch R = 1 ,900.00  ,50,50,50
BEGIN DESCRIPTION:
18
END DESCRIPTION:
#Sta/Elev= 12
     -18   77.06      -8   77.06      -5   75.56      -2   74.76       0   74.36
     1.5   73.46     3.3   73.06     4.3   73.06     6.7   73.56     7.3   73.56
     9.2   74.46    19.2   74.46
#Mann= 3 , 0 , 0
     -18    .035       0      -8    .035       0     9.2    .035       0
#XS Ineff= 2 , 0
       0      -8   77.06     9.2       0   74.46
Permanent Ineff=
       F       F
Bank Sta=-8,9.2
XS Rating Curve= 0
Exp/Cntr=.3,.1

Type RM Length L Ch R = 1 ,850.00  ,50,50,50
BEGIN DESCRIPTION:
17
END DESCRIPTION:
#Sta/Elev= 12
     -18   73.46      -8   73.46      -5   71.96      -2   71.16       0   70.76
     1.5   70.16     3.3   69.76     4.3   69.76     6.7   70.26     7.3   70.26
     9.2   70.86    19.2   70.86
#Mann= 3 , 0 , 0
     -18    .035       0      -8    .035       0     9.2    .035       0
Levee=-1,-8,73.46,-1,9.2,77,,
#XS Ineff= 2 , 0
       0      -8   73.46     9.2       0   70.86
Permanent Ineff=
       F       F
Bank Sta=-8,9.2
XS Rating Curve= 0
Exp/Cntr=.3,.1

Type RM Length L Ch R = 1 ,800.00  ,50,50,50
BEGIN DESCRIPTION:
16
END DESCRIPTION:
#Sta/Elev= 11
      -9   68.72      -6   68.22      -3   67.72       0   67.22     1.8   66.22
     3.8   66.22     4.3   65.92     6.1   66.12     8.6   66.72    12.6   69.22
    22.6   69.22
#Mann= 3 , 0 , 0
      -9    .035       0       0    .035       0    12.6    .035       0
#XS Ineff= 2 , 0
               0   67.22    12.6           69.22
Permanent Ineff=
       F       F
Bank Sta=0,12.6
XS Rating Curve= 0
Exp/Cntr=.3,.1

Type RM Length L Ch R = 1 ,750.00  ,50,50,50
BEGIN DESCRIPTION:
15
END DESCRIPTION:
#Sta/Elev= 11
      -9   64.49      -6   63.99      -3   63.49       0   62.99     1.8   61.99
     3.8   61.99     4.3   61.69     6.1   61.49     8.6   62.09    12.6   64.59
    22.6   64.59
#Mann= 3 , 0 , 0
      -9    .035       0       0    .035       0    12.6    .035       0
#XS Ineff= 2 , 0
               0   62.99    12.6           64.59
Permanent Ineff=
       F       F
Bank Sta=0,12.6
XS Rating Curve= 0
Exp/Cntr=.3,.1

Type RM Length L Ch R = 1 ,700.00  ,50,50,50
BEGIN DESCRIPTION:
14
END DESCRIPTION:
#Sta/Elev= 16
   -12.9    60.9    -2.9    60.9    -1.9    60.1    -1.6    60.1     -.6    60.6
       0    60.6       1      59     2.5    58.5       3    58.5     3.5      59
     7.3      59     8.5    60.6    12.7    60.6    15.7    61.1    18.7    61.6
    21.7    62.1
#Mann= 3 , 0 , 0
   -12.9    .035       0       0    .035       0     8.5    .035       0
#XS Ineff= 2 , 0
               0    60.6     8.5            60.6
Permanent Ineff=
       F       F
Bank Sta=0,8.5
XS Rating Curve= 0
Exp/Cntr=.3,.1

Type RM Length L Ch R = 1 ,650.00  ,13,13,13
BEGIN DESCRIPTION:
13
END DESCRIPTION:
#Sta/Elev= 16
   -12.9    58.2    -2.9    58.2    -1.9    57.4    -1.6    57.4     -.6    57.9
       0    57.9       1    56.3     2.5    55.8       3    55.8     3.5    56.3
     7.3    56.3     8.5    57.9    12.7    57.9    15.7    58.4    18.7    58.9
    21.7    59.4
#Mann= 3 , 0 , 0
   -12.9    .035       0       0    .035       0     8.5    .035       0
#XS Ineff= 2 , 0
               0    57.9     8.5            57.9
Permanent Ineff=
       F       F
Bank Sta=0,8.5
XS Rating Curve= 0
Exp/Cntr=.3,.1

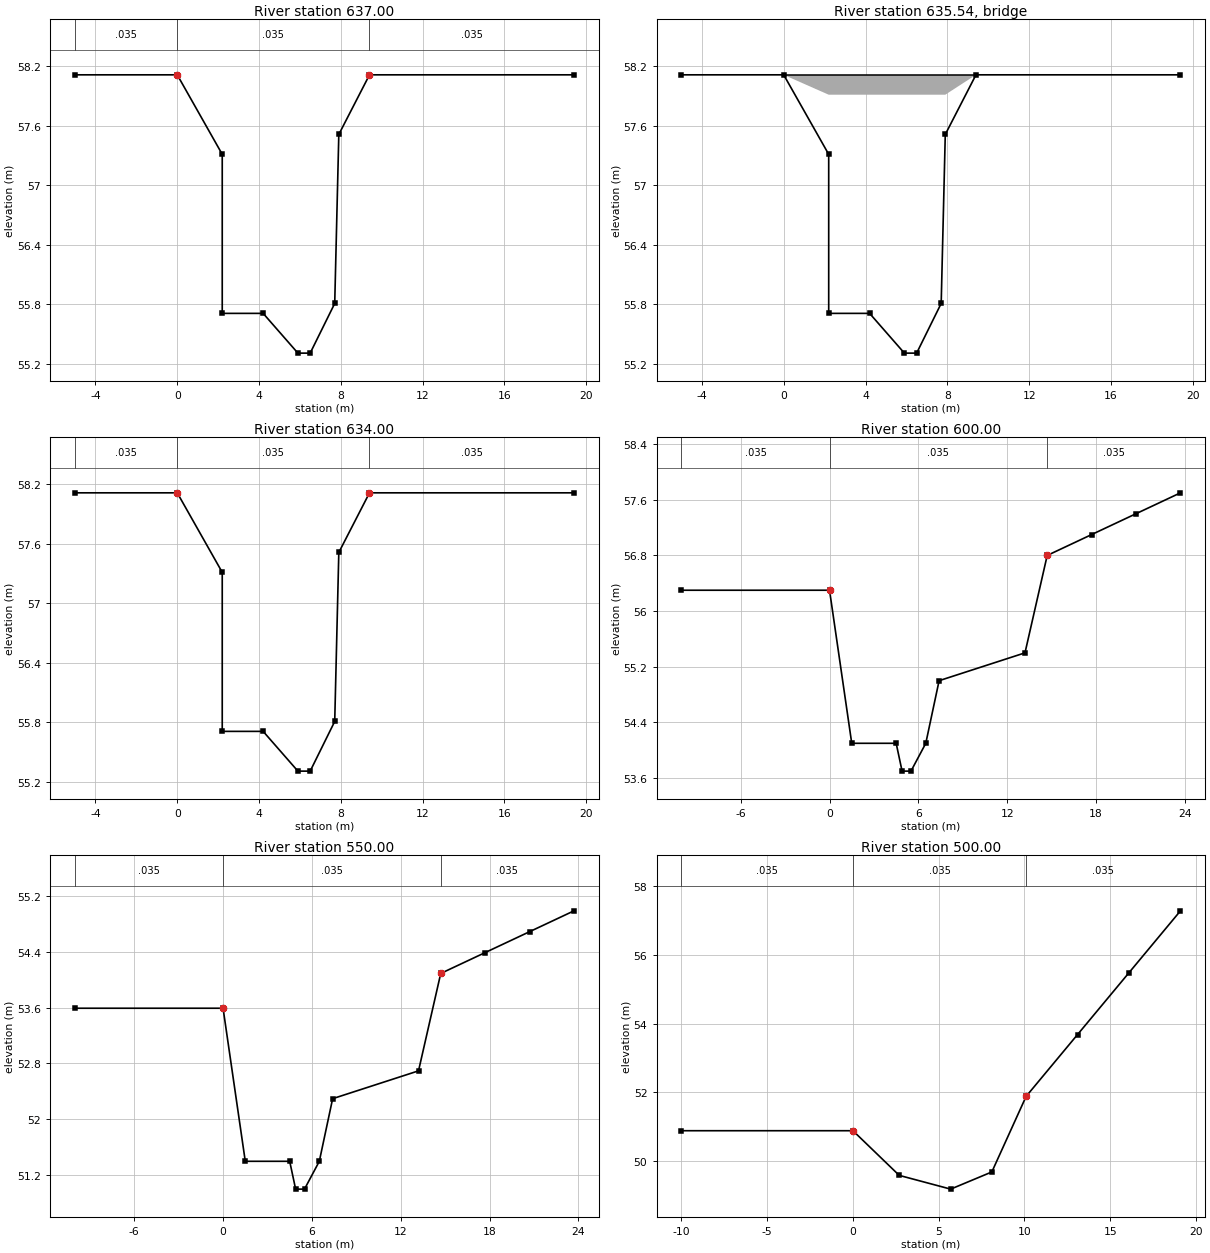
Type RM Length L Ch R = 1 ,637.00  ,3,3,3
BEGIN DESCRIPTION:
12.037
END DESCRIPTION:
#Sta/Elev= 11
      -5   58.11       0   58.11     2.2   57.31     2.2   55.71     4.2   55.71
     5.9   55.31     6.5   55.31     7.7   55.81     7.9   57.51     9.4   58.11
    19.4   58.11
#Mann= 3 , 0 , 0
      -5    .035       0       0    .035       0     9.4    .035       0
#XS Ineff= 2 , 0
       0       0   58.11     9.4       0   58.11
Permanent Ineff=
       F       F
Bank Sta=0,9.4
XS Rating Curve= 0
Exp/Cntr=.3,.1

Type RM Length L Ch R = 3 ,635.54  ,,,
BEGIN DESCRIPTION:
12.0355
END DESCRIPTION:
Bridge Culvert--1,0,-1,-1, 0
Deck Dist Width WeirC Skew NumUp NumDn MinLoCord MaxHiCord MaxSubmerge Is_Ogee
.01,2.9,1.44,0, 2, 2, , , .95, 0, 0,0,,
       0     9.4
   58.11   58.11
   57.91   57.91
       0     9.4
   58.11   58.11
   57.91   57.91
BR Coef=-1 , 1 , 0 ,, 0 ,,,.8,-1,1.2,0,
WSPro=,,,, 1 ,,,, 0 ,,,, 0 ,,,,-1 ,-1 ,-1 , 0 , 0 , 0 , 0 , 0
BC Design=,, 0 ,, 0 ,,,,,,

Type RM Length L Ch R = 1 ,634.00  ,34,34,34
BEGIN DESCRIPTION:
12.034
END DESCRIPTION:
#Sta/Elev= 11
      -5   58.11       0   58.11     2.2   57.31     2.2   55.71     4.2   55.71
     5.9   55.31     6.5   55.31     7.7   55.81     7.9   57.51     9.4   58.11
    19.4   58.11
#Mann= 3 , 0 , 0
      -5    .035       0       0    .035       0     9.4    .035       0
#XS Ineff= 2 , 0
       0       0   58.11     9.4       0   58.11
Permanent Ineff=
       F       F
Bank Sta=0,9.4
XS Rating Curve= 0
Exp/Cntr=.3,.1

Type RM Length L Ch R = 1 ,600.00  ,50,50,50
BEGIN DESCRIPTION:
12
END DESCRIPTION:
#Sta/Elev= 13
     -10    56.3       0    56.3     1.5    54.1     4.5    54.1     4.9    53.7
     5.5    53.7     6.5    54.1     7.4      55    13.2    55.4    14.7    56.8
    17.7    57.1    20.7    57.4    23.7    57.7
#Mann= 3 , 0 , 0
     -10    .035       0       0    .035       0    14.7    .035       0
#XS Ineff= 2 , 0
               0    56.3    14.7            56.8
Permanent Ineff=
       F       F
Bank Sta=0,14.7
XS Rating Curve= 0
Exp/Cntr=.3,.1

Type RM Length L Ch R = 1 ,550.00  ,50,50,50
BEGIN DESCRIPTION:
11
END DESCRIPTION:
#Sta/Elev= 13
     -10   53.59       0   53.59     1.5   51.39     4.5   51.39     4.9   50.99
     5.5   50.99     6.5   51.39     7.4   52.29    13.2   52.69    14.7   54.09
    17.7   54.39    20.7   54.69    23.7   54.99
#Mann= 3 , 0 , 0
     -10    .035       0       0    .035       0    14.7    .035       0
#XS Ineff= 2 , 0
               0   53.59    14.7           54.09
Permanent Ineff=
       F       F
Bank Sta=0,14.7
XS Rating Curve= 0
Exp/Cntr=.3,.1

Type RM Length L Ch R = 1 ,500.00  ,50,50,50
BEGIN DESCRIPTION:
10
END DESCRIPTION:
#Sta/Elev= 9
     -10   50.88       0   50.88     2.7   49.58     5.7   49.18     8.1   49.68
    10.1   51.88    13.1   53.68    16.1   55.48    19.1   57.28
#Mann= 3 , 0 , 0
     -10    .035       0       0    .035       0    10.1    .035       0
#XS Ineff= 2 , 0
               0   50.88    10.1           51.88
Permanent Ineff=
       F       F
Bank Sta=0,10.1
XS Rating Curve= 0
Exp/Cntr=.3,.1

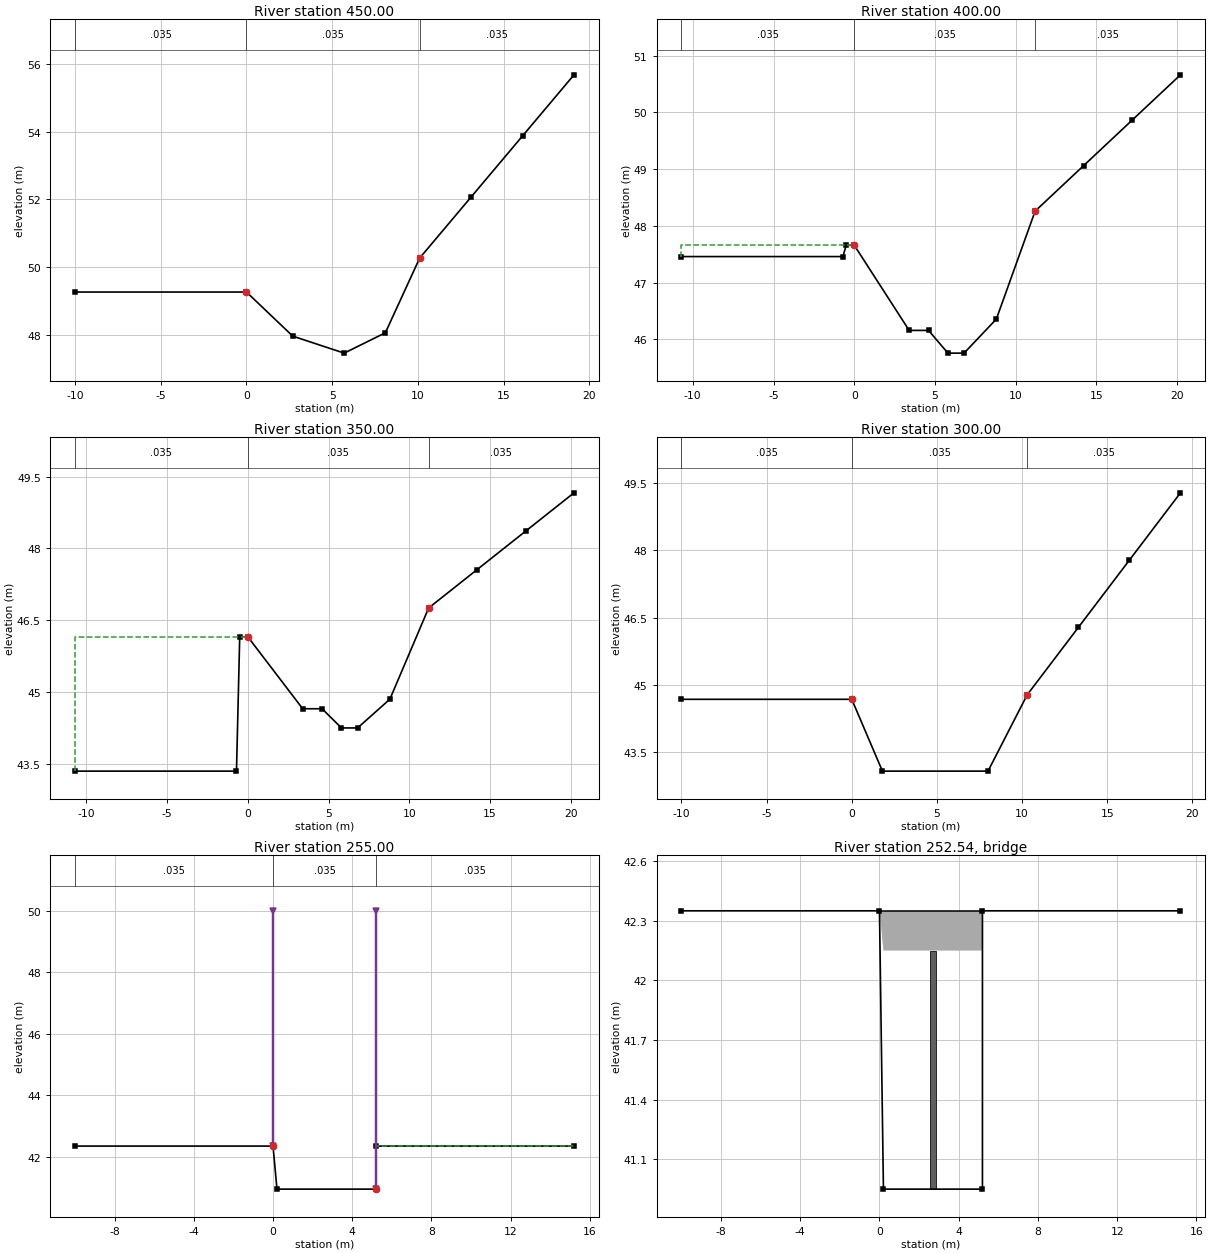
Type RM Length L Ch R = 1 ,450.00  ,50,50,50
BEGIN DESCRIPTION:
9
END DESCRIPTION:
#Sta/Elev= 9
     -10   49.27       0   49.27     2.7   47.97     5.7   47.47     8.1   48.07
    10.1   50.27    13.1   52.07    16.1   53.87    19.1   55.67
#Mann= 3 , 0 , 0
     -10    .035       0       0    .035       0    10.1    .035       0
#XS Ineff= 2 , 0
               0   49.27    10.1           50.27
Permanent Ineff=
       F       F
Bank Sta=0,10.1
XS Rating Curve= 0
Exp/Cntr=.3,.1

Type RM Length L Ch R = 1 ,400.00  ,50,50,50
BEGIN DESCRIPTION:
8
END DESCRIPTION:
#Sta/Elev= 13
   -10.7   47.46     -.7   47.46     -.5   47.66       0   47.66     3.4   46.16
     4.6   46.16     5.8   45.76     6.8   45.76     8.8   46.36    11.2   48.26
    14.2   49.06    17.2   49.86    20.2   50.66
#Mann= 3 , 0 , 0
   -10.7    .035       0       0    .035       0    11.2    .035       0
#XS Ineff= 2 , 0
               0   47.66    11.2           48.26
Permanent Ineff=
       F       F
Bank Sta=0,11.2
XS Rating Curve= 0
Exp/Cntr=.3,.1

Type RM Length L Ch R = 1 ,350.00  ,50,50,50
BEGIN DESCRIPTION:
7
END DESCRIPTION:
#Sta/Elev= 13
   -10.7   43.36     -.7   43.36     -.5   46.16       0   46.16     3.4   44.66
     4.6   44.66     5.8   44.26     6.8   44.26     8.8   44.86    11.2   46.76
    14.2   47.56    17.2   48.36    20.2   49.16
#Mann= 3 , 0 , 0
   -10.7    .035       0       0    .035       0    11.2    .035       0
#XS Ineff= 2 , 0
               0   46.16    11.2           46.76
Permanent Ineff=
       F       F
Bank Sta=0,11.2
XS Rating Curve= 0
Exp/Cntr=.3,.1

Type RM Length L Ch R = 1 ,300.00  ,45,45,45
BEGIN DESCRIPTION:
6
END DESCRIPTION:
#Sta/Elev= 8
     -10   44.68       0   44.68     1.8   43.08       8   43.08    10.3   44.78
    13.3   46.28    16.3   47.78    19.3   49.28
#Mann= 3 , 0 , 0
     -10    .035       0       0    .035       0    10.3    .035       0
#XS Ineff= 2 , 0
               0   44.68    10.3           44.78
Permanent Ineff=
       F       F
Bank Sta=0,10.3
XS Rating Curve= 0
Exp/Cntr=.3,.1

Type RM Length L Ch R = 1 ,255.00  ,5,5,5
BEGIN DESCRIPTION:
5.005
END DESCRIPTION:
#Sta/Elev= 6
     -10   42.35       0   42.35      .2   40.95     5.2   40.95     5.2   42.35
    15.2   42.35
#Mann= 3 , 0 , 0
     -10    .035       0       0    .035       0     5.2    .035       0
Levee=-1,0,50,-1,5.2,50,,
#XS Ineff= 2 , 0
               0   42.35     5.2           42.35
Permanent Ineff=
       F       F
Bank Sta=0,5.2
XS Rating Curve= 0
Exp/Cntr=.3,.1

Type RM Length L Ch R = 3 ,252.54  ,,,
BEGIN DESCRIPTION:
5.0025
END DESCRIPTION:
Bridge Culvert--1,0,-1,-1, 0
Deck Dist Width WeirC Skew NumUp NumDn MinLoCord MaxHiCord MaxSubmerge Is_Ogee
.01,4.9,1.44,0, 2, 2, , , .95, 0, 0,0,,
       0     5.2
   42.35   42.35
   42.15   42.15
       0     5.2
   42.25   42.25
   42.05   42.05
Pier Skew, UpSta & Num, DnSta & Num=  ,2.7, 2 ,2.7, 2 , 0 , 0 , 0 ,,
      .3      .3
   40.95   42.35
      .3      .3
   40.55   42.25
BR Coef=-1 , 1 , 1 ,.9, 0 ,,,.8,-1,1.2,0,
WSPro=,,,, 1 ,,,, 0 ,,,, 0 ,,,,-1 ,-1 ,-1 , 0 , 0 , 0 , 0 , 0
BC Design=,, 0 ,, 0 ,,,,,,

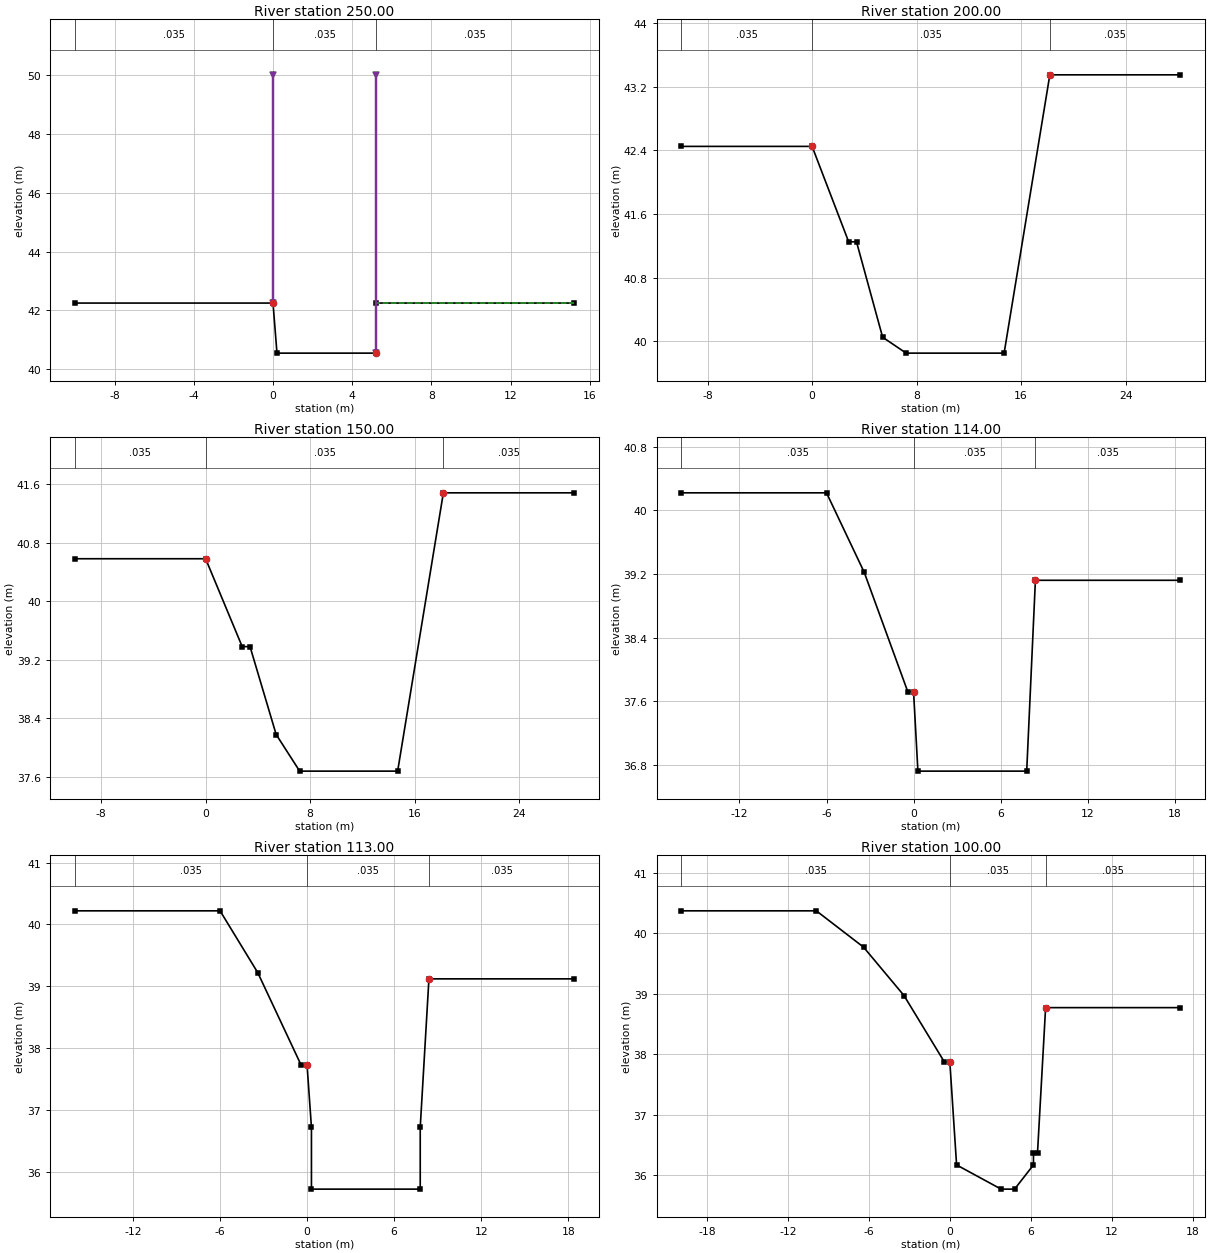
Type RM Length L Ch R = 1 ,250.00  ,50,50,50
BEGIN DESCRIPTION:
5
END DESCRIPTION:
#Sta/Elev= 6
     -10   42.25       0   42.25      .2   40.55     5.2   40.55     5.2   42.25
    15.2   42.25
#Mann= 3 , 0 , 0
     -10    .035       0       0    .035       0     5.2    .035       0
Levee=-1,0,50,-1,5.2,50,,
#XS Ineff= 2 , 0
               0   42.25     5.2           42.25
Permanent Ineff=
       F       F
Bank Sta=0,5.2
XS Rating Curve= 0
Exp/Cntr=.3,.1

Type RM Length L Ch R = 1 ,200.00  ,50,50,50
BEGIN DESCRIPTION:
4
END DESCRIPTION:
#Sta/Elev= 9
     -10   42.45       0   42.45     2.8   41.25     3.4   41.25     5.4   40.05
     7.2   39.85    14.7   39.85    18.2   43.35    28.2   43.35
#Mann= 3 , 0 , 0
     -10    .035       0       0    .035       0    18.2    .035       0
#XS Ineff= 2 , 0
               0   42.45    18.2           43.35
Permanent Ineff=
       F       F
Bank Sta=0,18.2
XS Rating Curve= 0
Exp/Cntr=.3,.1

Type RM Length L Ch R = 1 ,150.00  ,36,36,36
BEGIN DESCRIPTION:
3
END DESCRIPTION:
#Sta/Elev= 9
     -10   40.58       0   40.58     2.8   39.38     3.4   39.38     5.4   38.18
     7.2   37.68    14.7   37.68    18.2   41.48    28.2   41.48
#Mann= 3 , 0 , 0
     -10    .035       0       0    .035       0    18.2    .035       0
#XS Ineff= 2 , 0
               0   40.58    18.2           41.48
Permanent Ineff=
       F       F
Bank Sta=0,18.2
XS Rating Curve= 0
Exp/Cntr=.3,.1

Type RM Length L Ch R = 1 ,114.00  ,1,1,1
BEGIN DESCRIPTION:
2.014
END DESCRIPTION:
#Sta/Elev= 9
     -16   40.22      -6   40.22    -3.4   39.22     -.4   37.72       0   37.72
      .3   36.72     7.8   36.72     8.4   39.12    18.4   39.12
#Mann= 3 , 0 , 0
     -16    .035       0       0    .035       0     8.4    .035       0
#XS Ineff= 2 , 0
               0   37.72     8.4           39.12
Permanent Ineff=
       F       F
Bank Sta=0,8.4
XS Rating Curve= 0
Exp/Cntr=.3,.1

Type RM Length L Ch R = 1 ,113.00  ,13,13,13
BEGIN DESCRIPTION:
2.013
END DESCRIPTION:
#Sta/Elev= 11
     -16   40.22      -6   40.22    -3.4   39.22     -.4   37.72       0   37.72
      .3   36.72      .3   35.72     7.8   35.72     7.8   36.72     8.4   39.12
    18.4   39.12
#Mann= 3 , 0 , 0
     -16    .035       0       0    .035       0     8.4    .035       0
#XS Ineff= 2 , 0
               0   37.72     8.4           39.12
Permanent Ineff=
       F       F
Bank Sta=0,8.4
XS Rating Curve= 0
Exp/Cntr=.3,.1

Type RM Length L Ch R = 1 ,100.00  ,50,50,50
BEGIN DESCRIPTION:
2
END DESCRIPTION:
#Sta/Elev= 14
   -19.9   40.37    -9.9   40.37    -6.4   39.77    -3.4   38.97     -.4   37.87
       0   37.87      .5   36.17     3.8   35.77     4.8   35.77     6.2   36.17
     6.2   36.37     6.5   36.37     7.1   38.77    17.1   38.77
#Mann= 3 , 0 , 0
   -19.9    .035       0       0    .035       0     7.1    .035       0
#XS Ineff= 2 , 0
               0   37.87     7.1           38.77
Permanent Ineff=
       F       F
Bank Sta=0,7.1
XS Rating Curve= 0
Exp/Cntr=.3,.1

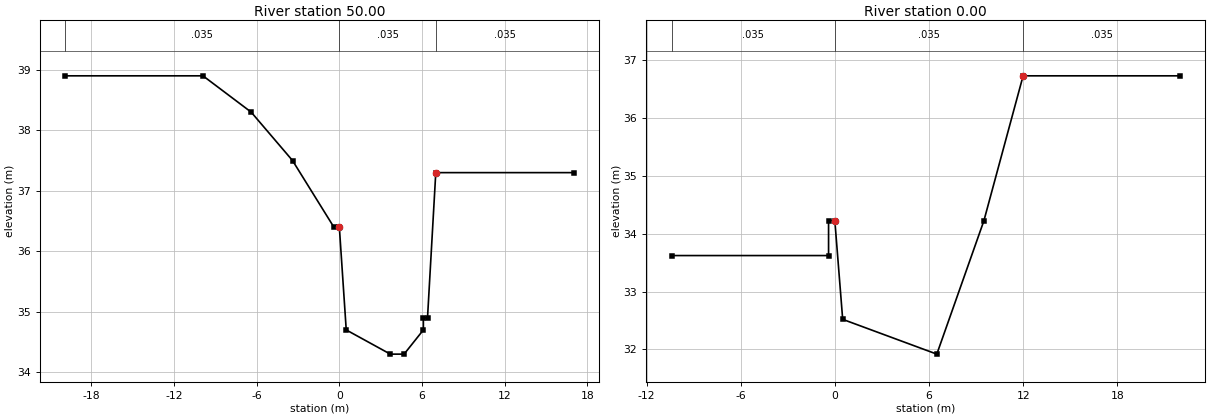
Type RM Length L Ch R = 1 ,50.00   ,50,50,50
BEGIN DESCRIPTION:
1
END DESCRIPTION:
#Sta/Elev= 14
   -19.9    38.9    -9.9    38.9    -6.4    38.3    -3.4    37.5     -.4    36.4
       0    36.4      .5    34.7     3.7    34.3     4.7    34.3     6.1    34.7
     6.1    34.9     6.4    34.9       7    37.3      17    37.3
#Mann= 3 , 0 , 0
   -19.9    .035       0       0    .035       0       7    .035       0
#XS Ineff= 2 , 0
               0    36.4       7            37.3
Permanent Ineff=
       F       F
Bank Sta=0,7
XS Rating Curve= 0
Exp/Cntr=.3,.1

Type RM Length L Ch R = 1 ,0.00    ,0,0,0
BEGIN DESCRIPTION:
0
END DESCRIPTION:
#Sta/Elev= 9
   -10.4   33.62     -.4   33.62     -.4   34.22       0   34.22      .5   32.52
     6.5   31.92     9.5   34.22      12   36.72      22   36.72
#Mann= 3 , 0 , 0
   -10.4    .035       0       0    .035       0      12    .035       0
#XS Ineff= 2 , 0
       0       0   34.22      12       0   36.72
Permanent Ineff=
       F       F
Bank Sta=0,12
XS Rating Curve= 0
Exp/Cntr=.3,.1

Chan Stop Cuts=-1