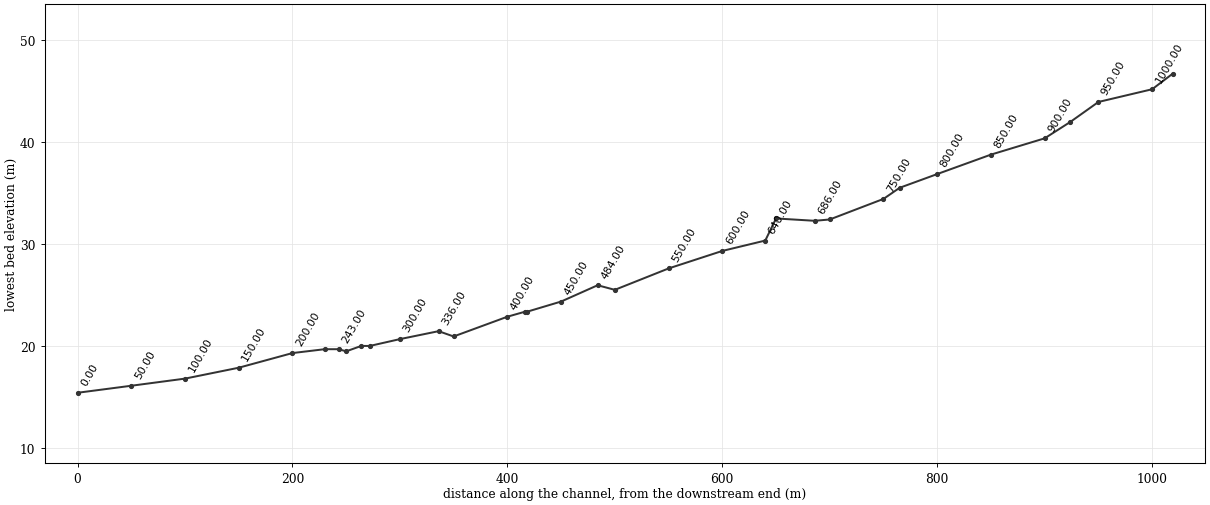
--- bac.prj (project) ---

Proj Title=buan-ch
Current Plan=p01
Default Exp/Contr=.3,.1
SI Units
Geom File=g01
Flow File=f01
Plan File=p01
Y Axis Title=Elevation
X Axis Title(PF)=Main Channel Distance
X Axis Title(XS)=Station
BEGIN DESCRIPTION:
           BACK WATER COMPUTATION
      APPLICATION OF HEC-2 BY Samju Construction Engineering
      ºÎ¾ÈÃµ(¿ËÃµÀ¾): 30,50,80,100,150³âºóµµ °³¼öÀü
END DESCRIPTION:
DSS Export Rating Curves= 0
DSS Export Rating Curve Sorted= 0
DSS Export Volume Flow Curves= 0
DXF OffsetX= 0
DXF OffsetY= 0
DXF ScaleX= 1
DXF ScaleY= 10

--- bac.p01 (plan) ---

Plan Title=Imported Plan 01
Version=Version 3.0.1  Mar 2001
Short Identifier=Imported Pla
Geom File=g01
Flow File=f01
Subcritical Flow
K Sum by GR= 0
Std Step Tol= 0.003
Critical Tol= 0.003
Num of Std Step Trials= 20
Max Error Tol= 0.1
Flow Tol Ratio= 0.001
Split Flow NTrial= 30
Split Flow Tol= 0.02
Split Flow Ratio= 0.02
Log Output Level= 0
Friction Slope Method= 1
Unsteady Friction Slope Method= 2
Parabolic Critical Depth
Global Vel Dist= 0 , 0 , 0
Global Log Level= 0
CheckData=True
Encroach Param=-1 ,0,0, 0
Computation Interval=1HOUR
Output Interval=1HOUR
Run HTab= 0
Run UNet= 0
Run PostProcess= 0
UNET Theta= 1
UNET ZTol= 0.02
UNET ZSATol= 0.1
UNET MxIter= 20
UNET MaxInSteps= 20
UNET DtIC= 0
UNET DtMin= 0
UNET MaxCRTS= 20
UNET WFStab= 2
UNET SFStab= 1
UNET WFX= 1
UNET SFX= 1
UNET Convert EG Bridges=-1
UNET Use Existing IB Tables=-1
Instantaneous Interval=1HOUR
Write IC File= 0
Write Velocity= 0
Write Detailed= 0

--- bac.f01 (steady flow) ---

Flow Title=Imported Flow 01
Version=Version 3.0.1  Mar 2001
Number of Profiles= 5
Profile Names=10yr,20yr,30yr,50yr,80yr
River Rch & RM=RIVER-1,Reach-1         ,20.019
   15.06   16.59   17.49   18.62   19.66
River Rch & RM=buan,buan            ,1019.00
   15.06   16.59   17.49   18.62   19.66
Boundary for River Rch & Prof#=buan,buan            , 1
Up Type= 0
Dn Type= 3
Dn Slope=.031
Boundary for River Rch & Prof#=buan,buan            , 2
Up Type= 0
Dn Type= 3
Dn Slope=.031
Boundary for River Rch & Prof#=buan,buan            , 3
Up Type= 0
Dn Type= 3
Dn Slope=.031
Boundary for River Rch & Prof#=buan,buan            , 4
Up Type= 0
Dn Type= 3
Dn Slope=.031
Boundary for River Rch & Prof#=buan,buan            , 5
Up Type= 0
Dn Type= 3
Dn Slope=.031
DSS Import GetInterval= 0
DSS Import GetPeak= 0
DSS Import FillOption= 0

--- bac.g01 (geometry) ---

Geom Title=Imported Geom 01
Version=Version 3.0.1  Mar 2001

River Reach=buan            ,buan
Reach XY= 2
              .5             .95              .5             .05

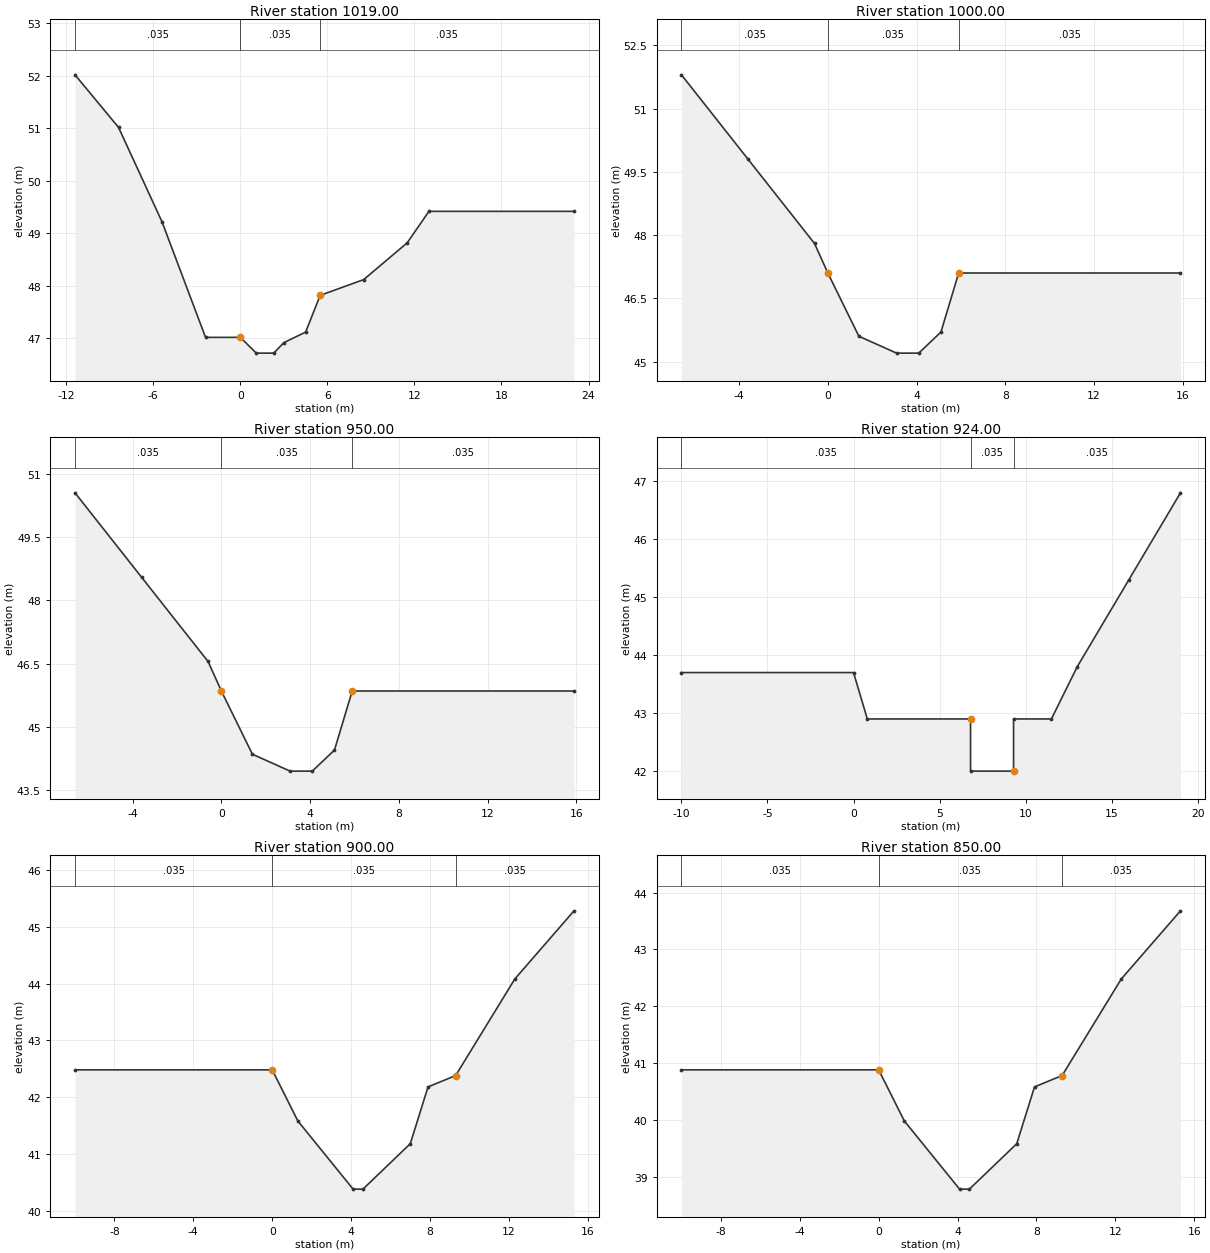
Type RM Length L Ch R = 1 ,1019.00 ,19,19,19
BEGIN DESCRIPTION:
20.019
END DESCRIPTION:
#Sta/Elev= 14
   -11.4   52.02    -8.4   51.02    -5.4   49.22    -2.4   47.02       0   47.02
     1.1   46.72     2.3   46.72       3   46.92     4.5   47.12     5.5   47.82
     8.5   48.12    11.5   48.82      13   49.42      23   49.42
#Mann= 3 , 0 , 0
   -11.4    .035       0       0    .035       0     5.5    .035       0
#XS Ineff= 2 , 0
               0   47.02     5.5           47.82
Permanent Ineff=
       F       F
Bank Sta=0,5.5
XS Rating Curve= 0
Exp/Cntr=.3,.1

Type RM Length L Ch R = 1 ,1000.00 ,50,50,50
BEGIN DESCRIPTION:
20
END DESCRIPTION:
#Sta/Elev= 10
    -6.6    51.8    -3.6    49.8     -.6    47.8       0    47.1     1.4    45.6
     3.1    45.2     4.1    45.2     5.1    45.7     5.9    47.1    15.9    47.1
#Mann= 3 , 0 , 0
    -6.6    .035       0       0    .035       0     5.9    .035       0
#XS Ineff= 2 , 0
               0    47.1     5.9            47.1
Permanent Ineff=
       F       F
Bank Sta=0,5.9
XS Rating Curve= 0
Exp/Cntr=.3,.1

Type RM Length L Ch R = 1 ,950.00  ,26,26,26
BEGIN DESCRIPTION:
19
END DESCRIPTION:
#Sta/Elev= 10
    -6.6   50.55    -3.6   48.55     -.6   46.55       0   45.85     1.4   44.35
     3.1   43.95     4.1   43.95     5.1   44.45     5.9   45.85    15.9   45.85
#Mann= 3 , 0 , 0
    -6.6    .035       0       0    .035       0     5.9    .035       0
#XS Ineff= 2 , 0
               0   45.85     5.9           45.85
Permanent Ineff=
       F       F
Bank Sta=0,5.9
XS Rating Curve= 0
Exp/Cntr=.3,.1

Type RM Length L Ch R = 1 ,924.00  ,24,24,24
BEGIN DESCRIPTION:
18.024
END DESCRIPTION:
#Sta/Elev= 11
     -10    43.7       0    43.7      .8    42.9     6.8    42.9     6.8      42
     9.3      42     9.3    42.9    11.5    42.9      13    43.8      16    45.3
      19    46.8
#Mann= 3 , 0 , 0
     -10    .035       0     6.8    .035       0     9.3    .035       0
#XS Ineff= 2 , 0
       0     6.8    42.9     9.3       0      42
Permanent Ineff=
       F       F
Bank Sta=6.8,9.3
XS Rating Curve= 0
Exp/Cntr=.3,.1

Type RM Length L Ch R = 1 ,900.00  ,50,50,50
BEGIN DESCRIPTION:
18
END DESCRIPTION:
#Sta/Elev= 10
     -10   42.48       0   42.48     1.3   41.58     4.1   40.38     4.6   40.38
       7   41.18     7.9   42.18     9.3   42.38    12.3   44.08    15.3   45.28
#Mann= 3 , 0 , 0
     -10    .035       0       0    .035       0     9.3    .035       0
#XS Ineff= 2 , 0
               0   42.48     9.3           42.38
Permanent Ineff=
       F       F
Bank Sta=0,9.3
XS Rating Curve= 0
Exp/Cntr=.3,.1

Type RM Length L Ch R = 1 ,850.00  ,50,50,50
BEGIN DESCRIPTION:
17
END DESCRIPTION:
#Sta/Elev= 10
     -10   40.88       0   40.88     1.3   39.98     4.1   38.78     4.6   38.78
       7   39.58     7.9   40.58     9.3   40.78    12.3   42.48    15.3   43.68
#Mann= 3 , 0 , 0
     -10    .035       0       0    .035       0     9.3    .035       0
#XS Ineff= 2 , 0
               0   40.88     9.3           40.78
Permanent Ineff=
       F       F
Bank Sta=0,9.3
XS Rating Curve= 0
Exp/Cntr=.3,.1

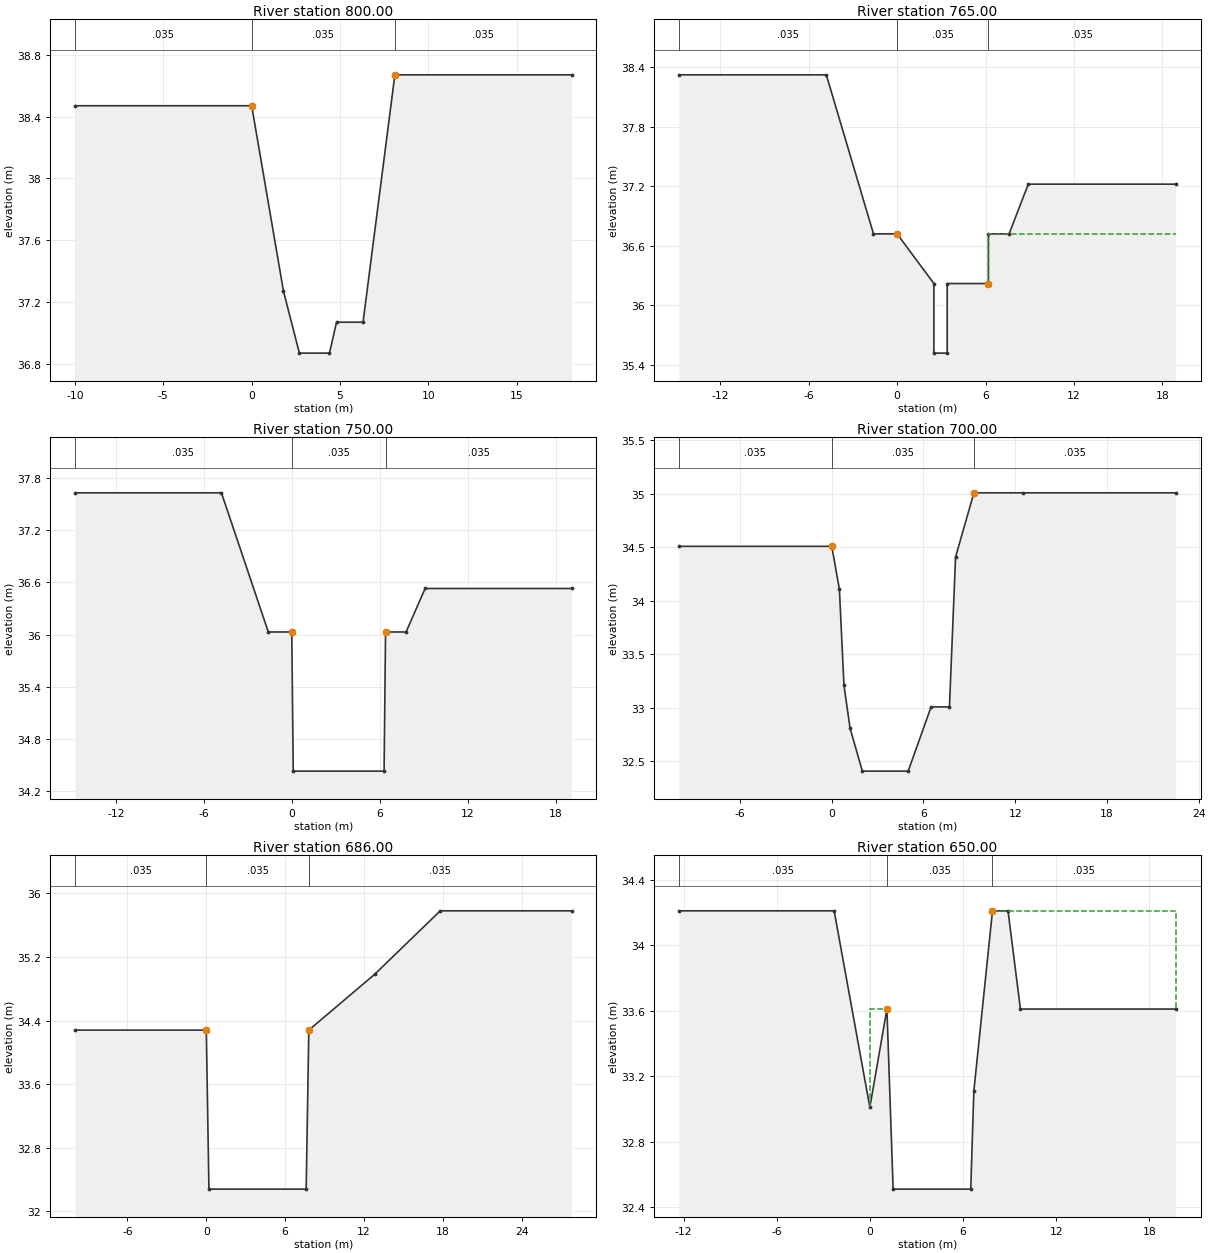
Type RM Length L Ch R = 1 ,800.00  ,35,35,35
BEGIN DESCRIPTION:
16
END DESCRIPTION:
#Sta/Elev= 9
     -10   38.47       0   38.47     1.8   37.27     2.7   36.87     4.4   36.87
     4.8   37.07     6.3   37.07     8.1   38.67    18.1   38.67
#Mann= 3 , 0 , 0
     -10    .035       0       0    .035       0     8.1    .035       0
#XS Ineff= 2 , 0
               0   38.47     8.1           38.67
Permanent Ineff=
       F       F
Bank Sta=0,8.1
XS Rating Curve= 0
Exp/Cntr=.3,.1

Type RM Length L Ch R = 1 ,765.00  ,15,15,15
BEGIN DESCRIPTION:
15.015
END DESCRIPTION:
#Sta/Elev= 13
   -14.8   38.32    -4.8   38.32    -1.6   36.72       0   36.72     2.5   36.22
     2.5   35.52     3.4   35.52     3.4   36.22     6.2   36.22     6.2   36.72
     7.6   36.72     8.9   37.22    18.9   37.22
#Mann= 3 , 0 , 0
   -14.8    .035       0       0    .035       0     6.2    .035       0
#XS Ineff= 2 , 0
               0   36.72     6.2           36.72
Permanent Ineff=
       F       F
Bank Sta=0,6.2
XS Rating Curve= 0
Exp/Cntr=.3,.1

Type RM Length L Ch R = 1 ,750.00  ,50,50,50
BEGIN DESCRIPTION:
15
END DESCRIPTION:
#Sta/Elev= 10
   -14.8   37.63    -4.8   37.63    -1.6   36.03       0   36.03      .1   34.43
     6.3   34.43     6.4   36.03     7.8   36.03     9.1   36.53    19.1   36.53
#Mann= 3 , 0 , 0
   -14.8    .035       0       0    .035       0     6.4    .035       0
#XS Ineff= 2 , 0
               0   36.03     6.4           36.03
Permanent Ineff=
       F       F
Bank Sta=0,6.4
XS Rating Curve= 0
Exp/Cntr=.3,.1

Type RM Length L Ch R = 1 ,700.00  ,14,14,14
BEGIN DESCRIPTION:
14
END DESCRIPTION:
#Sta/Elev= 13
     -10   34.51       0   34.51      .5   34.11      .8   33.21     1.2   32.81
       2   32.41       5   32.41     6.5   33.01     7.7   33.01     8.1   34.41
     9.3   35.01    12.5   35.01    22.5   35.01
#Mann= 3 , 0 , 0
     -10    .035       0       0    .035       0     9.3    .035       0
#XS Ineff= 2 , 0
               0   34.51     9.3           35.01
Permanent Ineff=
       F       F
Bank Sta=0,9.3
XS Rating Curve= 0
Exp/Cntr=.3,.1

Type RM Length L Ch R = 1 ,686.00  ,36,36,36
BEGIN DESCRIPTION:
13.036
END DESCRIPTION:
#Sta/Elev= 8
     -10   34.28       0   34.28      .2   32.28     7.6   32.28     7.8   34.28
    12.8   34.98    17.8   35.78    27.8   35.78
#Mann= 3 , 0 , 0
     -10    .035       0       0    .035       0     7.8    .035       0
#XS Ineff= 2 , 0
               0   34.28     7.8           34.28
Permanent Ineff=
       F       F
Bank Sta=0,7.8
XS Rating Curve= 0
Exp/Cntr=.3,.1

Type RM Length L Ch R = 1 ,650.00  ,10,10,10
BEGIN DESCRIPTION:
13
END DESCRIPTION:
#Sta/Elev= 11
   -12.3   34.21    -2.3   34.21       0   33.01     1.1   33.61     1.5   32.51
     6.5   32.51     6.7   33.11     7.9   34.21     8.9   34.21     9.7   33.61
    19.7   33.61
#Mann= 3 , 0 , 0
   -12.3    .035       0     1.1    .035       0     7.9    .035       0
#XS Ineff= 2 , 0
       0     1.1   33.61     7.9       0   34.21
Permanent Ineff=
       F       F
Bank Sta=1.1,7.9
XS Rating Curve= 0
Exp/Cntr=.3,.1

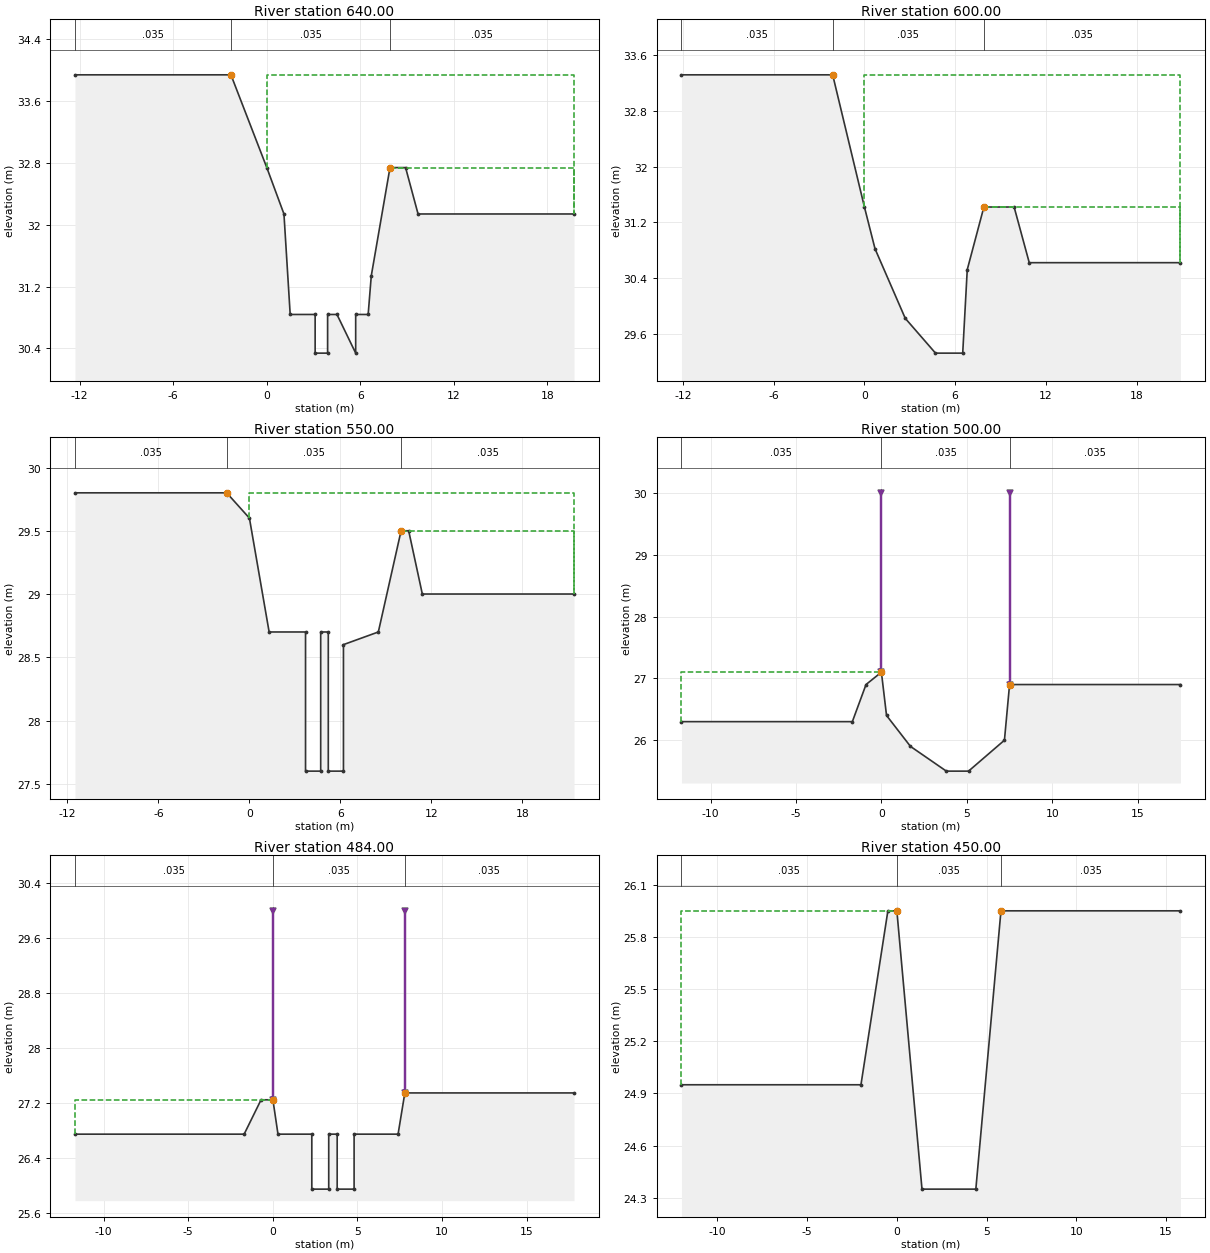
Type RM Length L Ch R = 1 ,640.00  ,40,40,40
BEGIN DESCRIPTION:
12.04
END DESCRIPTION:
#Sta/Elev= 18
   -12.3   33.94    -2.3   33.94       0   32.74     1.1   32.14     1.5   30.84
     3.1   30.84     3.1   30.34     3.9   30.34     3.9   30.84     4.5   30.84
     5.7   30.34     5.7   30.84     6.5   30.84     6.7   31.34     7.9   32.74
     8.9   32.74     9.7   32.14    19.7   32.14
#Mann= 3 , 0 , 0
   -12.3    .035       0    -2.3    .035       0     7.9    .035       0
#XS Ineff= 2 , 0
       0    -2.3   33.94     7.9       0   32.74
Permanent Ineff=
       F       F
Bank Sta=-2.3,7.9
XS Rating Curve= 0
Exp/Cntr=.3,.1

Type RM Length L Ch R = 1 ,600.00  ,50,50,50
BEGIN DESCRIPTION:
12
END DESCRIPTION:
#Sta/Elev= 12
   -12.1   33.32    -2.1   33.32       0   31.42      .7   30.82     2.7   29.82
     4.7   29.32     6.5   29.32     6.8   30.52     7.9   31.42     9.9   31.42
    10.9   30.62    20.9   30.62
#Mann= 3 , 0 , 0
   -12.1    .035       0    -2.1    .035       0     7.9    .035       0
#XS Ineff= 2 , 0
       0    -2.1   33.32     7.9       0   31.42
Permanent Ineff=
       F       F
Bank Sta=-2.1,7.9
XS Rating Curve= 0
Exp/Cntr=.3,.1

Type RM Length L Ch R = 1 ,550.00  ,50,50,50
BEGIN DESCRIPTION:
11
END DESCRIPTION:
#Sta/Elev= 17
   -11.5    29.8    -1.5    29.8       0    29.6     1.3    28.7     3.7    28.7
     3.7    27.6     4.7    27.6     4.7    28.7     5.2    28.7     5.2    27.6
     6.2    27.6     6.2    28.6     8.5    28.7      10    29.5    10.5    29.5
    11.4      29    21.4      29
#Mann= 3 , 0 , 0
   -11.5    .035       0    -1.5    .035       0      10    .035       0
#XS Ineff= 2 , 0
       0    -1.5    29.8      10       0    29.5
Permanent Ineff=
       F       F
Bank Sta=-1.5,10
XS Rating Curve= 0
Exp/Cntr=.3,.1

Type RM Length L Ch R = 1 ,500.00  ,16,16,16
BEGIN DESCRIPTION:
10
END DESCRIPTION:
#Sta/Elev= 11
   -11.7    26.3    -1.7    26.3     -.9    26.9       0    27.1      .3    26.4
     1.7    25.9     3.8    25.5     5.1    25.5     7.2      26     7.5    26.9
    17.5    26.9
#Mann= 3 , 0 , 0
   -11.7    .035       0       0    .035       0     7.5    .035       0
Levee=-1,0,30,-1,7.5,30,,
#XS Ineff= 2 , 0
               0    27.1     7.5            26.9
Permanent Ineff=
       F       F
Bank Sta=0,7.5
XS Rating Curve= 0
Exp/Cntr=.3,.1

Type RM Length L Ch R = 1 ,484.00  ,34,34,34
BEGIN DESCRIPTION:
9.034
END DESCRIPTION:
#Sta/Elev= 16
   -11.7   26.75    -1.7   26.75     -.7   27.25       0   27.25      .3   26.75
     2.3   26.75     2.3   25.95     3.3   25.95     3.3   26.75     3.8   26.75
     3.8   25.95     4.8   25.95     4.8   26.75     7.4   26.75     7.8   27.35
    17.8   27.35
#Mann= 3 , 0 , 0
   -11.7    .035       0       0    .035       0     7.8    .035       0
Levee=-1,0,30,-1,7.8,30,,
#XS Ineff= 2 , 0
               0   27.25     7.8           27.35
Permanent Ineff=
       F       F
Bank Sta=0,7.8
XS Rating Curve= 0
Exp/Cntr=.3,.1

Type RM Length L Ch R = 1 ,450.00  ,32,32,32
BEGIN DESCRIPTION:
9
END DESCRIPTION:
#Sta/Elev= 8
     -12   24.95      -2   24.95     -.5   25.95       0   25.95     1.4   24.35
     4.4   24.35     5.8   25.95    15.8   25.95
#Mann= 3 , 0 , 0
     -12    .035       0       0    .035       0     5.8    .035       0
#XS Ineff= 2 , 0
               0   25.95     5.8           25.95
Permanent Ineff=
       F       F
Bank Sta=0,5.8
XS Rating Curve= 0
Exp/Cntr=.3,.1

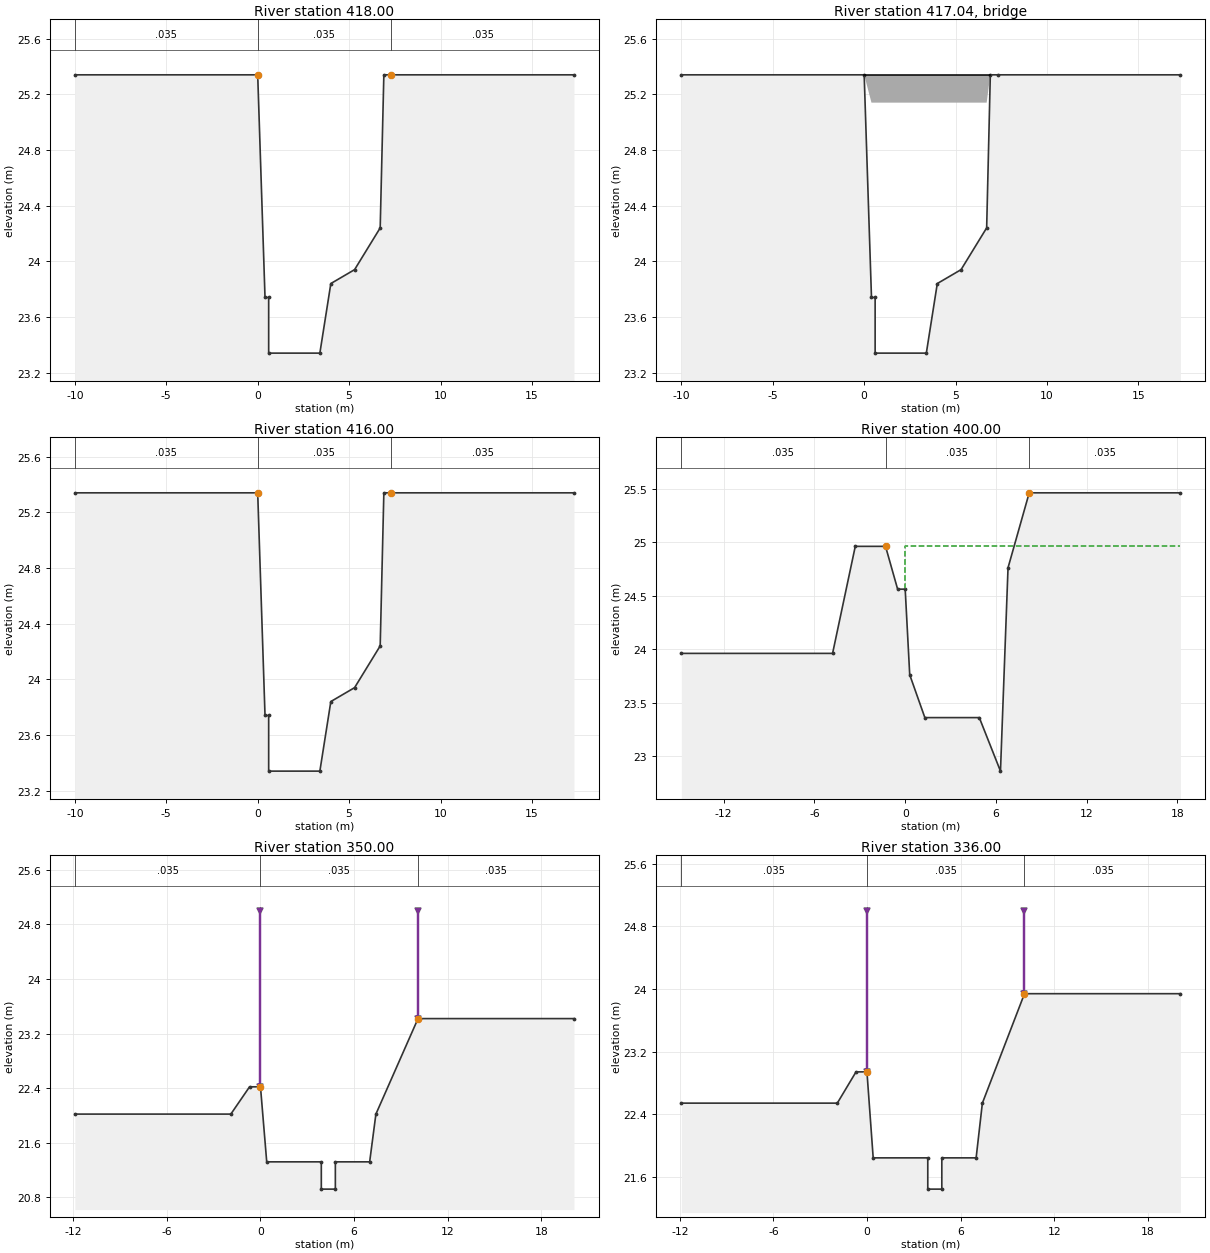
Type RM Length L Ch R = 1 ,418.00  ,2,2,2
BEGIN DESCRIPTION:
8.018
END DESCRIPTION:
#Sta/Elev= 12
     -10   25.34       0   25.34      .4   23.74      .6   23.74      .6   23.34
     3.4   23.34       4   23.84     5.3   23.94     6.7   24.24     6.9   25.34
     7.3   25.34    17.3   25.34
#Mann= 3 , 0 , 0
     -10    .035       0       0    .035       0     7.3    .035       0
#XS Ineff= 2 , 0
       0       0   25.34     7.3       0   25.34
Permanent Ineff=
       F       F
Bank Sta=0,7.3
XS Rating Curve= 0
Exp/Cntr=.3,.1

Type RM Length L Ch R = 3 ,417.04  ,,,
BEGIN DESCRIPTION:
8.017
END DESCRIPTION:
Bridge Culvert--1,0,-1,-1, 0
Deck Dist Width WeirC Skew NumUp NumDn MinLoCord MaxHiCord MaxSubmerge Is_Ogee
.01,1.9,1.44,0, 2, 2, , , .95, 0, 0,0,,
       0     6.9
   25.34   25.34
   25.14   25.14
       0     6.9
   25.34   25.34
   25.14   25.14
BR Coef=-1 , 1 , 0 ,, 0 ,,,.8,-1,1.2,0,
WSPro=,,,, 1 ,,,, 0 ,,,, 0 ,,,,-1 ,-1 ,-1 , 0 , 0 , 0 , 0 , 0
BC Design=,, 0 ,, 0 ,,,,,,

Type RM Length L Ch R = 1 ,416.00  ,16,16,16
BEGIN DESCRIPTION:
8.016
END DESCRIPTION:
#Sta/Elev= 12
     -10   25.34       0   25.34      .4   23.74      .6   23.74      .6   23.34
     3.4   23.34       4   23.84     5.3   23.94     6.7   24.24     6.9   25.34
     7.3   25.34    17.3   25.34
#Mann= 3 , 0 , 0
     -10    .035       0       0    .035       0     7.3    .035       0
#XS Ineff= 2 , 0
       0       0   25.34     7.3       0   25.34
Permanent Ineff=
       F       F
Bank Sta=0,7.3
XS Rating Curve= 0
Exp/Cntr=.3,.1

Type RM Length L Ch R = 1 ,400.00  ,50,50,50
BEGIN DESCRIPTION:
8
END DESCRIPTION:
#Sta/Elev= 13
   -14.8   23.96    -4.8   23.96    -3.3   24.96    -1.3   24.96     -.5   24.56
       0   24.56      .3   23.76     1.3   23.36     4.9   23.36     6.3   22.86
     6.8   24.76     8.2   25.46    18.2   25.46
#Mann= 3 , 0 , 0
   -14.8    .035       0    -1.3    .035       0     8.2    .035       0
#XS Ineff= 2 , 0
       0    -1.3   24.96     8.2       0   25.46
Permanent Ineff=
       F       F
Bank Sta=-1.3,8.2
XS Rating Curve= 0
Exp/Cntr=.3,.1

Type RM Length L Ch R = 1 ,350.00  ,14,14,14
BEGIN DESCRIPTION:
7
END DESCRIPTION:
#Sta/Elev= 13
   -11.9   22.02    -1.9   22.02     -.7   22.42       0   22.42      .4   21.32
     3.9   21.32     3.9   20.92     4.8   20.92     4.8   21.32       7   21.32
     7.4   22.02    10.1   23.42    20.1   23.42
#Mann= 3 , 0 , 0
   -11.9    .035       0       0    .035       0    10.1    .035       0
Levee=-1,0,25,-1,10.1,25,,
#XS Ineff= 2 , 0
       0       0   22.42    10.1       0   23.42
Permanent Ineff=
       F       F
Bank Sta=0,10.1
XS Rating Curve= 0
Exp/Cntr=.3,.1

Type RM Length L Ch R = 1 ,336.00  ,36,36,36
BEGIN DESCRIPTION:
6.036
END DESCRIPTION:
#Sta/Elev= 13
   -11.9   22.54    -1.9   22.54     -.7   22.94       0   22.94      .4   21.84
     3.9   21.84     3.9   21.44     4.8   21.44     4.8   21.84       7   21.84
     7.4   22.54    10.1   23.94    20.1   23.94
#Mann= 3 , 0 , 0
   -11.9    .035       0       0    .035       0    10.1    .035       0
Levee=-1,0,25,-1,10.1,25,,
#XS Ineff= 2 , 0
       0       0   22.94    10.1       0   23.94
Permanent Ineff=
       F       F
Bank Sta=0,10.1
XS Rating Curve= 0
Exp/Cntr=.3,.1

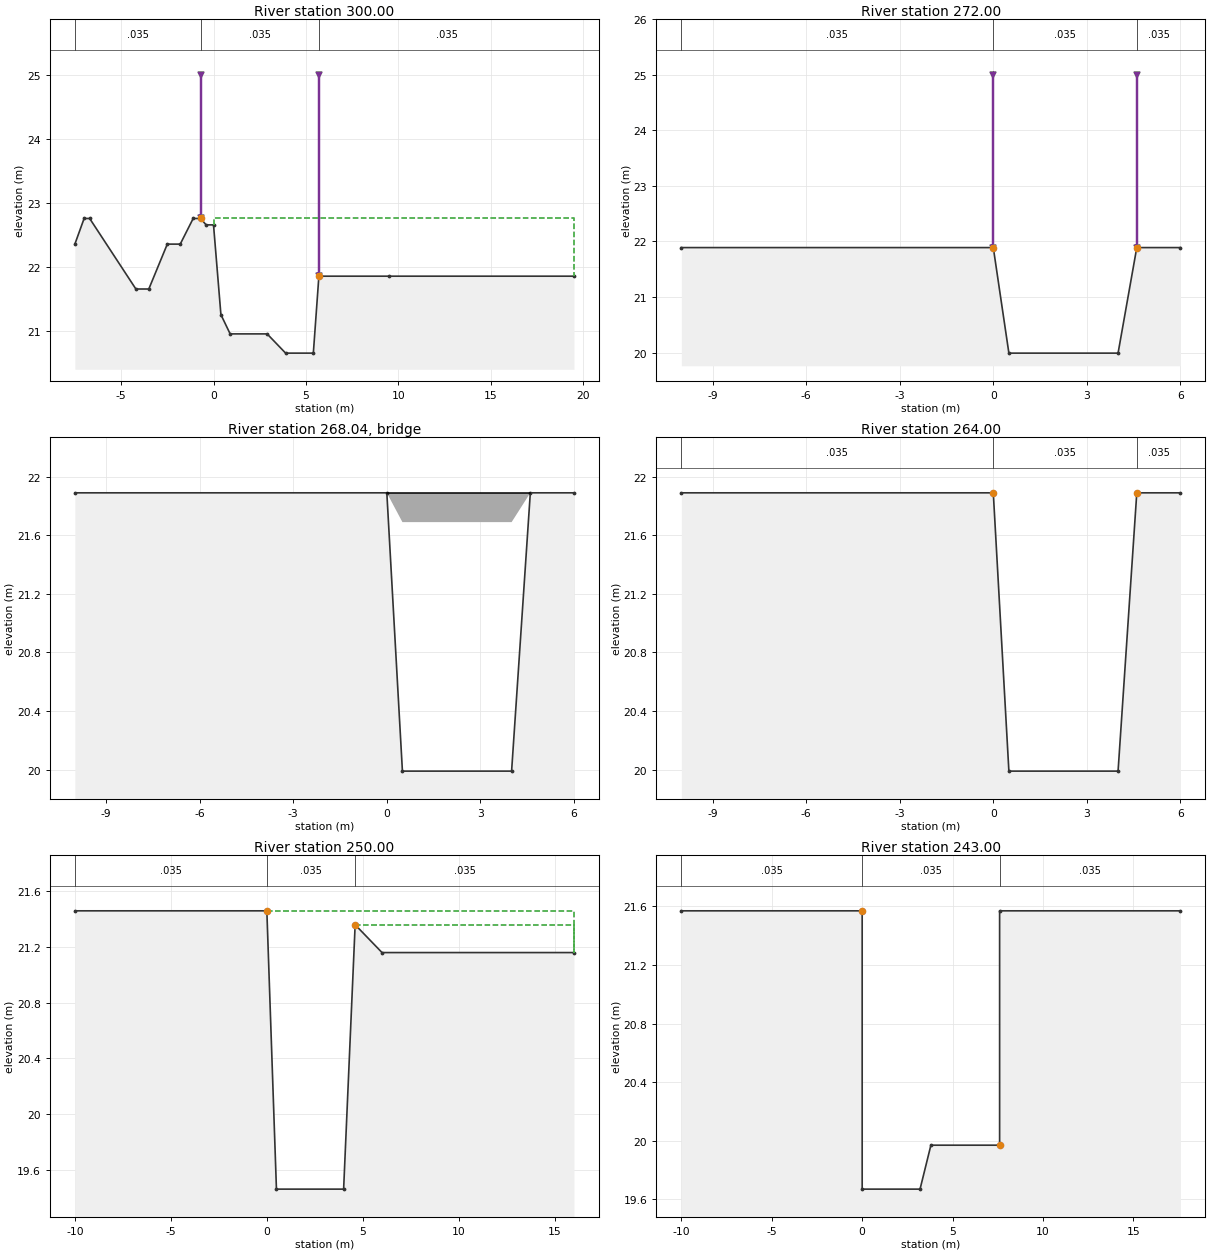
Type RM Length L Ch R = 1 ,300.00  ,28,28,28
BEGIN DESCRIPTION:
6
END DESCRIPTION:
#Sta/Elev= 19
    -7.5   22.36      -7   22.76    -6.7   22.76    -4.2   21.66    -3.5   21.66
    -2.5   22.36    -1.8   22.36    -1.1   22.76     -.7   22.76     -.4   22.66
       0   22.66      .4   21.26      .9   20.96     2.9   20.96     3.9   20.66
     5.4   20.66     5.7   21.86     9.5   21.86    19.5   21.86
#Mann= 3 , 0 , 0
    -7.5    .035       0     -.7    .035       0     5.7    .035       0
Levee=-1,-.7,25,-1,5.7,25,,
#XS Ineff= 2 , 0
       0     -.7   22.76     5.7       0   21.86
Permanent Ineff=
       F       F
Bank Sta=-.7,5.7
XS Rating Curve= 0
Exp/Cntr=.3,.1

Type RM Length L Ch R = 1 ,272.00  ,8,8,8
BEGIN DESCRIPTION:
5.022
END DESCRIPTION:
#Sta/Elev= 6
     -10   21.89       0   21.89      .5   19.99       4   19.99     4.6   21.89
       6   21.89
#Mann= 3 , 0 , 0
     -10    .035       0       0    .035       0     4.6    .035       0
Levee=-1,0,25,-1,4.6,25,,
#XS Ineff= 2 , 0
       0       0   21.89     4.6       0   21.89
Permanent Ineff=
       F       F
Bank Sta=0,4.6
XS Rating Curve= 0
Exp/Cntr=.3,.1

Type RM Length L Ch R = 3 ,268.04  ,,,
BEGIN DESCRIPTION:
5.018
END DESCRIPTION:
Bridge Culvert--1,0,-1,-1, 0
Deck Dist Width WeirC Skew NumUp NumDn MinLoCord MaxHiCord MaxSubmerge Is_Ogee
.01,7.9,1.44,0, 2, 2, , , .95, 0, 0,0,,
       0     4.6
   21.89   21.89
   21.69   21.69
       0     4.6
   21.89   21.89
   21.69   21.69
BR Coef=-1 , 1 , 0 ,, 0 ,,,.8,-1,1.2,0,
WSPro=,,,, 1 ,,,, 0 ,,,, 0 ,,,,-1 ,-1 ,-1 , 0 , 0 , 0 , 0 , 0
BC Design=,, 0 ,, 0 ,,,,,,

Type RM Length L Ch R = 1 ,264.00  ,14,14,14
BEGIN DESCRIPTION:
5.014
END DESCRIPTION:
#Sta/Elev= 6
     -10   21.89       0   21.89      .5   19.99       4   19.99     4.6   21.89
       6   21.89
#Mann= 3 , 0 , 0
     -10    .035       0       0    .035       0     4.6    .035       0
#XS Ineff= 2 , 0
       0       0   21.89     4.6       0   21.89
Permanent Ineff=
       F       F
Bank Sta=0,4.6
XS Rating Curve= 0
Exp/Cntr=.3,.1

Type RM Length L Ch R = 1 ,250.00  ,7,7,7
BEGIN DESCRIPTION:
5
END DESCRIPTION:
#Sta/Elev= 7
     -10   21.46       0   21.46      .5   19.46       4   19.46     4.6   21.36
       6   21.16      16   21.16
#Mann= 3 , 0 , 0
     -10    .035       0       0    .035       0     4.6    .035       0
#XS Ineff= 2 , 0
       0       0   21.46     4.6       0   21.36
Permanent Ineff=
       F       F
Bank Sta=0,4.6
XS Rating Curve= 0
Exp/Cntr=.3,.1

Type RM Length L Ch R = 1 ,243.00  ,13,13,13
BEGIN DESCRIPTION:
4.043
END DESCRIPTION:
#Sta/Elev= 8
     -10   21.57       0   21.57       0   19.67     3.2   19.67     3.8   19.97
     7.6   19.97     7.6   21.57    17.6   21.57
#Mann= 3 , 0 , 0
     -10    .035       0       0    .035       0     7.6    .035       0
#XS Ineff= 2 , 0
       0       0   21.57     7.6       0   19.97
Permanent Ineff=
       F       F
Bank Sta=0,7.6
XS Rating Curve= 0
Exp/Cntr=.3,.1

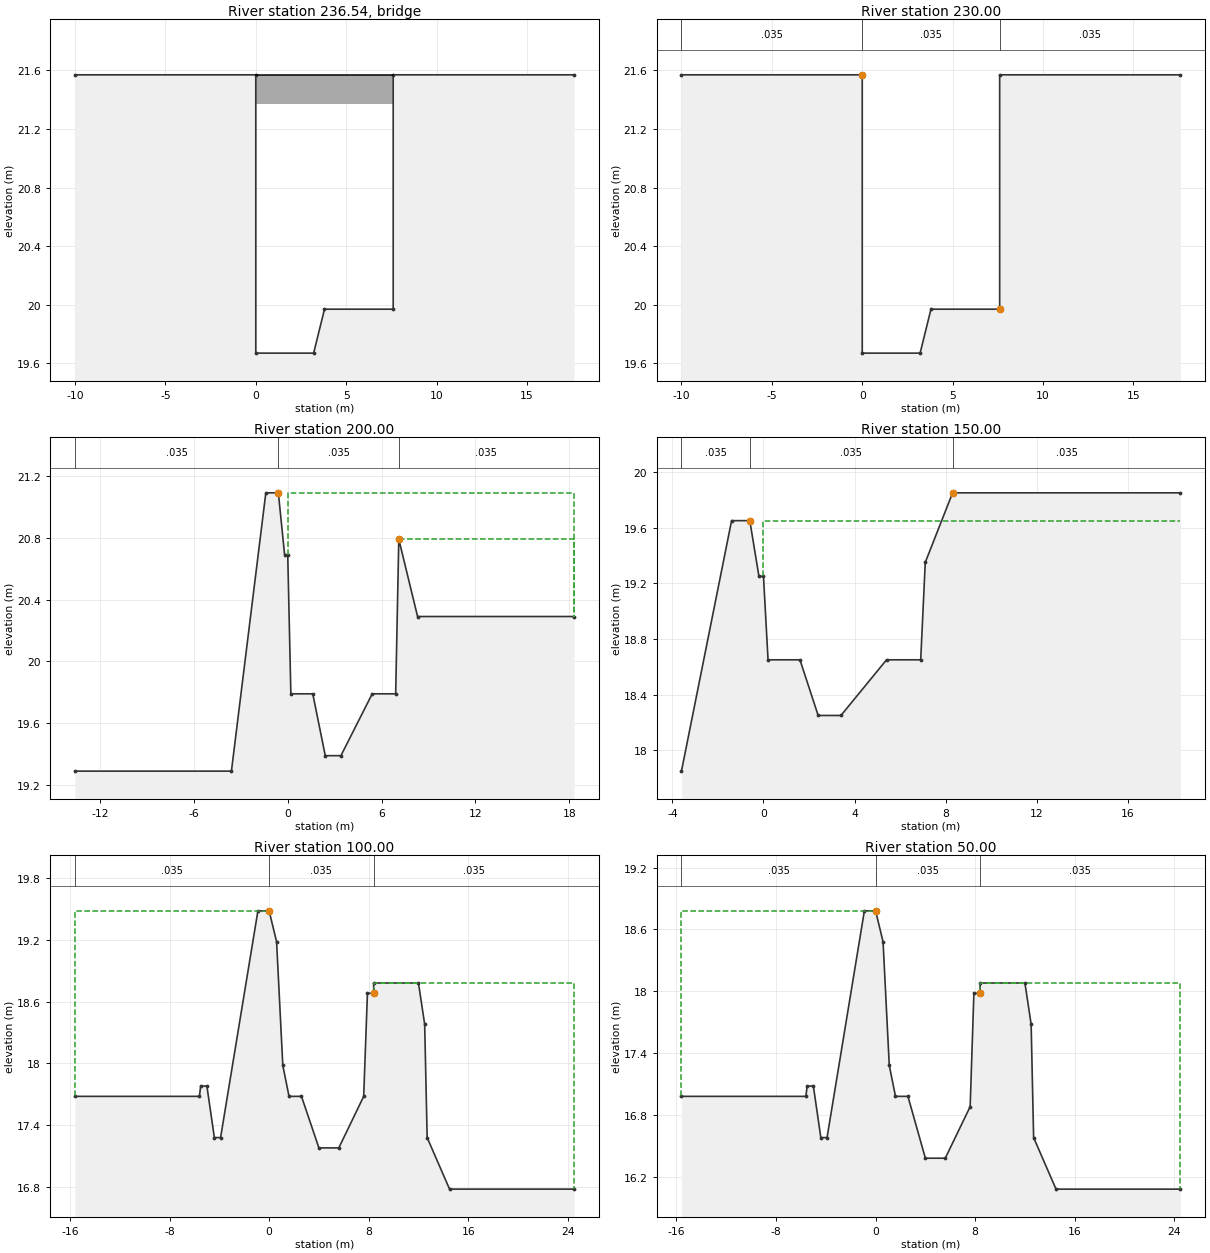
Type RM Length L Ch R = 3 ,236.54  ,,,
BEGIN DESCRIPTION:
4.0365
END DESCRIPTION:
Bridge Culvert--1,0,-1,-1, 0
Deck Dist Width WeirC Skew NumUp NumDn MinLoCord MaxHiCord MaxSubmerge Is_Ogee
.01,12.9,1.44,0, 2, 2, , , .95, 0, 0,0,,
       0     7.6
   21.57   21.57
   21.37   21.37
       0     7.6
   21.57   21.57
   21.37   21.37
BR Coef=-1 , 1 , 0 ,, 0 ,,,.8,-1,1.2,0,
WSPro=,,,, 1 ,,,, 0 ,,,, 0 ,,,,-1 ,-1 ,-1 , 0 , 0 , 0 , 0 , 0
BC Design=,, 0 ,, 0 ,,,,,,

Type RM Length L Ch R = 1 ,230.00  ,30,30,30
BEGIN DESCRIPTION:
4.030
END DESCRIPTION:
#Sta/Elev= 8
     -10   21.57       0   21.57       0   19.67     3.2   19.67     3.8   19.97
     7.6   19.97     7.6   21.57    17.6   21.57
#Mann= 3 , 0 , 0
     -10    .035       0       0    .035       0     7.6    .035       0
#XS Ineff= 2 , 0
       0       0   21.57     7.6       0   19.97
Permanent Ineff=
       F       F
Bank Sta=0,7.6
XS Rating Curve= 0
Exp/Cntr=.3,.1

Type RM Length L Ch R = 1 ,200.00  ,50,50,50
BEGIN DESCRIPTION:
4
END DESCRIPTION:
#Sta/Elev= 15
   -13.6   19.29    -3.6   19.29    -1.4   21.09     -.6   21.09     -.2   20.69
       0   20.69      .2   19.79     1.6   19.79     2.4   19.39     3.4   19.39
     5.4   19.79     6.9   19.79     7.1   20.79     8.3   20.29    18.3   20.29
#Mann= 3 , 0 , 0
   -13.6    .035       0     -.6    .035       0     7.1    .035       0
#XS Ineff= 2 , 0
       0     -.6   21.09     7.1       0   20.79
Permanent Ineff=
       F       F
Bank Sta=-.6,7.1
XS Rating Curve= 0
Exp/Cntr=.3,.1

Type RM Length L Ch R = 1 ,150.00  ,50,50,50
BEGIN DESCRIPTION:
3
END DESCRIPTION:
#Sta/Elev= 14
    -3.6   17.85    -1.4   19.65     -.6   19.65     -.2   19.25       0   19.25
      .2   18.65     1.6   18.65     2.4   18.25     3.4   18.25     5.4   18.65
     6.9   18.65     7.1   19.35     8.3   19.85    18.3   19.85
#Mann= 3 , 0 , 0
    -3.6    .035       0     -.6    .035       0     8.3    .035       0
#XS Ineff= 2 , 0
       0     -.6   19.65     8.3       0   19.85
Permanent Ineff=
       F       F
Bank Sta=-.6,8.3
XS Rating Curve= 0
Exp/Cntr=.3,.1

Type RM Length L Ch R = 1 ,100.00  ,50,50,50
BEGIN DESCRIPTION:
2
END DESCRIPTION:
#Sta/Elev= 23
   -15.6   17.68    -5.6   17.68    -5.5   17.78      -5   17.78    -4.4   17.28
    -3.9   17.28     -.9   19.48       0   19.48      .6   19.18     1.1   17.98
     1.6   17.68     2.6   17.68       4   17.18     5.6   17.18     7.6   17.68
     7.9   18.68     8.4   18.68     8.4   18.78      12   18.78    12.5   18.38
    12.7   17.28    14.5   16.78    24.5   16.78
#Mann= 3 , 0 , 0
   -15.6    .035       0       0    .035       0     8.4    .035       0
#XS Ineff= 2 , 0
               0   19.48     8.4           18.78
Permanent Ineff=
       F       F
Bank Sta=0,8.4
XS Rating Curve= 0
Exp/Cntr=.3,.1

Type RM Length L Ch R = 1 ,50.00   ,50,50,50
BEGIN DESCRIPTION:
1
END DESCRIPTION:
#Sta/Elev= 23
   -15.6   16.98    -5.6   16.98    -5.5   17.08      -5   17.08    -4.4   16.58
    -3.9   16.58     -.9   18.78       0   18.78      .6   18.48     1.1   17.28
     1.6   16.98     2.6   16.98       4   16.38     5.6   16.38     7.6   16.88
     7.9   17.98     8.4   17.98     8.4   18.08      12   18.08    12.5   17.68
    12.7   16.58    14.5   16.08    24.5   16.08
#Mann= 3 , 0 , 0
   -15.6    .035       0       0    .035       0     8.4    .035       0
#XS Ineff= 2 , 0
               0   18.78     8.4           18.08
Permanent Ineff=
       F       F
Bank Sta=0,8.4
XS Rating Curve= 0
Exp/Cntr=.3,.1

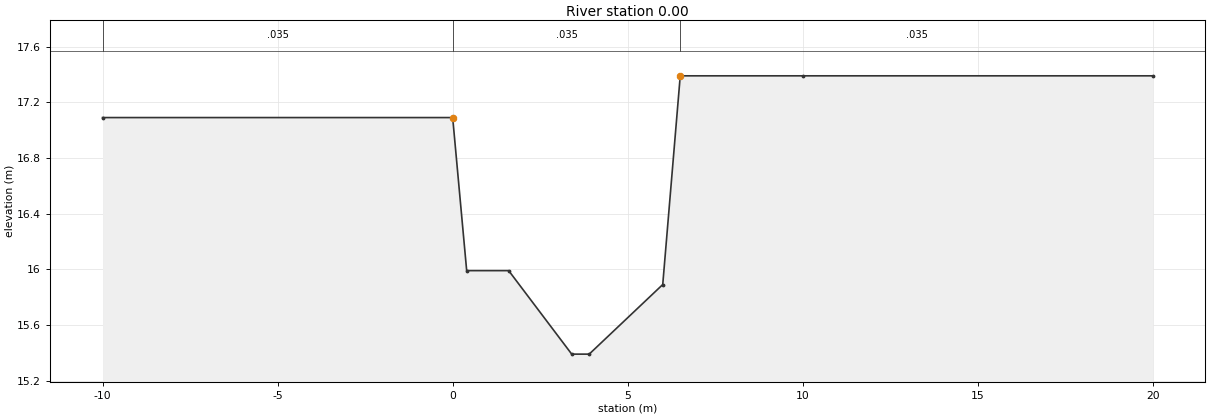
Type RM Length L Ch R = 1 ,0.00    ,0,0,0
BEGIN DESCRIPTION:
0
END DESCRIPTION:
#Sta/Elev= 10
     -10   17.09       0   17.09      .4   15.99     1.6   15.99     3.4   15.39
     3.9   15.39       6   15.89     6.5   17.39      10   17.39      20   17.39
#Mann= 3 , 0 , 0
     -10    .035       0       0    .035       0     6.5    .035       0
#XS Ineff= 2 , 0
               0   17.09     6.5           17.39
Permanent Ineff=
       F       F
Bank Sta=0,6.5
XS Rating Curve= 0
Exp/Cntr=.3,.1

Chan Stop Cuts=-1