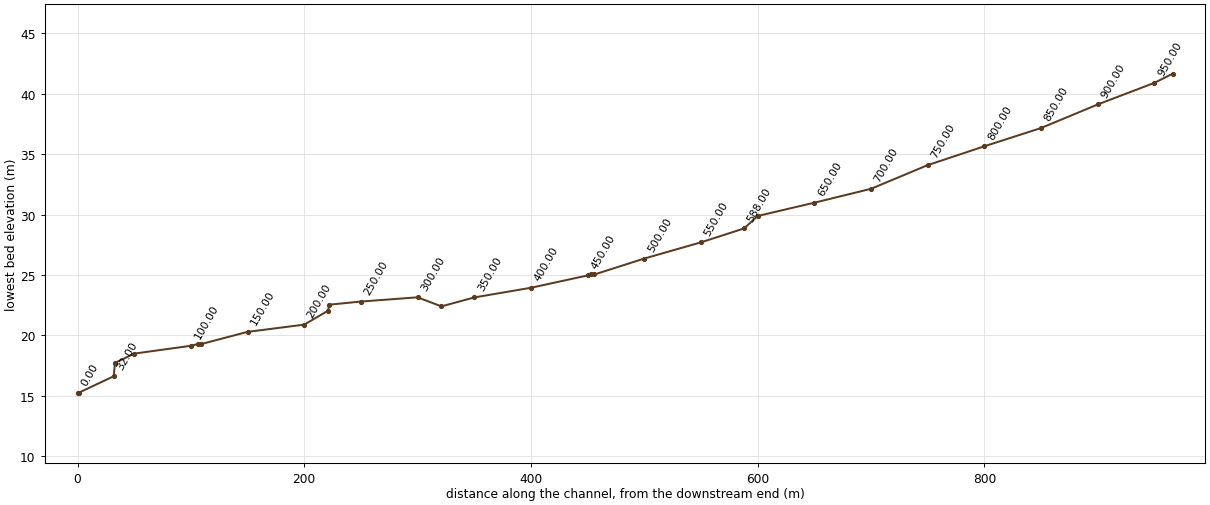
--- nsc.prj (project) ---

Proj Title=neaseung-ch
Current Plan=p01
Default Exp/Contr=.3,.1
SI Units
Geom File=g01
Flow File=f01
Plan File=p01
Y Axis Title=Elevation
X Axis Title(PF)=Main Channel Distance
X Axis Title(XS)=Station
BEGIN DESCRIPTION:
           BACK WATER COMPUTATION
      APPLICATION OF HEC-2 BY Samju Construction Engineering
      ³»¼ºÃµ(¿ËÃµÀ¾): 30,50,80,100,150³âºóµµ °³¼öÀü
END DESCRIPTION:
DSS Export Rating Curves= 0
DSS Export Rating Curve Sorted= 0
DSS Export Volume Flow Curves= 0
DXF OffsetX= 0
DXF OffsetY= 0
DXF ScaleX= 1
DXF ScaleY= 10

--- nsc.p01 (plan) ---

Plan Title=Imported Plan 01
Version=Version 3.0.1  Mar 2001
Short Identifier=Imported Pla
Geom File=g01
Flow File=f01
Subcritical Flow
K Sum by GR= 0
Std Step Tol= 0.003
Critical Tol= 0.003
Num of Std Step Trials= 20
Max Error Tol= 0.1
Flow Tol Ratio= 0.001
Split Flow NTrial= 30
Split Flow Tol= 0.02
Split Flow Ratio= 0.02
Log Output Level= 0
Friction Slope Method= 1
Unsteady Friction Slope Method= 2
Parabolic Critical Depth
Global Vel Dist= 0 , 0 , 0
Global Log Level= 0
CheckData=True
Encroach Param=-1 ,0,0, 0
Computation Interval=1HOUR
Output Interval=1HOUR
Run HTab= 0
Run UNet= 0
Run PostProcess= 0
UNET Theta= 1
UNET ZTol= 0.02
UNET ZSATol= 0.1
UNET MxIter= 20
UNET MaxInSteps= 20
UNET DtIC= 0
UNET DtMin= 0
UNET MaxCRTS= 20
UNET WFStab= 2
UNET SFStab= 1
UNET WFX= 1
UNET SFX= 1
UNET Convert EG Bridges=-1
UNET Use Existing IB Tables=-1
Instantaneous Interval=1HOUR
Write IC File= 0
Write Velocity= 0
Write Detailed= 0

--- nsc.f01 (steady flow) ---

Flow Title=Imported Flow 01
Version=Version 3.0.1  Mar 2001
Number of Profiles= 5
Profile Names=10yr,20yr,30yr,50yr,80yr
River Rch & RM=RIVER-1,Reach-1         ,19.016
   12.15   13.39   14.11   15.02   15.86
River Rch & RM=neaseung,neaseung        ,966.00
   12.15   13.39   14.11   15.02   15.86
Boundary for River Rch & Prof#=neaseung,neaseung        , 1
Up Type= 0
Dn Type= 3
Dn Slope=.0277
Boundary for River Rch & Prof#=neaseung,neaseung        , 2
Up Type= 0
Dn Type= 3
Dn Slope=.0277
Boundary for River Rch & Prof#=neaseung,neaseung        , 3
Up Type= 0
Dn Type= 3
Dn Slope=.0277
Boundary for River Rch & Prof#=neaseung,neaseung        , 4
Up Type= 0
Dn Type= 3
Dn Slope=.0277
Boundary for River Rch & Prof#=neaseung,neaseung        , 5
Up Type= 0
Dn Type= 3
Dn Slope=.0277
DSS Import GetInterval= 0
DSS Import GetPeak= 0
DSS Import FillOption= 0

--- nsc.g01 (geometry) ---

Geom Title=Imported Geom 01
Version=Version 3.0.1  Mar 2001

River Reach=neaseung        ,neaseung
Reach XY= 2
              .5             .95              .5             .05

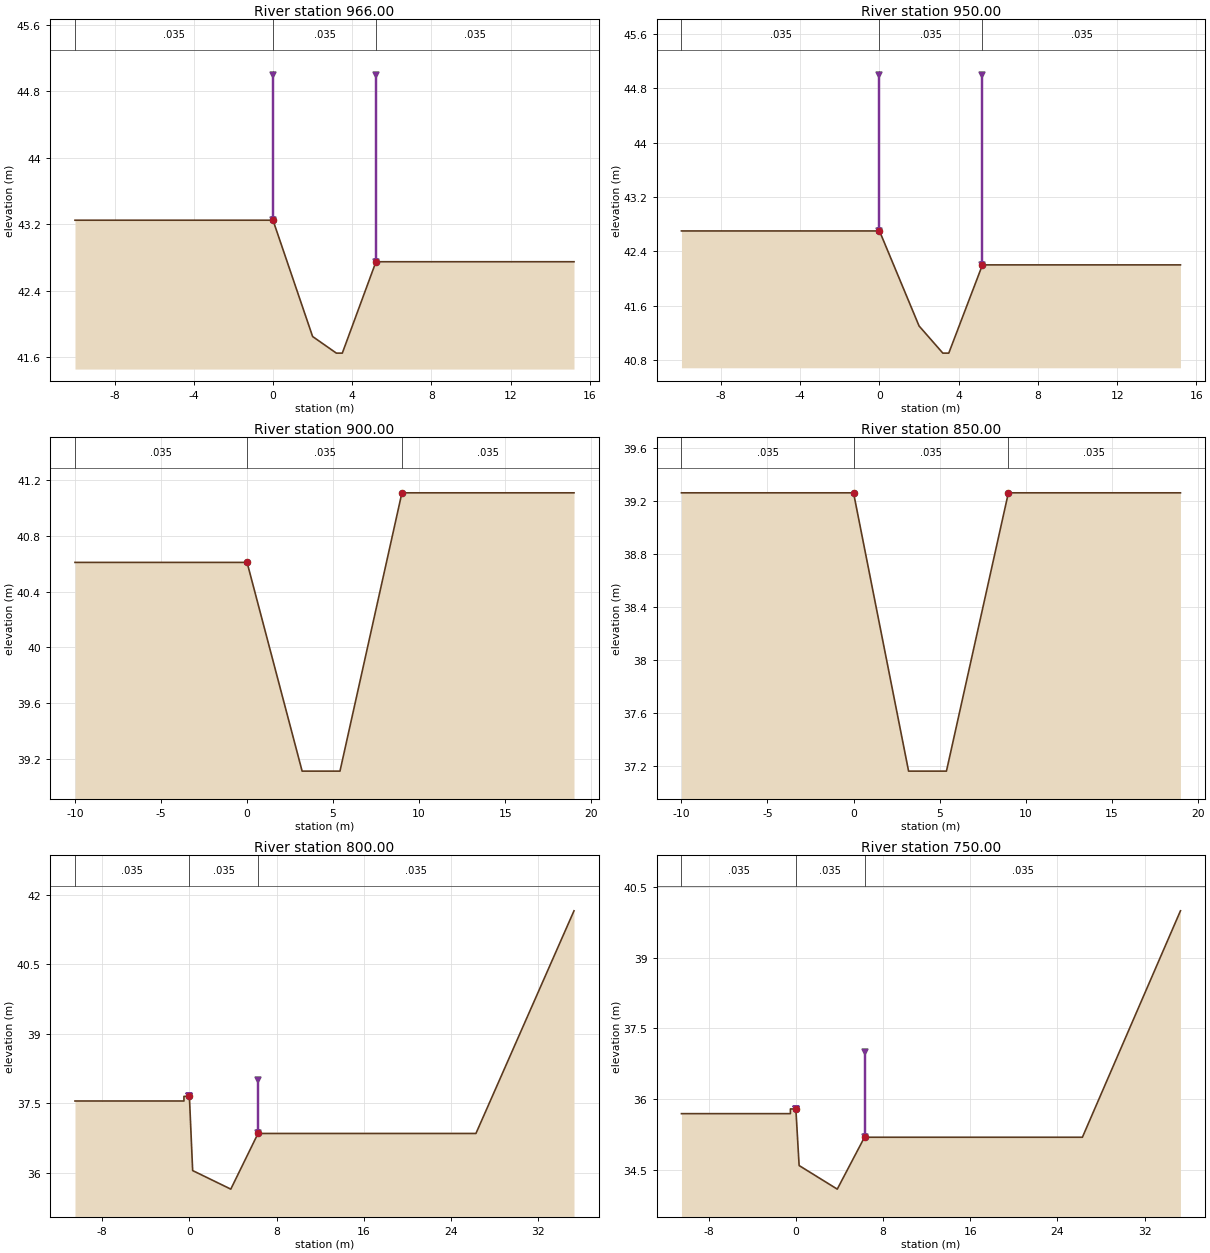
Type RM Length L Ch R = 1 ,966.00  ,16,16,16
BEGIN DESCRIPTION:
19.016
END DESCRIPTION:
#Sta/Elev= 7
     -10   43.25       0   43.25       2   41.85     3.2   41.65     3.5   41.65
     5.2   42.75    15.2   42.75
#Mann= 3 , 0 , 0
     -10    .035       0       0    .035       0     5.2    .035       0
Levee=-1,0,45,-1,5.2,45,,
#XS Ineff= 2 , 0
               0   43.25     5.2           42.75
Permanent Ineff=
       F       F
Bank Sta=0,5.2
XS Rating Curve= 0
Exp/Cntr=.3,.1

Type RM Length L Ch R = 1 ,950.00  ,50,50,50
BEGIN DESCRIPTION:
19
END DESCRIPTION:
#Sta/Elev= 7
     -10    42.7       0    42.7       2    41.3     3.2    40.9     3.5    40.9
     5.2    42.2    15.2    42.2
#Mann= 3 , 0 , 0
     -10    .035       0       0    .035       0     5.2    .035       0
Levee=-1,0,45,-1,5.2,45,,
#XS Ineff= 2 , 0
               0    42.7     5.2            42.2
Permanent Ineff=
       F       F
Bank Sta=0,5.2
XS Rating Curve= 0
Exp/Cntr=.3,.1

Type RM Length L Ch R = 1 ,900.00  ,50,50,50
BEGIN DESCRIPTION:
18
END DESCRIPTION:
#Sta/Elev= 6
     -10   40.61       0   40.61     3.2   39.11     5.4   39.11       9   41.11
      19   41.11
#Mann= 3 , 0 , 0
     -10    .035       0       0    .035       0       9    .035       0
#XS Ineff= 2 , 0
               0   40.61       9           41.11
Permanent Ineff=
       F       F
Bank Sta=0,9
XS Rating Curve= 0
Exp/Cntr=.3,.1

Type RM Length L Ch R = 1 ,850.00  ,50,50,50
BEGIN DESCRIPTION:
17
END DESCRIPTION:
#Sta/Elev= 6
     -10   39.26       0   39.26     3.2   37.16     5.4   37.16       9   39.26
      19   39.26
#Mann= 3 , 0 , 0
     -10    .035       0       0    .035       0       9    .035       0
#XS Ineff= 2 , 0
               0   39.26       9           39.26
Permanent Ineff=
       F       F
Bank Sta=0,9
XS Rating Curve= 0
Exp/Cntr=.3,.1

Type RM Length L Ch R = 1 ,800.00  ,50,50,50
BEGIN DESCRIPTION:
16
END DESCRIPTION:
#Sta/Elev= 11
   -10.5   37.55     -.5   37.55     -.5   37.65       0   37.65      .3   36.05
     3.8   35.65     6.3   36.85    26.3   36.85    29.3   38.45    32.3   40.05
    35.3   41.65
#Mann= 3 , 0 , 0
   -10.5    .035       0       0    .035       0     6.3    .035       0
Levee=-1,0,37.65,-1,6.3,38,,
#XS Ineff= 2 , 0
       0       0   37.65     6.3       0   36.85
Permanent Ineff=
       F       F
Bank Sta=0,6.3
XS Rating Curve= 0
Exp/Cntr=.3,.1

Type RM Length L Ch R = 1 ,750.00  ,50,50,50
BEGIN DESCRIPTION:
15
END DESCRIPTION:
#Sta/Elev= 11
   -10.5   35.69     -.5   35.69     -.5   35.79       0   35.79      .3   34.59
     3.8   34.09     6.3   35.19    26.3   35.19    29.3   36.79    32.3   38.39
    35.3   39.99
#Mann= 3 , 0 , 0
   -10.5    .035       0       0    .035       0     6.3    .035       0
Levee=-1,0,35.79,-1,6.3,37,,
#XS Ineff= 2 , 0
       0       0   35.79     6.3       0   35.19
Permanent Ineff=
       F       F
Bank Sta=0,6.3
XS Rating Curve= 0
Exp/Cntr=.3,.1

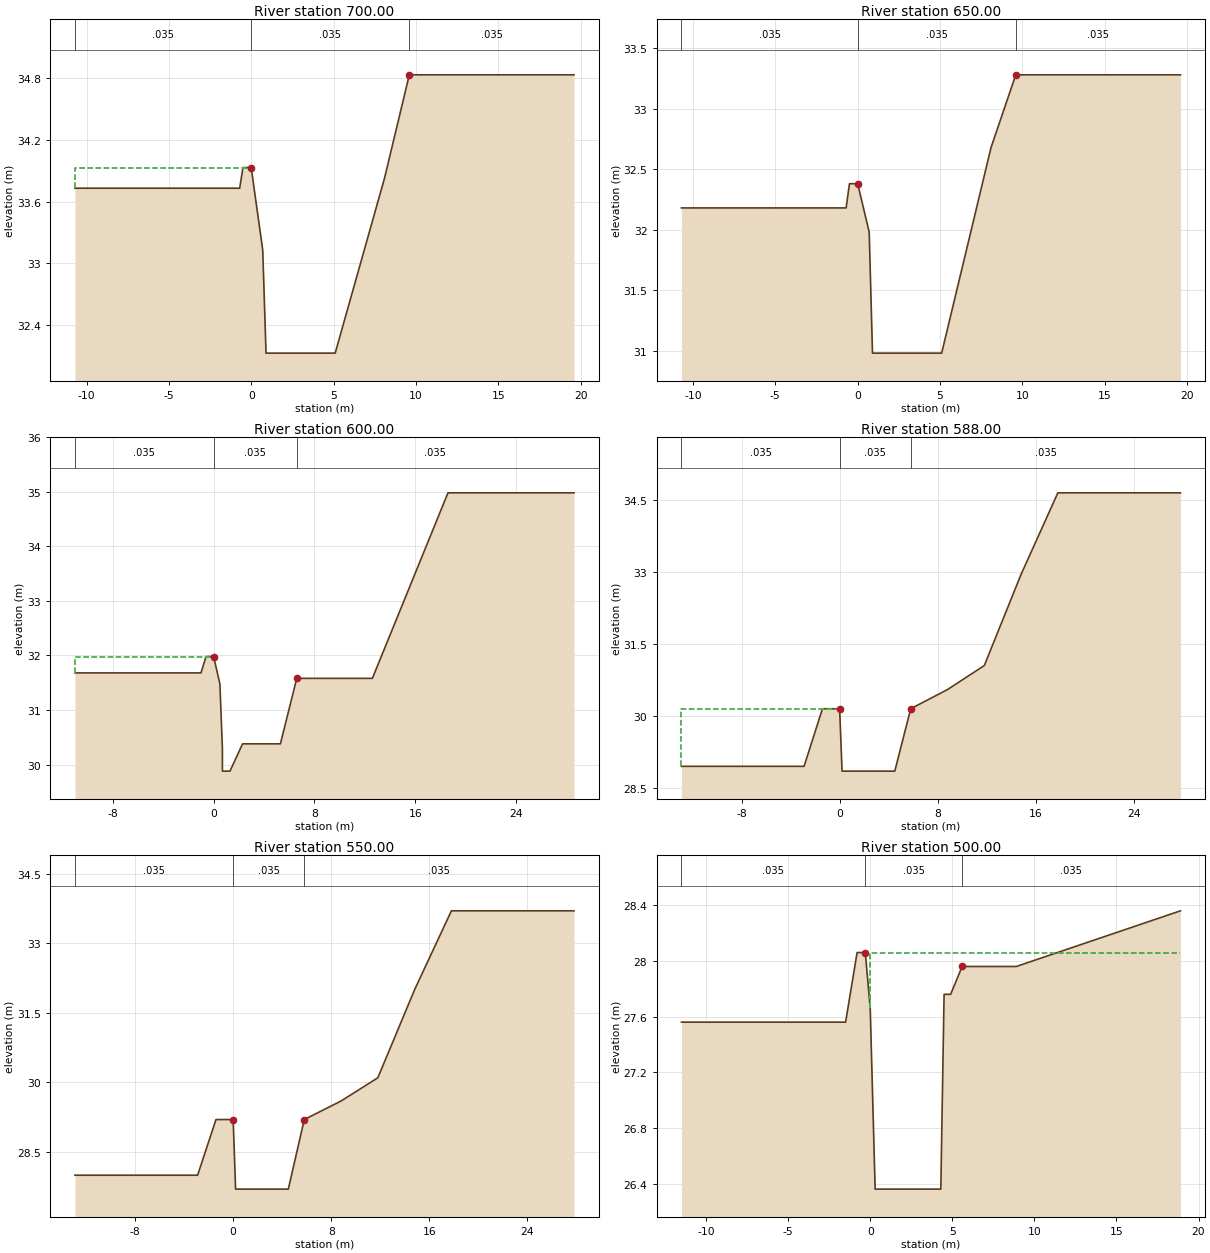
Type RM Length L Ch R = 1 ,700.00  ,50,50,50
BEGIN DESCRIPTION:
14
END DESCRIPTION:
#Sta/Elev= 10
   -10.7   33.73     -.7   33.73     -.5   33.93       0   33.93      .7   33.13
      .9   32.13     5.1   32.13     8.1   33.83     9.6   34.83    19.6   34.83
#Mann= 3 , 0 , 0
   -10.7    .035       0       0    .035       0     9.6    .035       0
#XS Ineff= 2 , 0
               0   33.93     9.6           34.83
Permanent Ineff=
       F       F
Bank Sta=0,9.6
XS Rating Curve= 0
Exp/Cntr=.3,.1

Type RM Length L Ch R = 1 ,650.00  ,50,50,50
BEGIN DESCRIPTION:
13
END DESCRIPTION:
#Sta/Elev= 10
   -10.7   32.18     -.7   32.18     -.5   32.38       0   32.38      .7   31.98
      .9   30.98     5.1   30.98     8.1   32.68     9.6   33.28    19.6   33.28
#Mann= 3 , 0 , 0
   -10.7    .035       0       0    .035       0     9.6    .035       0
#XS Ineff= 2 , 0
       0       0   32.38     9.6       0   33.28
Permanent Ineff=
       F       F
Bank Sta=0,9.6
XS Rating Curve= 0
Exp/Cntr=.3,.1

Type RM Length L Ch R = 1 ,600.00  ,12,12,12
BEGIN DESCRIPTION:
12
END DESCRIPTION:
#Sta/Elev= 15
     -11   31.68      -1   31.68     -.6   31.98       0   31.98      .5   31.48
      .7   30.28      .7   29.88     1.3   29.88     2.3   30.38     5.3   30.38
     6.6   31.58    12.6   31.58    15.6   33.28    18.6   34.98    28.6   34.98
#Mann= 3 , 0 , 0
     -11    .035       0       0    .035       0     6.6    .035       0
#XS Ineff= 2 , 0
               0   31.98     6.6           31.58
Permanent Ineff=
       F       F
Bank Sta=0,6.6
XS Rating Curve= 0
Exp/Cntr=.3,.1

Type RM Length L Ch R = 1 ,588.00  ,38,38,38
BEGIN DESCRIPTION:
11.038
END DESCRIPTION:
#Sta/Elev= 12
   -12.9   28.95    -2.9   28.95    -1.4   30.15       0   30.15      .2   28.85
     4.5   28.85     5.8   30.15     8.8   30.55    11.8   31.05    14.8   32.95
    17.8   34.65    27.8   34.65
#Mann= 3 , 0 , 0
   -12.9    .035       0       0    .035       0     5.8    .035       0
#XS Ineff= 2 , 0
               0   30.15     5.8           30.15
Permanent Ineff=
       F       F
Bank Sta=0,5.8
XS Rating Curve= 0
Exp/Cntr=.3,.1

Type RM Length L Ch R = 1 ,550.00  ,50,50,50
BEGIN DESCRIPTION:
11
END DESCRIPTION:
#Sta/Elev= 12
   -12.9      28    -2.9      28    -1.4    29.2       0    29.2      .2    27.7
     4.5    27.7     5.8    29.2     8.8    29.6    11.8    30.1    14.8      32
    17.8    33.7    27.8    33.7
#Mann= 3 , 0 , 0
   -12.9    .035       0       0    .035       0     5.8    .035       0
#XS Ineff= 2 , 0
       0       0    29.2     5.8       0    29.2
Permanent Ineff=
       F       F
Bank Sta=0,5.8
XS Rating Curve= 0
Exp/Cntr=.3,.1

Type RM Length L Ch R = 1 ,500.00  ,44,44,44
BEGIN DESCRIPTION:
10
END DESCRIPTION:
#Sta/Elev= 13
   -11.5   27.56    -1.5   27.56     -.8   28.06     -.3   28.06       0   27.66
      .3   26.36     4.3   26.36     4.5   27.76     4.9   27.76     5.6   27.96
     8.9   27.96    13.9   28.16    18.9   28.36
#Mann= 3 , 0 , 0
   -11.5    .035       0     -.3    .035       0     5.6    .035       0
#XS Ineff= 2 , 0
       0     -.3   28.06     5.6       0   27.96
Permanent Ineff=
       F       F
Bank Sta=-.3,5.6
XS Rating Curve= 0
Exp/Cntr=.3,.1

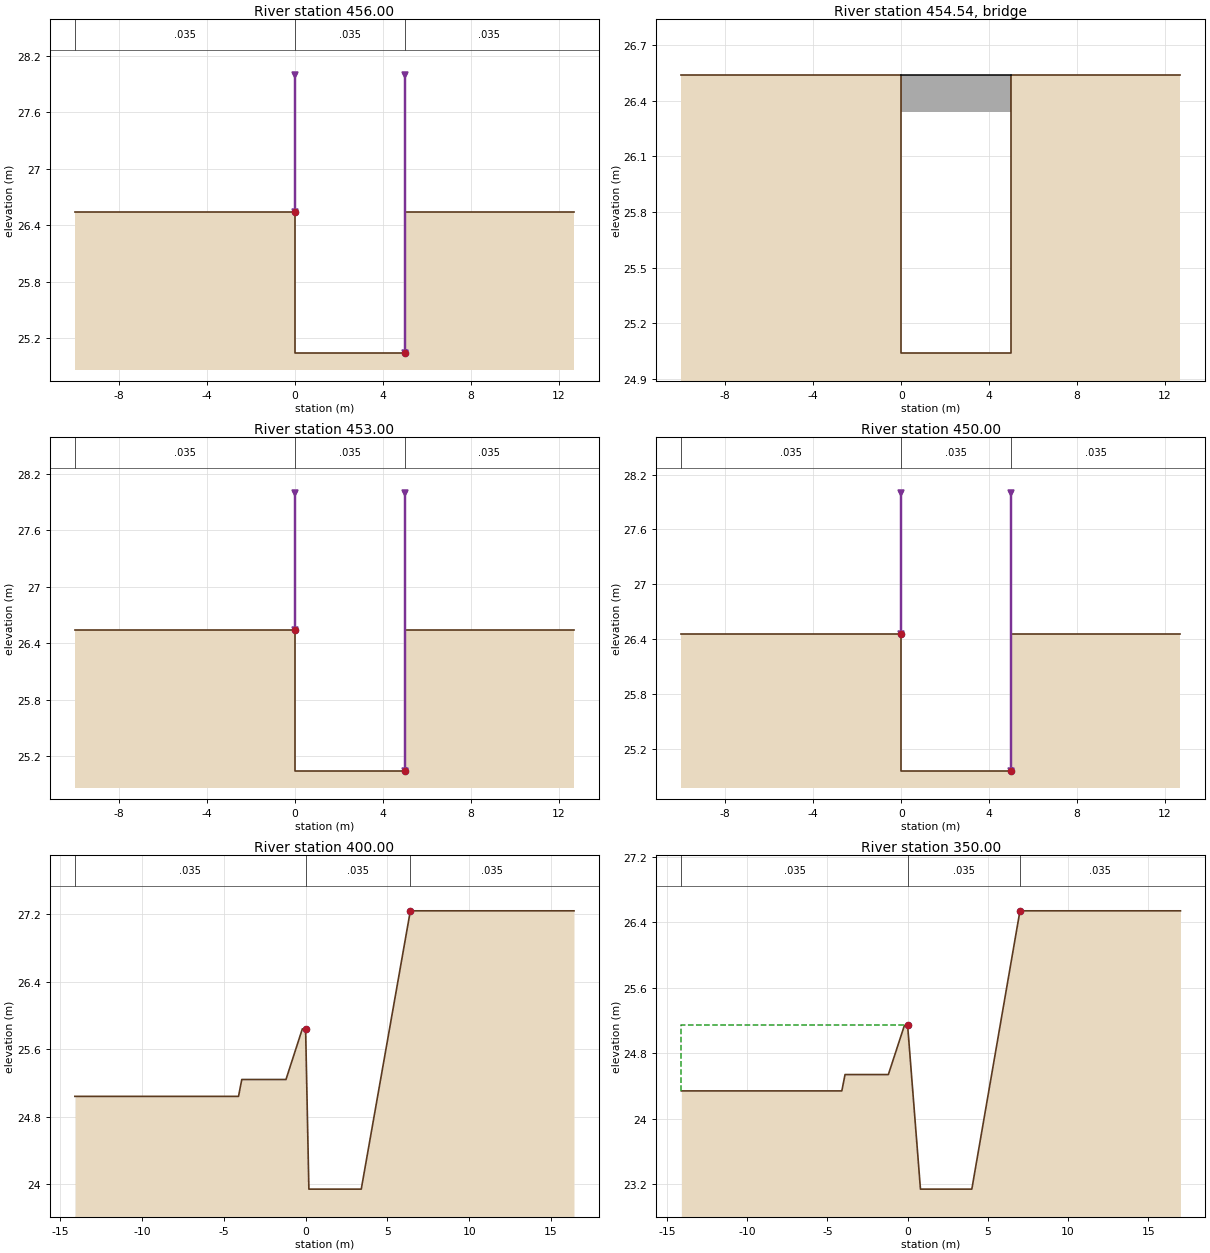
Type RM Length L Ch R = 1 ,456.00  ,3,3,3
BEGIN DESCRIPTION:
9.006
END DESCRIPTION:
#Sta/Elev= 6
     -10   26.54       0   26.54       0   25.04       5   25.04       5   26.54
    12.7   26.54
#Mann= 3 , 0 , 0
     -10    .035       0       0    .035       0       5    .035       0
Levee=-1,0,28,-1,5,28,,
Bank Sta=0,5
XS Rating Curve= 0
Exp/Cntr=.3,.1

Type RM Length L Ch R = 3 ,454.54  ,,,
BEGIN DESCRIPTION:
9.0045
END DESCRIPTION:
Bridge Culvert--1,0,-1,-1, 0
Deck Dist Width WeirC Skew NumUp NumDn MinLoCord MaxHiCord MaxSubmerge Is_Ogee
.01,2.9,1.44,0, 2, 2, , , .95, 0, 0,0,,
       0       5
   26.54   26.54
   26.34   26.34
       0       5
   26.54   26.54
   26.34   26.34
BR Coef=-1 , 1 , 0 ,, 0 ,,,.8,-1,1.2,0,
WSPro=,,,, 1 ,,,, 0 ,,,, 0 ,,,,-1 ,-1 ,-1 , 0 , 0 , 0 , 0 , 0
BC Design=,, 0 ,, 0 ,,,,,,

Type RM Length L Ch R = 1 ,453.00  ,3,3,3
BEGIN DESCRIPTION:
9.003
END DESCRIPTION:
#Sta/Elev= 6
     -10   26.54       0   26.54       0   25.04       5   25.04       5   26.54
    12.7   26.54
#Mann= 3 , 0 , 0
     -10    .035       0       0    .035       0       5    .035       0
Levee=-1,0,28,-1,5,28,,
Bank Sta=0,5
XS Rating Curve= 0
Exp/Cntr=.3,.1

Type RM Length L Ch R = 1 ,450.00  ,50,50,50
BEGIN DESCRIPTION:
9
END DESCRIPTION:
#Sta/Elev= 6
     -10   26.46       0   26.46       0   24.96       5   24.96       5   26.46
    12.7   26.46
#Mann= 3 , 0 , 0
     -10    .035       0       0    .035       0       5    .035       0
Levee=-1,0,28,-1,5,28,,
Bank Sta=0,5
XS Rating Curve= 0
Exp/Cntr=.3,.1

Type RM Length L Ch R = 1 ,400.00  ,50,50,50
BEGIN DESCRIPTION:
8
END DESCRIPTION:
#Sta/Elev= 10
   -14.1   25.04    -4.1   25.04    -3.9   25.24    -1.2   25.24     -.2   25.84
       0   25.84      .2   23.94     3.4   23.94     6.4   27.24    16.4   27.24
#Mann= 3 , 0 , 0
   -14.1    .035       0       0    .035       0     6.4    .035       0
#XS Ineff= 2 , 0
       0       0   25.84     6.4       0   27.24
Permanent Ineff=
       F       F
Bank Sta=0,6.4
XS Rating Curve= 0
Exp/Cntr=.3,.1

Type RM Length L Ch R = 1 ,350.00  ,29,29,29
BEGIN DESCRIPTION:
7
END DESCRIPTION:
#Sta/Elev= 10
   -14.1   24.34    -4.1   24.34    -3.9   24.54    -1.2   24.54     -.2   25.14
       0   25.14      .8   23.14       4   23.14       7   26.54      17   26.54
#Mann= 3 , 0 , 0
   -14.1    .035       0       0    .035       0       7    .035       0
#XS Ineff= 2 , 0
               0   25.14       7           26.54
Permanent Ineff=
       F       F
Bank Sta=0,7
XS Rating Curve= 0
Exp/Cntr=.3,.1

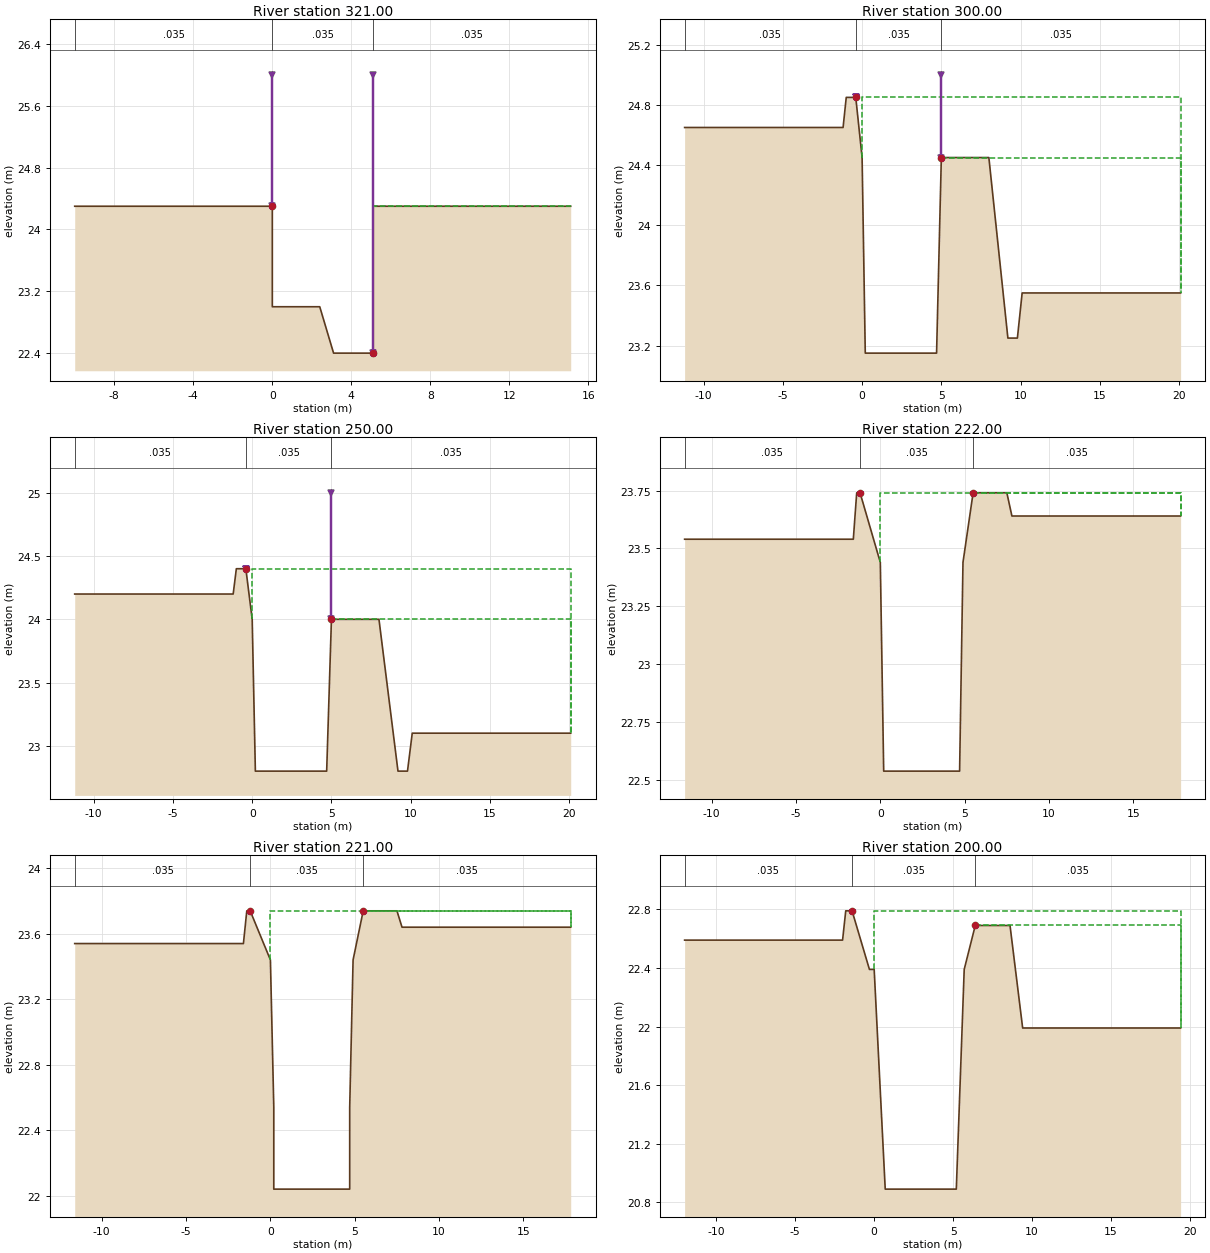
Type RM Length L Ch R = 1 ,321.00  ,21,21,21
BEGIN DESCRIPTION:
6.021
END DESCRIPTION:
#Sta/Elev= 8
     -10    24.3       0    24.3       0      23     2.4      23     3.1    22.4
     5.1    22.4     5.1    24.3    15.1    24.3
#Mann= 3 , 0 , 0
     -10    .035       0       0    .035       0     5.1    .035       0
Levee=-1,0,26,-1,5.1,26,,
#XS Ineff= 2 , 0
               0    24.3     5.1            24.3
Permanent Ineff=
       F       F
Bank Sta=0,5.1
XS Rating Curve= 0
Exp/Cntr=.3,.1

Type RM Length L Ch R = 1 ,300.00  ,50,50,50
BEGIN DESCRIPTION:
6
END DESCRIPTION:
#Sta/Elev= 14
   -11.2   24.65    -1.4   24.65    -1.2   24.65      -1   24.85     -.4   24.85
       0   24.45      .2   23.15     4.7   23.15       5   24.45       8   24.45
     9.2   23.25     9.8   23.25    10.1   23.55    20.1   23.55
#Mann= 3 , 0 , 0
   -11.2    .035       0     -.4    .035       0       5    .035       0
Levee=-1,-.4,24.85,-1,5,25,,
#XS Ineff= 2 , 0
       0     -.4   24.85       5       0   24.45
Permanent Ineff=
       F       F
Bank Sta=-.4,5
XS Rating Curve= 0
Exp/Cntr=.3,.1

Type RM Length L Ch R = 1 ,250.00  ,28,28,28
BEGIN DESCRIPTION:
5
END DESCRIPTION:
#Sta/Elev= 14
   -11.2    24.2    -1.4    24.2    -1.2    24.2      -1    24.4     -.4    24.4
       0      24      .2    22.8     4.7    22.8       5      24       8      24
     9.2    22.8     9.8    22.8    10.1    23.1    20.1    23.1
#Mann= 3 , 0 , 0
   -11.2    .035       0     -.4    .035       0       5    .035       0
Levee=-1,-.4,24.4,-1,5,25,,
#XS Ineff= 2 , 0
       0     -.4    24.4       5       0      24
Permanent Ineff=
       F       F
Bank Sta=-.4,5
XS Rating Curve= 0
Exp/Cntr=.3,.1

Type RM Length L Ch R = 1 ,222.00  ,1,1,1
BEGIN DESCRIPTION:
4.022
END DESCRIPTION:
#Sta/Elev= 12
   -11.6   23.54    -1.6   23.54    -1.4   23.74    -1.2   23.74       0   23.44
      .2   22.54     4.7   22.54     4.9   23.44     5.5   23.74     7.5   23.74
     7.8   23.64    17.8   23.64
#Mann= 3 , 0 , 0
   -11.6    .035       0    -1.2    .035       0     5.5    .035       0
#XS Ineff= 2 , 0
       0    -1.2   23.74     5.5       0   23.74
Permanent Ineff=
       F       F
Bank Sta=-1.2,5.5
XS Rating Curve= 0
Exp/Cntr=.3,.1

Type RM Length L Ch R = 1 ,221.00  ,21,21,21
BEGIN DESCRIPTION:
4.021
END DESCRIPTION:
#Sta/Elev= 14
   -11.6   23.54    -1.6   23.54    -1.4   23.74    -1.2   23.74       0   23.44
      .2   22.54      .2   22.04     4.7   22.04     4.7   22.54     4.9   23.44
     5.5   23.74     7.5   23.74     7.8   23.64    17.8   23.64
#Mann= 3 , 0 , 0
   -11.6    .035       0    -1.2    .035       0     5.5    .035       0
#XS Ineff= 2 , 0
       0    -1.2   23.74     5.5       0   23.74
Permanent Ineff=
       F       F
Bank Sta=-1.2,5.5
XS Rating Curve= 0
Exp/Cntr=.3,.1

Type RM Length L Ch R = 1 ,200.00  ,50,50,50
BEGIN DESCRIPTION:
4
END DESCRIPTION:
#Sta/Elev= 13
     -12   22.59      -2   22.59    -1.8   22.79    -1.4   22.79     -.3   22.39
       0   22.39      .7   20.89     5.2   20.89     5.7   22.39     6.4   22.69
     8.6   22.69     9.4   21.99    19.4   21.99
#Mann= 3 , 0 , 0
     -12    .035       0    -1.4    .035       0     6.4    .035       0
#XS Ineff= 2 , 0
       0    -1.4   22.79     6.4       0   22.69
Permanent Ineff=
       F       F
Bank Sta=-1.4,6.4
XS Rating Curve= 0
Exp/Cntr=.3,.1

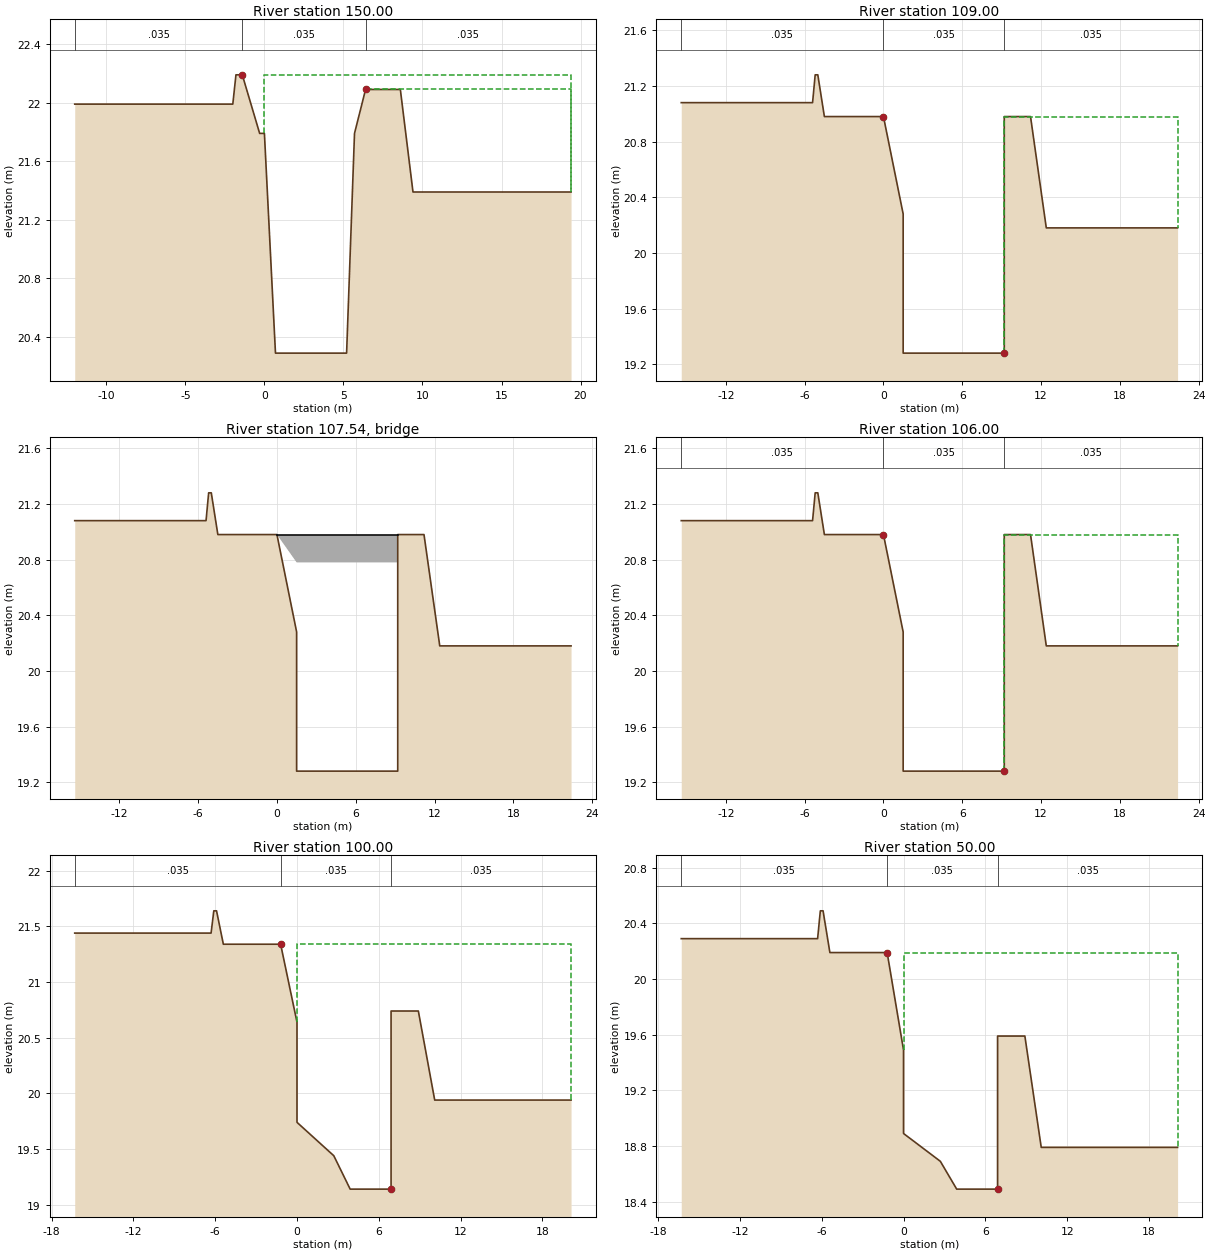
Type RM Length L Ch R = 1 ,150.00  ,41,41,41
BEGIN DESCRIPTION:
3
END DESCRIPTION:
#Sta/Elev= 13
     -12   21.99      -2   21.99    -1.8   22.19    -1.4   22.19     -.3   21.79
       0   21.79      .7   20.29     5.2   20.29     5.7   21.79     6.4   22.09
     8.6   22.09     9.4   21.39    19.4   21.39
#Mann= 3 , 0 , 0
     -12    .035       0    -1.4    .035       0     6.4    .035       0
#XS Ineff= 2 , 0
       0    -1.4   22.19     6.4       0   22.09
Permanent Ineff=
       F       F
Bank Sta=-1.4,6.4
XS Rating Curve= 0
Exp/Cntr=.3,.1

Type RM Length L Ch R = 1 ,109.00  ,3,3,3
BEGIN DESCRIPTION:
2.009
END DESCRIPTION:
#Sta/Elev= 13
   -15.4   21.08    -5.4   21.08    -5.2   21.28      -5   21.28    -4.5   20.98
       0   20.98     1.5   20.28     1.5   19.28     9.2   19.28     9.2   20.98
    11.2   20.98    12.4   20.18    22.4   20.18
#Mann= 3 , 0 , 0
   -15.4    .035       0       0    .035       0     9.2    .035       0
#XS Ineff= 2 , 0
               0   20.98     9.2           20.98
Permanent Ineff=
       F       F
Bank Sta=0,9.2
XS Rating Curve= 0
Exp/Cntr=.3,.1

Type RM Length L Ch R = 3 ,107.54  ,,,
BEGIN DESCRIPTION:
2.0075
END DESCRIPTION:
Bridge Culvert--1,0,-1,-1, 0
Deck Dist Width WeirC Skew NumUp NumDn MinLoCord MaxHiCord MaxSubmerge Is_Ogee
.01,2.9,1.44,0, 2, 2, , , .95, 0, 0,0,,
       0     9.2
   20.98   20.98
   20.78   20.78
       0     9.2
   20.98   20.98
   20.78   20.78
BR Coef=-1 , 1 , 0 ,, 0 ,,,.8,-1,1.2,0,
WSPro=,,,, 1 ,,,, 0 ,,,, 0 ,,,,-1 ,-1 ,-1 , 0 , 0 , 0 , 0 , 0
BC Design=,, 0 ,, 0 ,,,,,,

Type RM Length L Ch R = 1 ,106.00  ,6,6,6
BEGIN DESCRIPTION:
2.006
END DESCRIPTION:
#Sta/Elev= 13
   -15.4   21.08    -5.4   21.08    -5.2   21.28      -5   21.28    -4.5   20.98
       0   20.98     1.5   20.28     1.5   19.28     9.2   19.28     9.2   20.98
    11.2   20.98    12.4   20.18    22.4   20.18
#Mann= 3 , 0 , 0
   -15.4    .035       0       0    .035       0     9.2    .035       0
#XS Ineff= 2 , 0
               0   20.98     9.2           20.98
Permanent Ineff=
       F       F
Bank Sta=0,9.2
XS Rating Curve= 0
Exp/Cntr=.3,.1

Type RM Length L Ch R = 1 ,100.00  ,50,50,50
BEGIN DESCRIPTION:
2
END DESCRIPTION:
#Sta/Elev= 15
   -16.3   21.44    -6.3   21.44    -6.1   21.64    -5.9   21.64    -5.4   21.34
    -1.2   21.34       0   20.64       0   19.74     2.7   19.44     3.9   19.14
     6.9   19.14     6.9   20.74     8.9   20.74    10.1   19.94    20.1   19.94
#Mann= 3 , 0 , 0
   -16.3    .035       0    -1.2    .035       0     6.9    .035       0
#XS Ineff= 2 , 0
       0    -1.2   21.34     6.9       0   19.14
Permanent Ineff=
       F       F
Bank Sta=-1.2,6.9
XS Rating Curve= 0
Exp/Cntr=.3,.1

Type RM Length L Ch R = 1 ,50.00   ,17,17,17
BEGIN DESCRIPTION:
1
END DESCRIPTION:
#Sta/Elev= 15
   -16.3   20.29    -6.3   20.29    -6.1   20.49    -5.9   20.49    -5.4   20.19
    -1.2   20.19       0   19.49       0   18.89     2.7   18.69     3.9   18.49
     6.9   18.49     6.9   19.59     8.9   19.59    10.1   18.79    20.1   18.79
#Mann= 3 , 0 , 0
   -16.3    .035       0    -1.2    .035       0     6.9    .035       0
#XS Ineff= 2 , 0
       0    -1.2   20.19     6.9       0   18.49
Permanent Ineff=
       F       F
Bank Sta=-1.2,6.9
XS Rating Curve= 0
Exp/Cntr=.3,.1

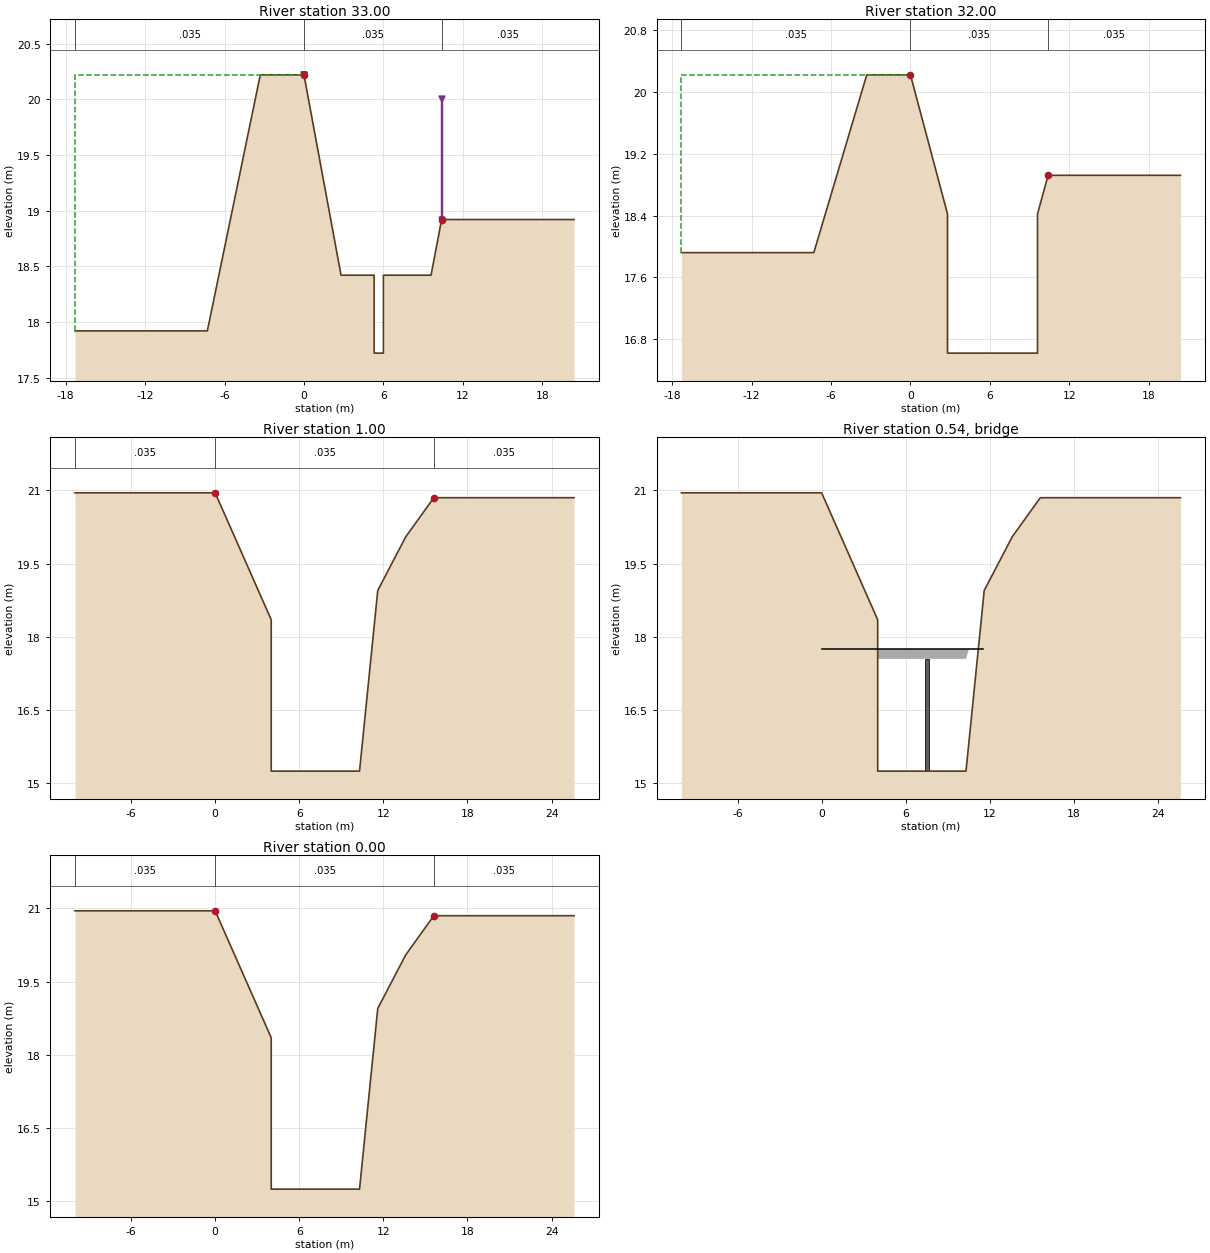
Type RM Length L Ch R = 1 ,33.00   ,1,1,1
BEGIN DESCRIPTION:
0.033
END DESCRIPTION:
#Sta/Elev= 12
   -17.3   17.92    -7.3   17.92    -3.3   20.22       0   20.22     2.8   18.42
     5.3   18.42     5.3   17.72       6   17.72       6   18.42     9.6   18.42
    10.4   18.92    20.4   18.92
#Mann= 3 , 0 , 0
   -17.3    .035       0       0    .035       0    10.4    .035       0
Levee=-1,0,20.22,-1,10.4,20,,
#XS Ineff= 2 , 0
               0   20.22    10.4           18.92
Permanent Ineff=
       F       F
Bank Sta=0,10.4
XS Rating Curve= 0
Exp/Cntr=.3,.1

Type RM Length L Ch R = 1 ,32.00   ,31,31,31
BEGIN DESCRIPTION:
0.032
END DESCRIPTION:
#Sta/Elev= 10
   -17.3   17.92    -7.3   17.92    -3.3   20.22       0   20.22     2.8   18.42
     2.8   16.62     9.6   16.62     9.6   18.42    10.4   18.92    20.4   18.92
#Mann= 3 , 0 , 0
   -17.3    .035       0       0    .035       0    10.4    .035       0
#XS Ineff= 2 , 0
               0   20.22    10.4           18.92
Permanent Ineff=
       F       F
Bank Sta=0,10.4
XS Rating Curve= 0
Exp/Cntr=.3,.1

Type RM Length L Ch R = 1 ,1.00    ,1,1,1
BEGIN DESCRIPTION:
0.001
END DESCRIPTION:
#Sta/Elev= 9
     -10   20.95       0   20.95       4   18.35       4   15.25    10.3   15.25
    11.6   18.95    13.6   20.05    15.6   20.85    25.6   20.85
#Mann= 3 , 0 , 0
     -10    .035       0       0    .035       0    15.6    .035       0
#XS Ineff= 2 , 0
               0   20.95    15.6           20.85
Permanent Ineff=
       F       F
Bank Sta=0,15.6
XS Rating Curve= 0
Exp/Cntr=.3,.1

Type RM Length L Ch R = 3 ,0.54    ,,,
BEGIN DESCRIPTION:
0.0005
END DESCRIPTION:
Bridge Culvert--1,0,-1,-1, 0
Deck Dist Width WeirC Skew NumUp NumDn MinLoCord MaxHiCord MaxSubmerge Is_Ogee
.01,.9,1.44,0, 2, 2, , , .95, 0, 0,0,,
       0    11.5
   17.75   17.75
   17.55   17.55
       0    11.5
   17.75   17.75
   17.55   17.55
Pier Skew, UpSta & Num, DnSta & Num=  ,7.5, 2 ,7.5, 2 , 0 , 0 , 0 ,,
      .3      .3
   15.25   17.75
      .3      .3
   15.25   17.75
BR Coef=-1 , 1 , 1 ,.9, 0 ,,,.8,-1,1.2,0,
WSPro=,,,, 1 ,,,, 0 ,,,, 0 ,,,,-1 ,-1 ,-1 , 0 , 0 , 0 , 0 , 0
BC Design=,, 0 ,, 0 ,,,,,,

Type RM Length L Ch R = 1 ,0.00    ,0,0,0
BEGIN DESCRIPTION:
0
END DESCRIPTION:
#Sta/Elev= 9
     -10   20.95       0   20.95       4   18.35       4   15.25    10.3   15.25
    11.6   18.95    13.6   20.05    15.6   20.85    25.6   20.85
#Mann= 3 , 0 , 0
     -10    .035       0       0    .035       0    15.6    .035       0
#XS Ineff= 2 , 0
               0   20.95    15.6           20.85
Permanent Ineff=
       F       F
Bank Sta=0,15.6
XS Rating Curve= 0
Exp/Cntr=.3,.1

Chan Stop Cuts=-1