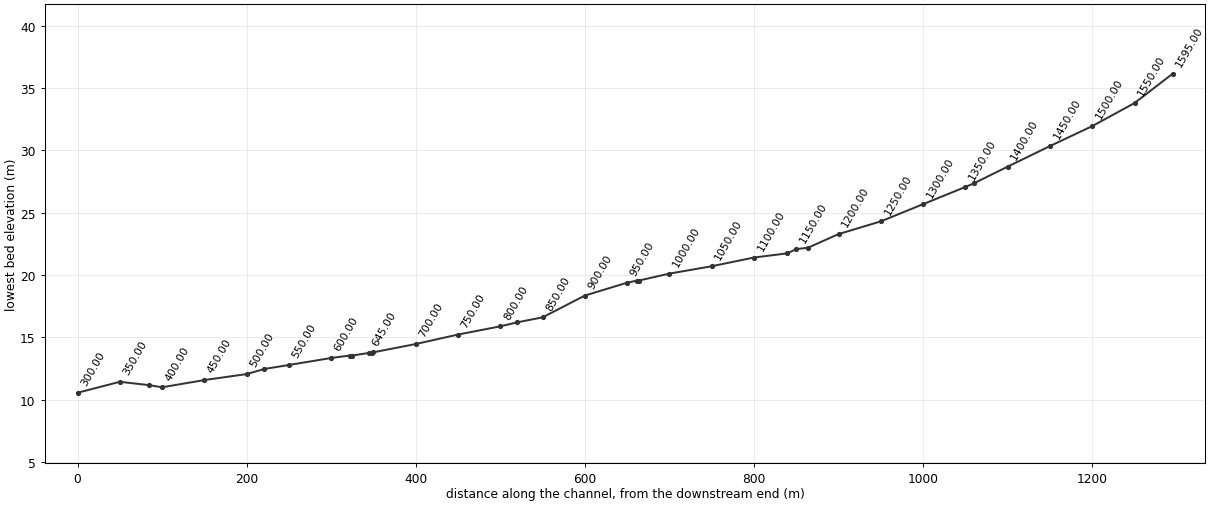
--- kzw.prj (project) ---

Proj Title=kazawool-ch
Current Plan=p01
Default Exp/Contr=.3,.1
SI Units
Geom File=g01
Flow File=f01
Plan File=p01
Y Axis Title=Elevation
X Axis Title(PF)=Main Channel Distance
X Axis Title(XS)=Station
BEGIN DESCRIPTION:
           BACK WATER COMPUTATION
      APPLICATION OF HEC-2 BY Samju Construction Engineering
    kazawool-ch : 10,20,30,50,80 yr
END DESCRIPTION:
DSS Export Rating Curves= 0
DSS Export Rating Curve Sorted= 0
DSS Export Volume Flow Curves= 0
DXF OffsetX= 0
DXF OffsetY= 0
DXF ScaleX= 1
DXF ScaleY= 10

--- kzw.p01 (plan) ---

Plan Title=Imported Plan 01
Version=Version 3.0.1  Mar 2001
Short Identifier=Imported Pla
Geom File=g01
Flow File=f01
Subcritical Flow
K Sum by GR= 0
Std Step Tol= 0.003
Critical Tol= 0.003
Num of Std Step Trials= 20
Max Error Tol= 0.1
Flow Tol Ratio= 0.001
Split Flow NTrial= 30
Split Flow Tol= 0.02
Split Flow Ratio= 0.02
Log Output Level= 0
Friction Slope Method= 1
Unsteady Friction Slope Method= 2
Parabolic Critical Depth
Global Vel Dist= 0 , 0 , 0
Global Log Level= 0
CheckData=True
Encroach Param=-1 ,0,0, 0
Computation Interval=1HOUR
Output Interval=1HOUR
Run HTab= 0
Run UNet= 0
Run PostProcess= 0
UNET Theta= 1
UNET ZTol= 0.02
UNET ZSATol= 0.1
UNET MxIter= 20
UNET MaxInSteps= 20
UNET DtIC= 0
UNET DtMin= 0
UNET MaxCRTS= 20
UNET WFStab= 2
UNET SFStab= 1
UNET WFX= 1
UNET SFX= 1
UNET Convert EG Bridges=-1
UNET Use Existing IB Tables=-1
Instantaneous Interval=1HOUR
Write IC File= 0
Write Velocity= 0
Write Detailed= 0

--- kzw.f01 (steady flow) ---

Flow Title=Imported Flow 01
Version=Version 3.0.1  Mar 2001
Number of Profiles= 5
Profile Names=10yr,20yr,30yr,50yr,80yr
River Rch & RM=RIVER-1,Reach-1         ,31.045
    6.98    7.69     8.1    8.62     9.1
River Rch & RM=RIVER-1,Reach-1         ,12
    8.28    9.12    9.61   10.23    10.8
River Rch & RM=°¡ÀÚ¿ïÃµ,°¡ÀÚ¿ïÃµ            ,31.045
    6.98    7.69     8.1    8.62     9.1
River Rch & RM=°¡ÀÚ¿ïÃµ,°¡ÀÚ¿ïÃµ            ,12
    8.28    9.12    9.61   10.23    10.8
River Rch & RM=kajawool,kajawool        ,1595.00
    6.98    7.69     8.1    8.62     9.1
River Rch & RM=kajawool,kajawool        ,600.00
    8.28    9.12    9.61   10.23    10.8
Boundary for River Rch & Prof#=kajawool,kajawool        , 1
Up Type= 0
Dn Type= 3
Dn Slope=.0188
Boundary for River Rch & Prof#=kajawool,kajawool        , 2
Up Type= 0
Dn Type= 3
Dn Slope=.0188
Boundary for River Rch & Prof#=kajawool,kajawool        , 3
Up Type= 0
Dn Type= 3
Dn Slope=.0188
Boundary for River Rch & Prof#=kajawool,kajawool        , 4
Up Type= 0
Dn Type= 3
Dn Slope=.0188
Boundary for River Rch & Prof#=kajawool,kajawool        , 5
Up Type= 0
Dn Type= 3
Dn Slope=.0188
DSS Import GetInterval= 0
DSS Import GetPeak= 0
DSS Import FillOption= 0

--- kzw.g01 (geometry) ---

Geom Title=Imported Geom 01
Version=Version 3.0.1  Mar 2001

River Reach=kajawool        ,kajawool
Reach XY= 2
              .5             .95              .5             .05

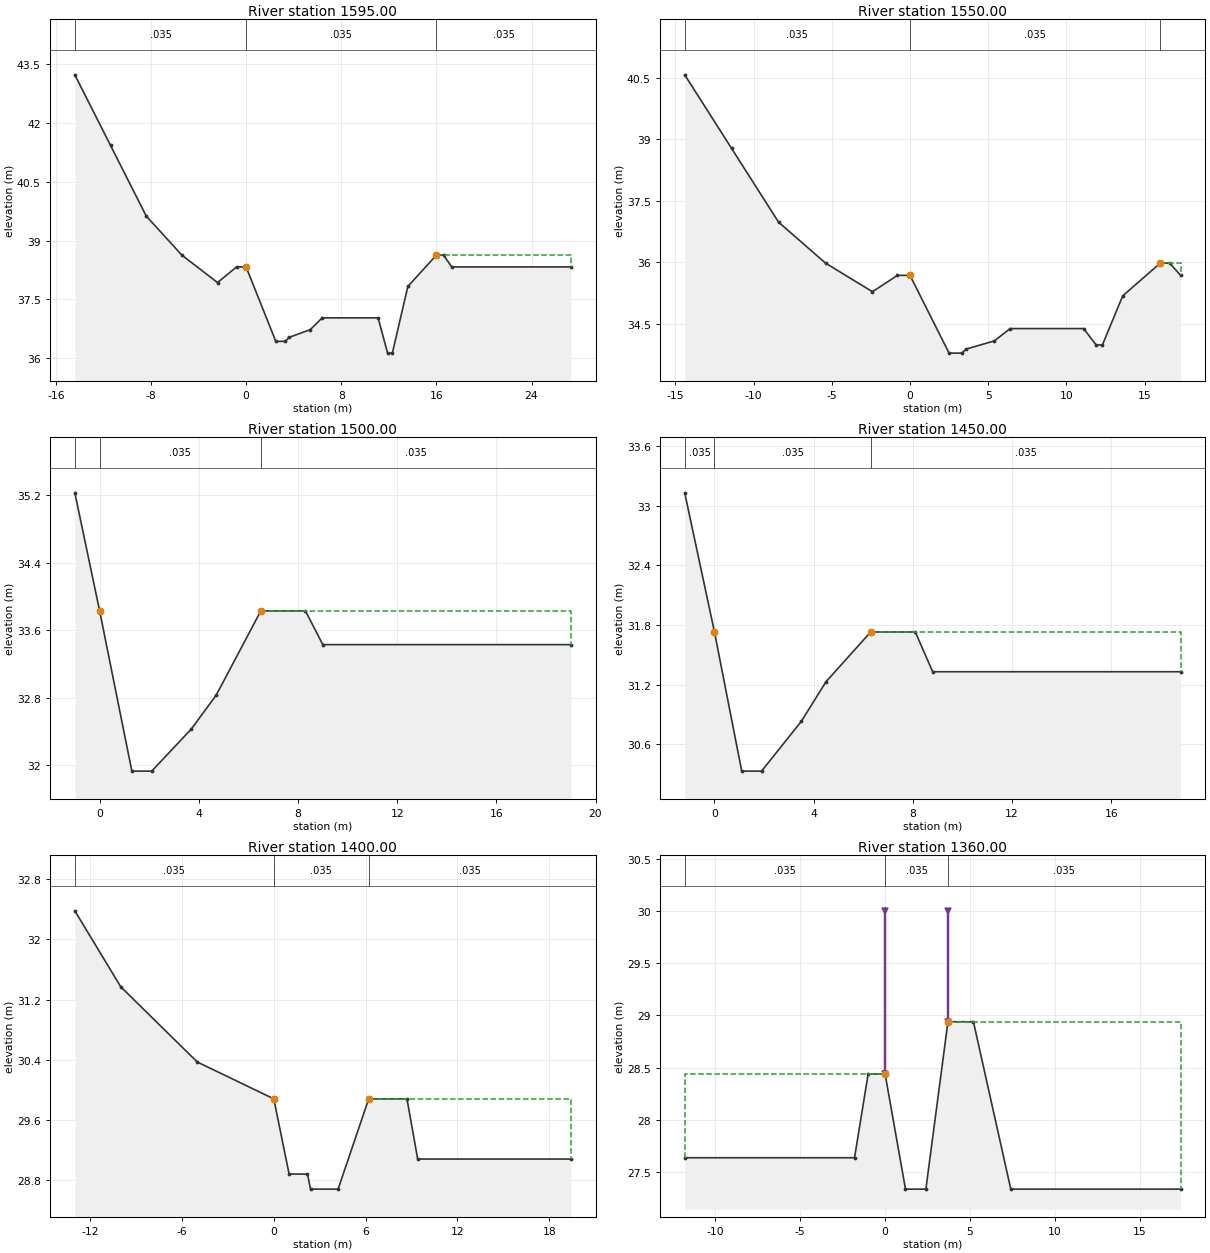
Type RM Length L Ch R = 1 ,1595.00 ,45,45,45
BEGIN DESCRIPTION:
31.045
END DESCRIPTION:
#Sta/Elev= 20
   -14.4   43.23   -11.4   41.43    -8.4   39.63    -5.4   38.63    -2.4   37.93
     -.8   38.33       0   38.33     2.5   36.43     3.3   36.43     3.6   36.53
     5.4   36.73     6.4   37.03    11.1   37.03    11.9   36.13    12.3   36.13
    13.6   37.83      16   38.63    16.6   38.63    17.3   38.33    27.3   38.33
#Mann= 3 , 0 , 0
   -14.4    .035       0       0    .035       0      16    .035       0
#XS Ineff= 2 , 0
               0   38.33      16           38.63
Permanent Ineff=
       F       F
Bank Sta=0,16
XS Rating Curve= 0
Exp/Cntr=.3,.1

Type RM Length L Ch R = 1 ,1550.00 ,50,50,50
BEGIN DESCRIPTION:
31
END DESCRIPTION:
#Sta/Elev= 19
   -14.4   40.58   -11.4   38.78    -8.4   36.98    -5.4   35.98    -2.4   35.28
     -.8   35.68       0   35.68     2.5   33.78     3.3   33.78     3.6   33.88
     5.4   34.08     6.4   34.38    11.1   34.38    11.9   33.98    12.3   33.98
    13.6   35.18      16   35.98    16.6   35.98    17.3   35.68
#Mann= 3 , 0 , 0
   -14.4    .035       0       0    .035       0      16    .035       0
#XS Ineff= 2 , 0
       0       0   35.68      16       0   35.98
Permanent Ineff=
       F       F
Bank Sta=0,16
XS Rating Curve= 0
Exp/Cntr=.3,.1

Type RM Length L Ch R = 1 ,1500.00 ,50,50,50
BEGIN DESCRIPTION:
30
END DESCRIPTION:
#Sta/Elev= 10
      -1   35.23       0   33.83     1.3   31.93     2.1   31.93     3.7   32.43
     4.7   32.83     6.5   33.83     8.3   33.83       9   33.43      19   33.43
#Mann= 3 , 0 , 0
      -1    .035       0       0    .035       0     6.5    .035       0
#XS Ineff= 2 , 0
               0   33.83     6.5           33.83
Permanent Ineff=
       F       F
Bank Sta=0,6.5
XS Rating Curve= 0
Exp/Cntr=.3,.1

Type RM Length L Ch R = 1 ,1450.00 ,50,50,50
BEGIN DESCRIPTION:
29
END DESCRIPTION:
#Sta/Elev= 10
    -1.2   33.13       0   31.73     1.1   30.33     1.9   30.33     3.5   30.83
     4.5   31.23     6.3   31.73     8.1   31.73     8.8   31.33    18.8   31.33
#Mann= 3 , 0 , 0
    -1.2    .035       0       0    .035       0     6.3    .035       0
#XS Ineff= 2 , 0
               0   31.73     6.3           31.73
Permanent Ineff=
       F       F
Bank Sta=0,6.3
XS Rating Curve= 0
Exp/Cntr=.3,.1

Type RM Length L Ch R = 1 ,1400.00 ,40,40,40
BEGIN DESCRIPTION:
28
END DESCRIPTION:
#Sta/Elev= 12
     -13   32.38     -10   31.37      -5   30.37       0   29.88       1   28.88
     2.2   28.88     2.4   28.68     4.2   28.68     6.2   29.88     8.7   29.88
     9.4   29.08    19.4   29.08
#Mann= 3 , 0 , 0
     -13    .035       0       0    .035       0     6.2    .035       0
#XS Ineff= 2 , 0
               0   29.88     6.2           29.88
Permanent Ineff=
       F       F
Bank Sta=0,6.2
XS Rating Curve= 0
Exp/Cntr=.3,.1

Type RM Length L Ch R = 1 ,1360.00 ,10,10,10
BEGIN DESCRIPTION:
27.01
END DESCRIPTION:
#Sta/Elev= 10
   -11.8   27.64    -1.8   27.64      -1   28.44       0   28.44     1.2   27.34
     2.4   27.34     3.7   28.94     5.2   28.94     7.4   27.34    17.4   27.34
#Mann= 3 , 0 , 0
   -11.8    .035       0       0    .035       0     3.7    .035       0
Levee=-1,0,30,-1,3.7,30,,
#XS Ineff= 2 , 0
               0   28.44     3.7           28.94
Permanent Ineff=
       F       F
Bank Sta=0,3.7
XS Rating Curve= 0
Exp/Cntr=.3,.1

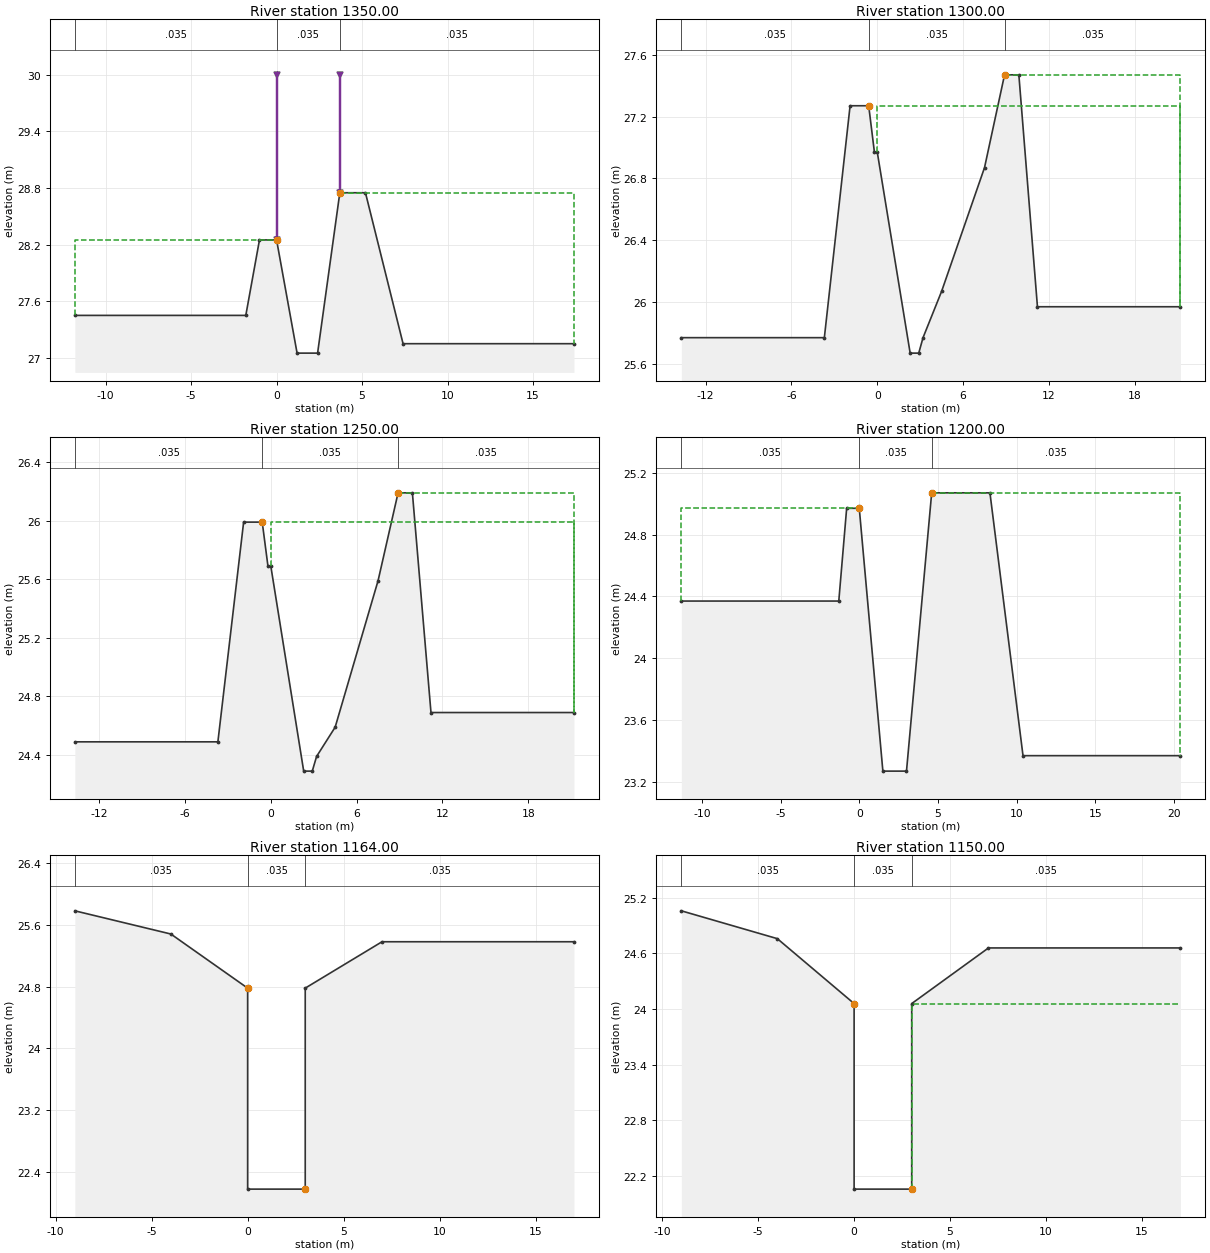
Type RM Length L Ch R = 1 ,1350.00 ,50,50,50
BEGIN DESCRIPTION:
27
END DESCRIPTION:
#Sta/Elev= 10
   -11.8   27.45    -1.8   27.45      -1   28.25       0   28.25     1.2   27.05
     2.4   27.05     3.7   28.75     5.2   28.75     7.4   27.15    17.4   27.15
#Mann= 3 , 0 , 0
   -11.8    .035       0       0    .035       0     3.7    .035       0
Levee=-1,0,30,-1,3.7,30,,
#XS Ineff= 2 , 0
               0   28.25     3.7           28.75
Permanent Ineff=
       F       F
Bank Sta=0,3.7
XS Rating Curve= 0
Exp/Cntr=.3,.1

Type RM Length L Ch R = 1 ,1300.00 ,50,50,50
BEGIN DESCRIPTION:
26
END DESCRIPTION:
#Sta/Elev= 15
   -13.7   25.77    -3.7   25.77    -1.9   27.27     -.6   27.27     -.2   26.97
       0   26.97     2.3   25.67     2.9   25.67     3.2   25.77     4.5   26.07
     7.5   26.87     8.9   27.47     9.9   27.47    11.2   25.97    21.2   25.97
#Mann= 3 , 0 , 0
   -13.7    .035       0     -.6    .035       0     8.9    .035       0
#XS Ineff= 2 , 0
       0     -.6   27.27     8.9       0   27.47
Permanent Ineff=
       F       F
Bank Sta=-.6,8.9
XS Rating Curve= 0
Exp/Cntr=.3,.1

Type RM Length L Ch R = 1 ,1250.00 ,50,50,50
BEGIN DESCRIPTION:
25
END DESCRIPTION:
#Sta/Elev= 15
   -13.7   24.49    -3.7   24.49    -1.9   25.99     -.6   25.99     -.2   25.69
       0   25.69     2.3   24.29     2.9   24.29     3.2   24.39     4.5   24.59
     7.5   25.59     8.9   26.19     9.9   26.19    11.2   24.69    21.2   24.69
#Mann= 3 , 0 , 0
   -13.7    .035       0     -.6    .035       0     8.9    .035       0
#XS Ineff= 2 , 0
       0     -.6   25.99     8.9       0   26.19
Permanent Ineff=
       F       F
Bank Sta=-.6,8.9
XS Rating Curve= 0
Exp/Cntr=.3,.1

Type RM Length L Ch R = 1 ,1200.00 ,36,36,36
BEGIN DESCRIPTION:
24
END DESCRIPTION:
#Sta/Elev= 10
   -11.3   24.37    -1.3   24.37     -.8   24.97       0   24.97     1.5   23.27
       3   23.27     4.6   25.07     8.3   25.07    10.4   23.37    20.4   23.37
#Mann= 3 , 0 , 0
   -11.3    .035       0       0    .035       0     4.6    .035       0
#XS Ineff= 2 , 0
               0   24.97     4.6           25.07
Permanent Ineff=
       F       F
Bank Sta=0,4.6
XS Rating Curve= 0
Exp/Cntr=.3,.1

Type RM Length L Ch R = 1 ,1164.00 ,14,14,14
BEGIN DESCRIPTION:
23.014
END DESCRIPTION:
#Sta/Elev= 8
      -9   25.78      -4   25.48       0   24.78       0   22.18       3   22.18
       3   24.78       7   25.38      17   25.38
#Mann= 3 , 0 , 0
      -9    .035       0       0    .035       0       3    .035       0
#XS Ineff= 2 , 0
       0       0   24.78       3       0   22.18
Permanent Ineff=
       F       F
Bank Sta=0,3
XS Rating Curve= 0
Exp/Cntr=.3,.1

Type RM Length L Ch R = 1 ,1150.00 ,11,11,11
BEGIN DESCRIPTION:
23
END DESCRIPTION:
#Sta/Elev= 8
      -9   25.06      -4   24.76       0   24.06       0   22.06       3   22.06
       3   24.06       7   24.66      17   24.66
#Mann= 3 , 0 , 0
      -9    .035       0       0    .035       0       3    .035       0
#XS Ineff= 2 , 0
               0   24.06       3           24.06
Permanent Ineff=
       F       F
Bank Sta=0,3
XS Rating Curve= 0
Exp/Cntr=.3,.1

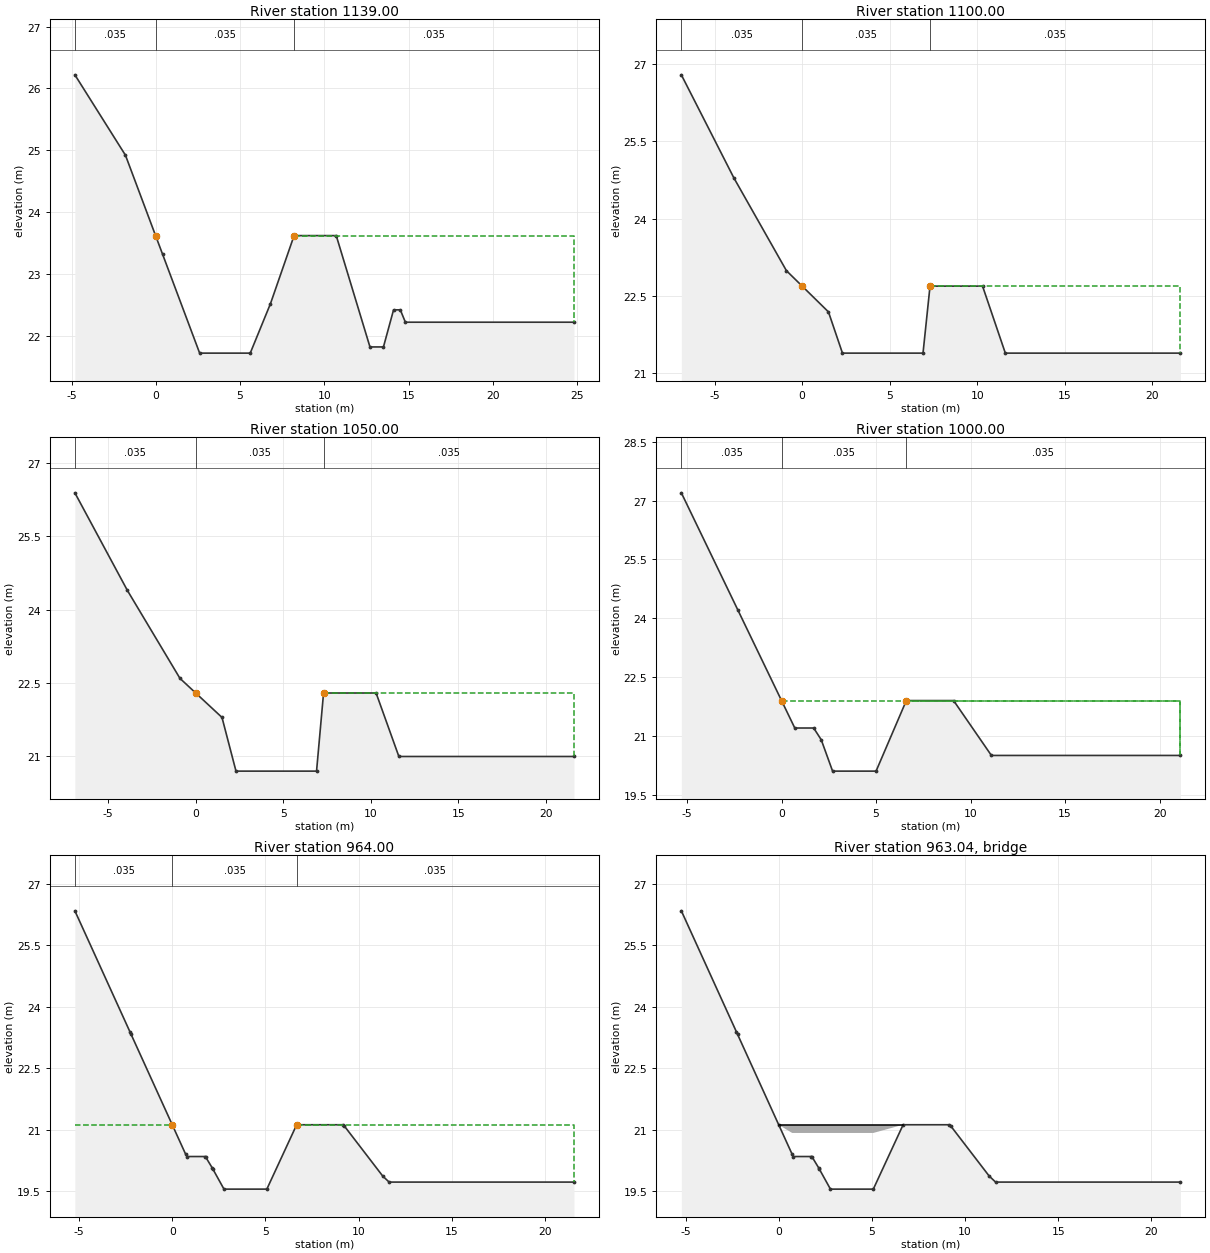
Type RM Length L Ch R = 1 ,1139.00 ,39,39,39
BEGIN DESCRIPTION:
22.039
END DESCRIPTION:
#Sta/Elev= 15
    -4.8   26.22    -1.8   24.92       0   23.61      .4   23.32     2.6   21.72
     5.6   21.72     6.8   22.52     8.2   23.62    10.7   23.62    12.7   21.82
    13.5   21.82    14.1   22.42    14.5   22.42    14.8   22.22    24.8   22.22
#Mann= 3 , 0 , 0
    -4.8    .035       0       0    .035       0     8.2    .035       0
#XS Ineff= 2 , 0
               0   23.61     8.2           23.62
Permanent Ineff=
       F       F
Bank Sta=0,8.2
XS Rating Curve= 0
Exp/Cntr=.3,.1

Type RM Length L Ch R = 1 ,1100.00 ,50,50,50
BEGIN DESCRIPTION:
22
END DESCRIPTION:
#Sta/Elev= 11
    -6.9   26.79    -3.9   24.79     -.9   22.99       0   22.69     1.5   22.19
     2.3   21.39     6.9   21.39     7.3   22.69    10.3   22.69    11.6   21.39
    21.6   21.39
#Mann= 3 , 0 , 0
    -6.9    .035       0       0    .035       0     7.3    .035       0
#XS Ineff= 2 , 0
               0   22.69     7.3           22.69
Permanent Ineff=
       F       F
Bank Sta=0,7.3
XS Rating Curve= 0
Exp/Cntr=.3,.1

Type RM Length L Ch R = 1 ,1050.00 ,50,50,50
BEGIN DESCRIPTION:
21
END DESCRIPTION:
#Sta/Elev= 11
    -6.9   26.39    -3.9   24.39     -.9   22.59       0   22.29     1.5   21.79
     2.3   20.69     6.9   20.69     7.3   22.29    10.3   22.29    11.6   20.99
    21.6   20.99
#Mann= 3 , 0 , 0
    -6.9    .035       0       0    .035       0     7.3    .035       0
#XS Ineff= 2 , 0
               0   22.29     7.3           22.29
Permanent Ineff=
       F       F
Bank Sta=0,7.3
XS Rating Curve= 0
Exp/Cntr=.3,.1

Type RM Length L Ch R = 1 ,1000.00 ,36,36,36
BEGIN DESCRIPTION:
20
END DESCRIPTION:
#Sta/Elev= 12
    -5.3    27.2    -2.3    24.2       0    21.9      .7    21.2     1.7    21.2
     2.1    20.9     2.7    20.1       5    20.1     6.6    21.9     9.1    21.9
    11.1    20.5    21.1    20.5
#Mann= 3 , 0 , 0
    -5.3    .035       0       0    .035       0     6.6    .035       0
#XS Ineff= 2 , 0
       0       0    21.9     6.6       0    21.9
Permanent Ineff=
       F       F
Bank Sta=0,6.6
XS Rating Curve= 0
Exp/Cntr=.3,.1

Type RM Length L Ch R = 1 ,964.00  ,2,2,2
BEGIN DESCRIPTION:
19.014
END DESCRIPTION:
#Sta/Elev= 18
  -5.224  26.341  -2.267  23.384   -2.21  23.327       0  21.117     .72  20.397
    .793  20.341   1.748  20.341   1.785  20.335   2.159  20.054   2.181  20.034
   2.776  19.545   5.076  19.545   6.676  21.117   9.156  21.117   9.242  21.081
  11.294  19.864  11.636  19.717  21.556  19.717
#Mann= 3 , 0 , 0
  -5.224    .035       0       0    .035       0   6.676    .035       0
#XS Ineff= 2 , 0
               0 21.1172   6.676         21.1172
Permanent Ineff=
       F       F
Bank Sta=0,6.676
XS Rating Curve= 0
Exp/Cntr=.3,.1

Type RM Length L Ch R = 3 ,963.04  ,,,
BEGIN DESCRIPTION:
19.013
END DESCRIPTION:
Bridge Culvert--1,0,-1,-1, 0
Deck Dist Width WeirC Skew NumUp NumDn MinLoCord MaxHiCord MaxSubmerge Is_Ogee
.01,1.9,1.44,0, 2, 2, , , .95, 0, 0,0,,
       0   6.676
  21.117  21.117
  20.917  20.917
       0   6.676
  21.117  21.117
  20.917  20.917
BR Coef=-1 , 1 , 0 ,, 0 ,,,.8,-1,1.2,0,
WSPro=,,,, 1 ,,,, 0 ,,,, 0 ,,,,-1 ,-1 ,-1 , 0 , 0 , 0 , 0 , 0
BC Design=,, 0 ,, 0 ,,,,,,

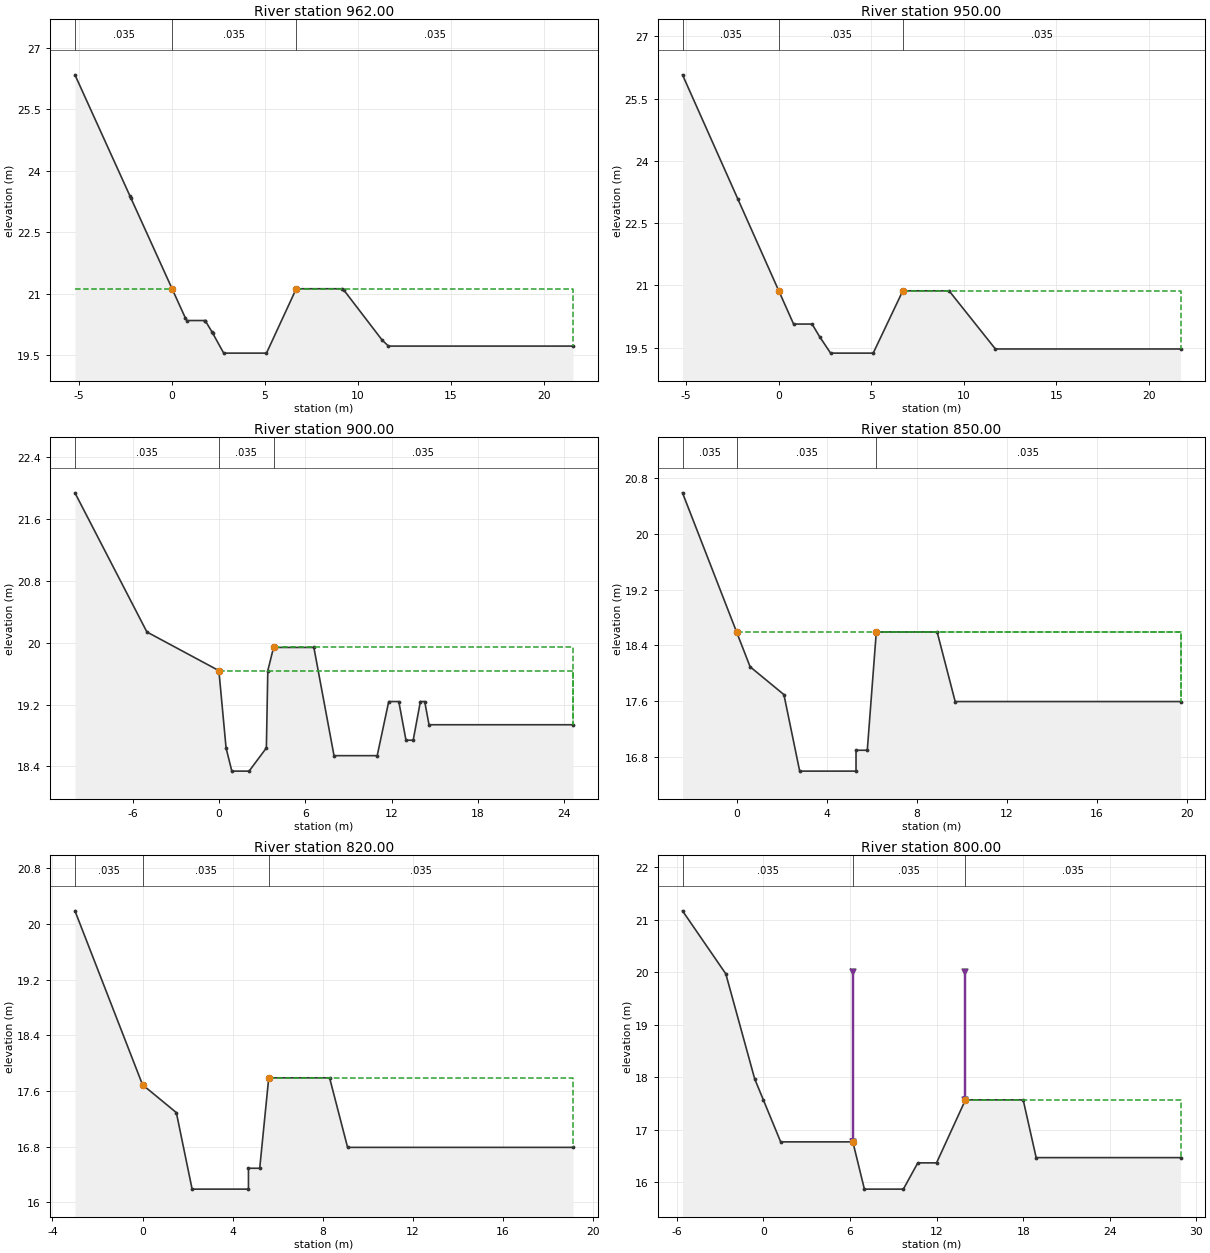
Type RM Length L Ch R = 1 ,962.00  ,12,12,12
BEGIN DESCRIPTION:
19.012
END DESCRIPTION:
#Sta/Elev= 18
  -5.224  26.341  -2.267  23.384   -2.21  23.327       0  21.117     .72  20.397
    .793  20.341   1.748  20.341   1.785  20.335   2.159  20.054   2.181  20.034
   2.776  19.545   5.076  19.545   6.676  21.117   9.156  21.117   9.242  21.081
  11.294  19.864  11.636  19.717  21.556  19.717
#Mann= 3 , 0 , 0
  -5.224    .035       0       0    .035       0   6.676    .035       0
#XS Ineff= 2 , 0
               0 21.1172   6.676         21.1172
Permanent Ineff=
       F       F
Bank Sta=0,6.676
XS Rating Curve= 0
Exp/Cntr=.3,.1

Type RM Length L Ch R = 1 ,950.00  ,50,50,50
BEGIN DESCRIPTION:
19
END DESCRIPTION:
#Sta/Elev= 12
    -5.2   26.07    -2.2   23.07       0   20.87      .8   20.07     1.8   20.07
     2.2   19.77     2.8   19.37     5.1   19.37     6.7   20.87     9.2   20.87
    11.7   19.47    21.7   19.47
#Mann= 3 , 0 , 0
    -5.2    .035       0       0    .035       0     6.7    .035       0
#XS Ineff= 2 , 0
               0   20.87     6.7           20.87
Permanent Ineff=
       F       F
Bank Sta=0,6.7
XS Rating Curve= 0
Exp/Cntr=.3,.1

Type RM Length L Ch R = 1 ,900.00  ,50,50,50
BEGIN DESCRIPTION:
18
END DESCRIPTION:
#Sta/Elev= 20
     -10   21.94      -5   20.14       0   19.64      .5   18.64      .9   18.34
     2.1   18.34     3.3   18.64     3.4   19.64     3.8   19.94     6.6   19.94
       8   18.54      11   18.54    11.8   19.24    12.5   19.24      13   18.74
    13.5   18.74      14   19.24    14.3   19.24    14.6   18.94    24.6   18.94
#Mann= 3 , 0 , 0
     -10    .035       0       0    .035       0     3.8    .035       0
#XS Ineff= 2 , 0
       0       0   19.64     3.8       0   19.94
Permanent Ineff=
       F       F
Bank Sta=0,3.8
XS Rating Curve= 0
Exp/Cntr=.3,.1

Type RM Length L Ch R = 1 ,850.00  ,30,30,30
BEGIN DESCRIPTION:
17
END DESCRIPTION:
#Sta/Elev= 12
    -2.4   20.59       0   18.59      .6   18.09     2.1   17.69     2.8   16.59
     5.3   16.59     5.3   16.89     5.8   16.89     6.2   18.59     8.9   18.59
     9.7   17.59    19.7   17.59
#Mann= 3 , 0 , 0
    -2.4    .035       0       0    .035       0     6.2    .035       0
#XS Ineff= 2 , 0
       0       0   18.59     6.2       0   18.59
Permanent Ineff=
       F       F
Bank Sta=0,6.2
XS Rating Curve= 0
Exp/Cntr=.3,.1

Type RM Length L Ch R = 1 ,820.00  ,20,20,20
BEGIN DESCRIPTION:
16.02
END DESCRIPTION:
#Sta/Elev= 11
      -3   20.19       0   17.69     1.5   17.29     2.2   16.19     4.7   16.19
     4.7   16.49     5.2   16.49     5.6   17.79     8.3   17.79     9.1   16.79
    19.1   16.79
#Mann= 3 , 0 , 0
      -3    .035       0       0    .035       0     5.6    .035       0
#XS Ineff= 2 , 0
               0   17.69     5.6           17.79
Permanent Ineff=
       F       F
Bank Sta=0,5.6
XS Rating Curve= 0
Exp/Cntr=.3,.1

Type RM Length L Ch R = 1 ,800.00  ,50,50,50
BEGIN DESCRIPTION:
16
END DESCRIPTION:
#Sta/Elev= 14
    -5.6   21.17    -2.6   19.97     -.6   17.97       0   17.57     1.2   16.77
     6.2   16.77       7   15.87     9.7   15.87    10.7   16.37      12   16.37
      14   17.57      18   17.57    18.9   16.47    28.9   16.47
#Mann= 3 , 0 , 0
    -5.6    .035       0     6.2    .035       0      14    .035       0
Levee=-1,6.2,20,-1,14,20,,
#XS Ineff= 2 , 0
       0     6.2   16.77      14       0   17.57
Permanent Ineff=
       F       F
Bank Sta=6.2,14
XS Rating Curve= 0
Exp/Cntr=.3,.1

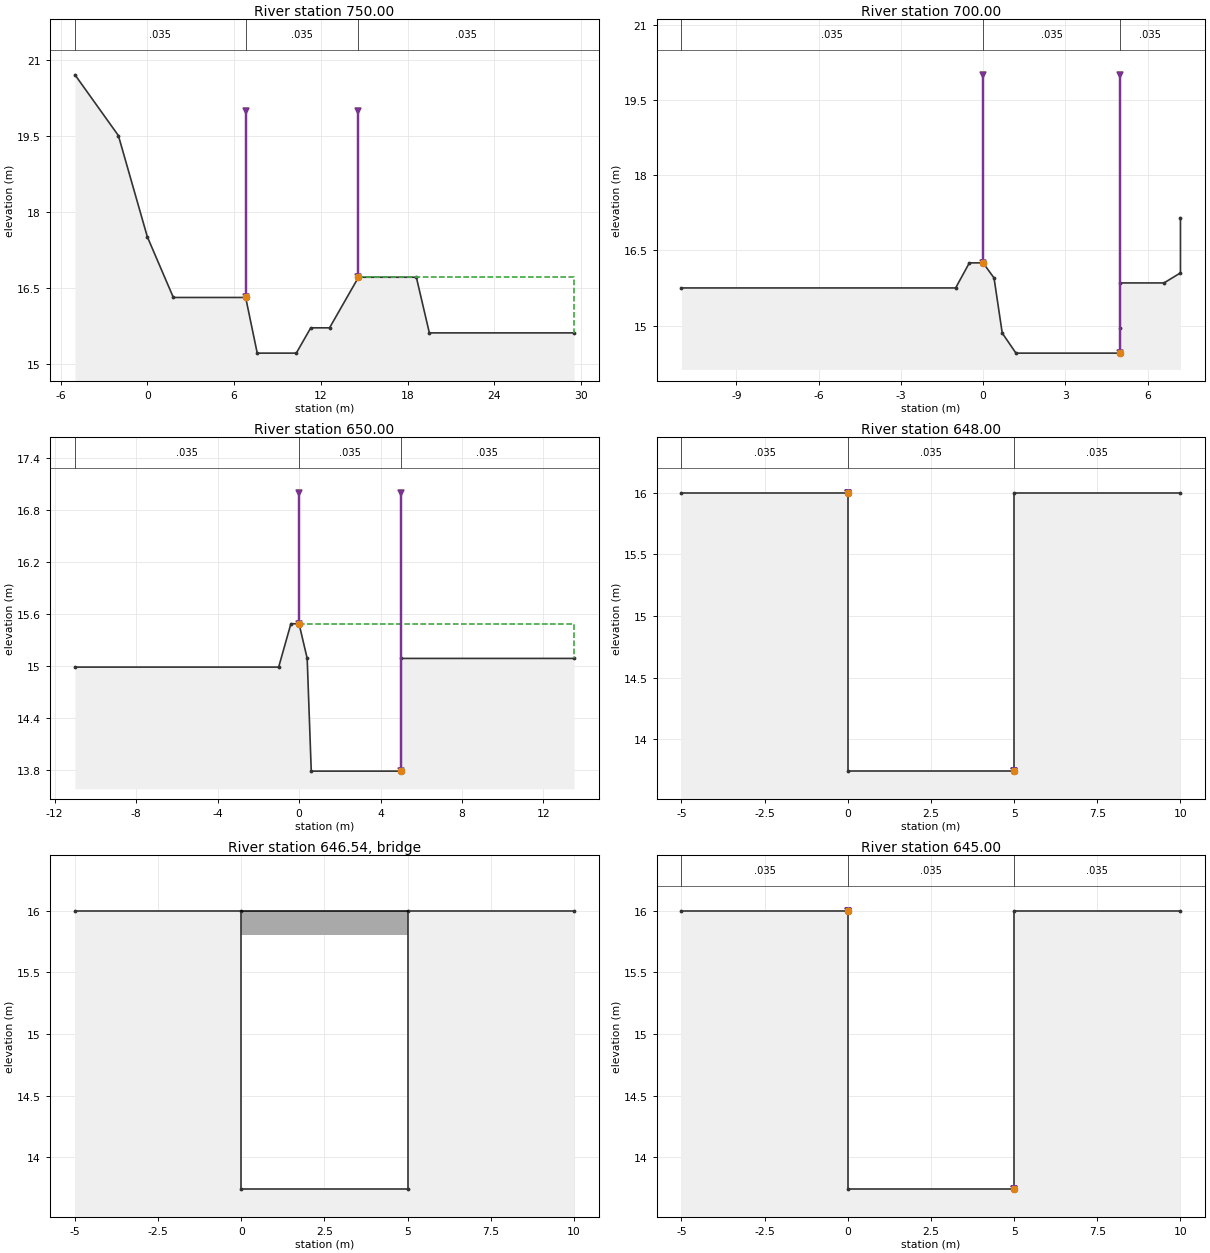
Type RM Length L Ch R = 1 ,750.00  ,50,50,50
BEGIN DESCRIPTION:
15
END DESCRIPTION:
#Sta/Elev= 13
      -5   20.71      -2   19.51       0   17.51     1.8   16.31     6.8   16.31
     7.6   15.21    10.3   15.21    11.3   15.71    12.6   15.71    14.6   16.71
    18.6   16.71    19.5   15.61    29.5   15.61
#Mann= 3 , 0 , 0
      -5    .035       0     6.8    .035       0    14.6    .035       0
Levee=-1,6.8,20,-1,14.6,20,,
#XS Ineff= 2 , 0
       0     6.8   16.31    14.6       0   16.71
Permanent Ineff=
       F       F
Bank Sta=6.8,14.6
XS Rating Curve= 0
Exp/Cntr=.3,.1

Type RM Length L Ch R = 1 ,700.00  ,50,50,50
BEGIN DESCRIPTION:
14
END DESCRIPTION:
#Sta/Elev= 13
     -11   15.75      -1   15.75     -.5   16.25       0   16.25      .4   15.95
      .7   14.85     1.2   14.45       5   14.45       5   14.95       5   15.85
     6.6   15.85     7.2   16.05     7.2   17.15
#Mann= 3 , 0 , 0
     -11    .035       0       0    .035       0       5    .035       0
Levee=-1,0,20,-1,5,20,,
Bank Sta=0,5
XS Rating Curve= 0
Exp/Cntr=.3,.1

Type RM Length L Ch R = 1 ,650.00  ,2,2,2
BEGIN DESCRIPTION:
13
END DESCRIPTION:
#Sta/Elev= 9
     -11   14.99      -1   14.99     -.4   15.49       0   15.49      .4   15.09
      .6   13.79       5   13.79       5   15.09    13.5   15.09
#Mann= 3 , 0 , 0
     -11    .035       0       0    .035       0       5    .035       0
Levee=-1,0,17,-1,5,17,,
#XS Ineff= 2 , 0
       0       0   15.49       5       0   13.79
Permanent Ineff=
       F       F
Bank Sta=0,5
XS Rating Curve= 0
Exp/Cntr=.3,.1

Type RM Length L Ch R = 1 ,648.00  ,3,3,3
BEGIN DESCRIPTION:
12.048
END DESCRIPTION:
#Sta/Elev= 6
      -5      16       0      16       0   13.74       5   13.74       5      16
      10      16
#Mann= 3 , 0 , 0
      -5    .035       0       0    .035       0       5    .035       0
Levee=-1,0,16,-1,5,13.74,,
#XS Ineff= 2 , 0
       0       0      16       5       0   13.74
Permanent Ineff=
       F       F
Bank Sta=0,5
XS Rating Curve= 0
Exp/Cntr=.3,.1

Type RM Length L Ch R = 3 ,646.54  ,,,
BEGIN DESCRIPTION:
12.0465
END DESCRIPTION:
Bridge Culvert--1,0,-1,-1, 0
Deck Dist Width WeirC Skew NumUp NumDn MinLoCord MaxHiCord MaxSubmerge Is_Ogee
.01,2.9,1.44,0, 2, 2, , , .95, 0, 0,0,,
       0       5
      16      16
    15.8    15.8
       0       5
      16      16
    15.8    15.8
BR Coef=-1 , 1 , 0 ,, 0 ,,,.8,-1,1.2,0,
WSPro=,,,, 1 ,,,, 0 ,,,, 0 ,,,,-1 ,-1 ,-1 , 0 , 0 , 0 , 0 , 0
BC Design=,, 0 ,, 0 ,,,,,,

Type RM Length L Ch R = 1 ,645.00  ,20,20,20
BEGIN DESCRIPTION:
12.045
END DESCRIPTION:
#Sta/Elev= 6
      -5      16       0      16       0   13.74       5   13.74       5      16
      10      16
#Mann= 3 , 0 , 0
      -5    .035       0       0    .035       0       5    .035       0
Levee=-1,0,16,-1,5,13.74,,
#XS Ineff= 2 , 0
       0       0      16       5       0   13.74
Permanent Ineff=
       F       F
Bank Sta=0,5
XS Rating Curve= 0
Exp/Cntr=.3,.1

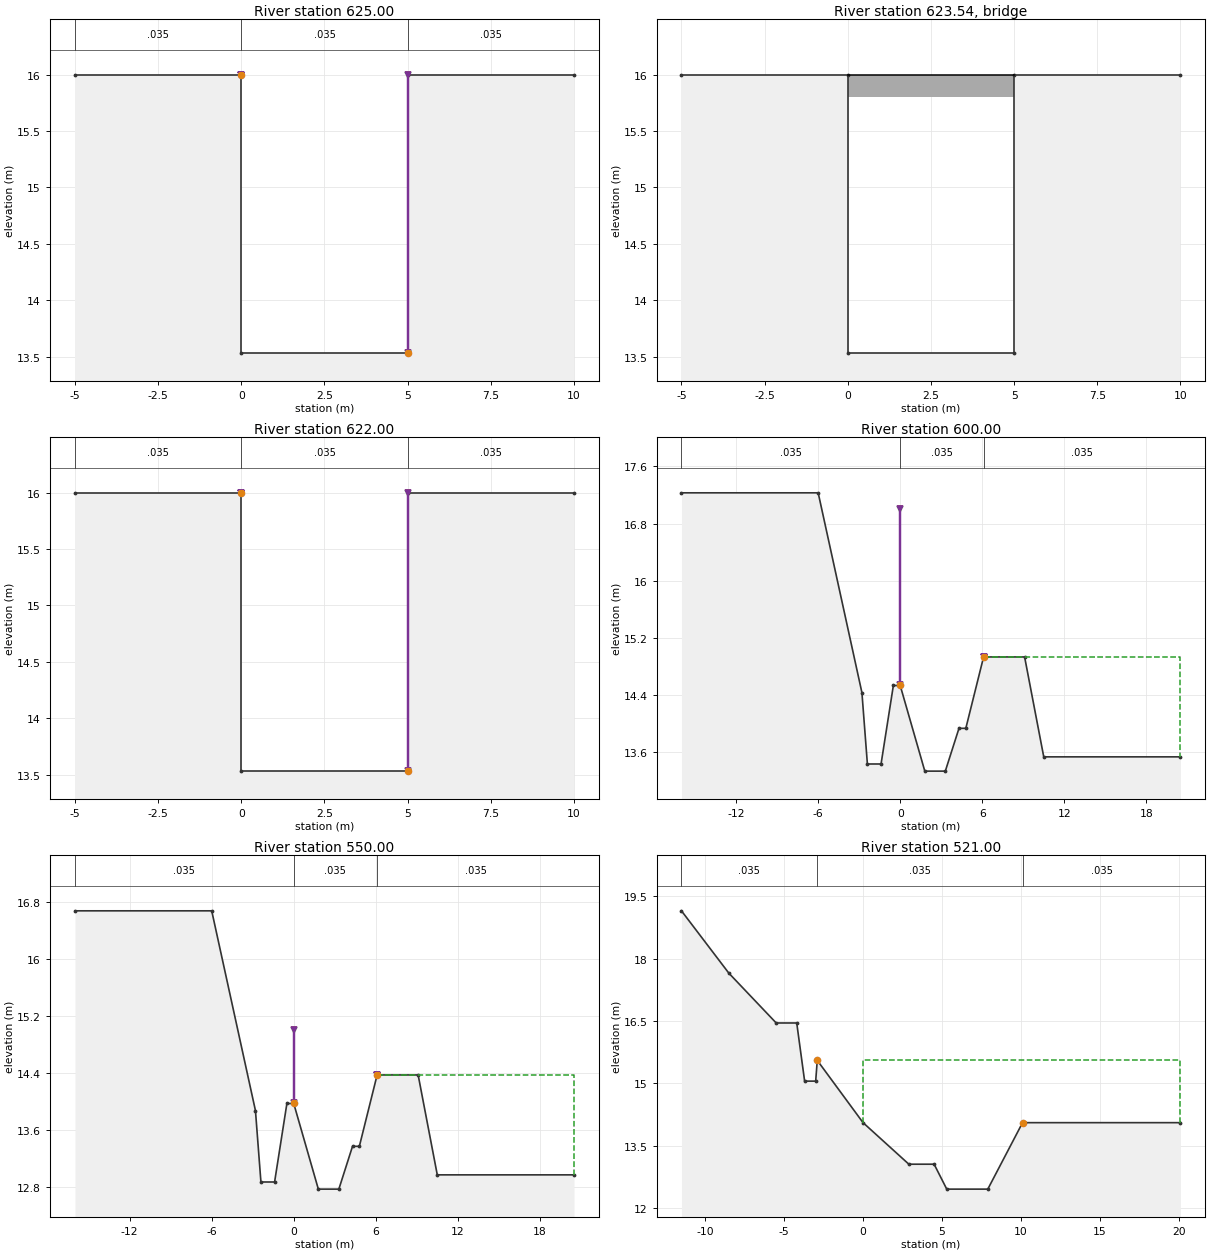
Type RM Length L Ch R = 1 ,625.00  ,3,3,3
BEGIN DESCRIPTION:
12.025
END DESCRIPTION:
#Sta/Elev= 6
      -5      16       0      16       0   13.53       5   13.53       5      16
      10      16
#Mann= 3 , 0 , 0
      -5    .035       0       0    .035       0       5    .035       0
Levee=-1,0,16,-1,5,16,,
Bank Sta=0,5
XS Rating Curve= 0
Exp/Cntr=.3,.1

Type RM Length L Ch R = 3 ,623.54  ,,,
BEGIN DESCRIPTION:
12.0235
END DESCRIPTION:
Bridge Culvert--1,0,-1,-1, 0
Deck Dist Width WeirC Skew NumUp NumDn MinLoCord MaxHiCord MaxSubmerge Is_Ogee
.01,2.9,1.44,0, 2, 2, , , .95, 0, 0,0,,
       0       5
      16      16
    15.8    15.8
       0       5
      16      16
    15.8    15.8
BR Coef=-1 , 1 , 0 ,, 0 ,,,.8,-1,1.2,0,
WSPro=,,,, 1 ,,,, 0 ,,,, 0 ,,,,-1 ,-1 ,-1 , 0 , 0 , 0 , 0 , 0
BC Design=,, 0 ,, 0 ,,,,,,

Type RM Length L Ch R = 1 ,622.00  ,22,22,22
BEGIN DESCRIPTION:
12.022
END DESCRIPTION:
#Sta/Elev= 6
      -5      16       0      16       0   13.53       5   13.53       5      16
      10      16
#Mann= 3 , 0 , 0
      -5    .035       0       0    .035       0       5    .035       0
Levee=-1,0,16,-1,5,16,,
Bank Sta=0,5
XS Rating Curve= 0
Exp/Cntr=.3,.1

Type RM Length L Ch R = 1 ,600.00  ,50,50,50
BEGIN DESCRIPTION:
12
END DESCRIPTION:
#Sta/Elev= 15
     -16   17.23      -6   17.23    -2.8   14.43    -2.4   13.43    -1.4   13.43
     -.5   14.53       0   14.53     1.8   13.33     3.3   13.33     4.3   13.93
     4.8   13.93     6.1   14.93     9.1   14.93    10.5   13.53    20.5   13.53
#Mann= 3 , 0 , 0
     -16    .035       0       0    .035       0     6.1    .035       0
Levee=-1,0,17,-1,6.1,14.93,,
#XS Ineff= 2 , 0
               0   14.53     6.1           14.93
Permanent Ineff=
       F       F
Bank Sta=0,6.1
XS Rating Curve= 0
Exp/Cntr=.3,.1

Type RM Length L Ch R = 1 ,550.00  ,29,29,29
BEGIN DESCRIPTION:
11
END DESCRIPTION:
#Sta/Elev= 15
     -16   16.67      -6   16.67    -2.8   13.87    -2.4   12.87    -1.4   12.87
     -.5   13.97       0   13.97     1.8   12.77     3.3   12.77     4.3   13.37
     4.8   13.37     6.1   14.37     9.1   14.37    10.5   12.97    20.5   12.97
#Mann= 3 , 0 , 0
     -16    .035       0       0    .035       0     6.1    .035       0
Levee=-1,0,15,-1,6.1,14.37,,
#XS Ineff= 2 , 0
               0   13.97     6.1           14.37
Permanent Ineff=
       F       F
Bank Sta=0,6.1
XS Rating Curve= 0
Exp/Cntr=.3,.1

Type RM Length L Ch R = 1 ,521.00  ,21,21,21
BEGIN DESCRIPTION:
10.021
END DESCRIPTION:
#Sta/Elev= 14
   -11.5   19.15    -8.5   17.65    -5.5   16.45    -4.2   16.45    -3.7   15.05
      -3   15.05    -2.9   15.55       0   14.05     2.9   13.05     4.5   13.05
     5.3   12.45     7.9   12.45    10.1   14.05    20.1   14.05
#Mann= 3 , 0 , 0
   -11.5    .035       0    -2.9    .035       0    10.1    .035       0
#XS Ineff= 2 , 0
       0    -2.9   15.55    10.1       0   14.05
Permanent Ineff=
       F       F
Bank Sta=-2.9,10.1
XS Rating Curve= 0
Exp/Cntr=.3,.1

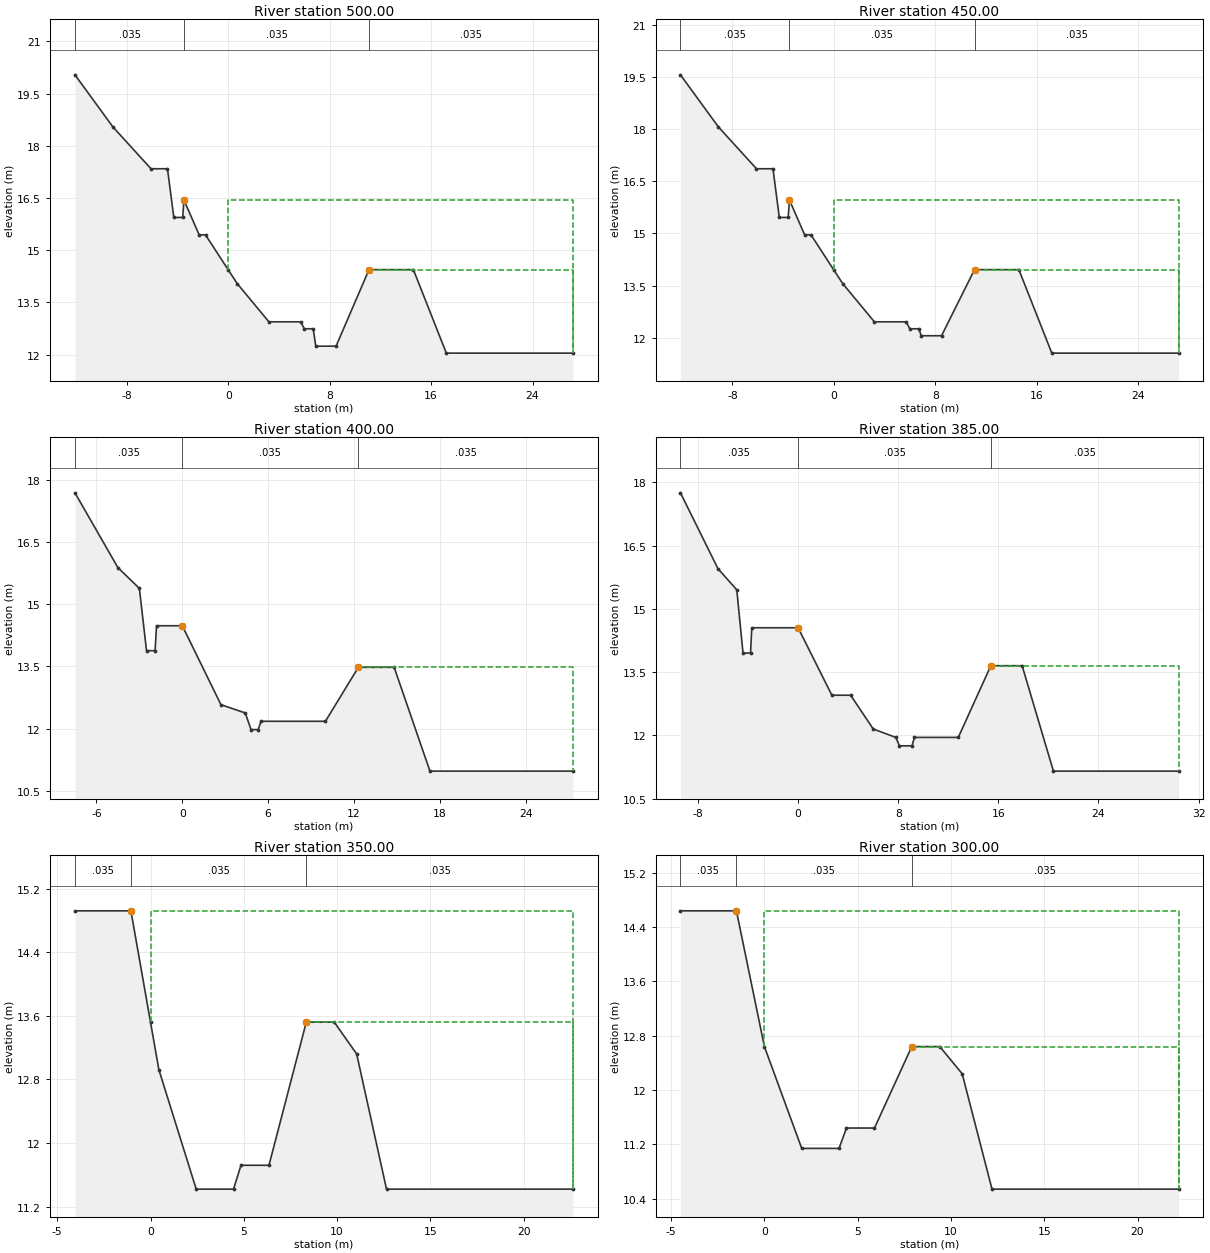
Type RM Length L Ch R = 1 ,500.00  ,50,50,50
BEGIN DESCRIPTION:
10
END DESCRIPTION:
#Sta/Elev= 21
   -12.1   20.04    -9.1   18.54    -6.1   17.34    -4.8   17.34    -4.3   15.94
    -3.6   15.94    -3.5   16.44    -2.3   15.44    -1.8   15.44       0   14.43
      .7   14.04     3.2   12.94     5.7   12.94       6   12.74     6.7   12.74
     6.9   12.24     8.5   12.24    11.1   14.44    14.6   14.44    17.2   12.04
    27.2   12.04
#Mann= 3 , 0 , 0
   -12.1    .035       0    -3.5    .035       0    11.1    .035       0
#XS Ineff= 2 , 0
       0    -3.5   16.44    11.1       0   14.44
Permanent Ineff=
       F       F
Bank Sta=-3.5,11.1
XS Rating Curve= 0
Exp/Cntr=.3,.1

Type RM Length L Ch R = 1 ,450.00  ,50,50,50
BEGIN DESCRIPTION:
9
END DESCRIPTION:
#Sta/Elev= 21
   -12.1   19.56    -9.1   18.06    -6.1   16.86    -4.8   16.86    -4.3   15.46
    -3.6   15.46    -3.5   15.96    -2.3   14.96    -1.8   14.96       0   13.95
      .7   13.56     3.2   12.46     5.7   12.46       6   12.26     6.7   12.26
     6.9   12.06     8.5   12.06    11.1   13.96    14.6   13.96    17.2   11.56
    27.2   11.56
#Mann= 3 , 0 , 0
   -12.1    .035       0    -3.5    .035       0    11.1    .035       0
#XS Ineff= 2 , 0
       0    -3.5   15.96    11.1       0   13.96
Permanent Ineff=
       F       F
Bank Sta=-3.5,11.1
XS Rating Curve= 0
Exp/Cntr=.3,.1

Type RM Length L Ch R = 1 ,400.00  ,15,15,15
BEGIN DESCRIPTION:
8
END DESCRIPTION:
#Sta/Elev= 17
    -7.5   17.68    -4.5   15.88      -3   15.38    -2.5   13.88    -1.9   13.88
    -1.8   14.48       0   14.48     2.7   12.58     4.4   12.38     4.8   11.98
     5.3   11.98     5.5   12.18      10   12.18    12.3   13.48    14.8   13.48
    17.3   10.98    27.3   10.98
#Mann= 3 , 0 , 0
    -7.5    .035       0       0    .035       0    12.3    .035       0
#XS Ineff= 2 , 0
               0   14.48    12.3           13.48
Permanent Ineff=
       F       F
Bank Sta=0,12.3
XS Rating Curve= 0
Exp/Cntr=.3,.1

Type RM Length L Ch R = 1 ,385.00  ,35,35,35
BEGIN DESCRIPTION:
7.035
END DESCRIPTION:
#Sta/Elev= 19
    -9.4   17.75    -6.4   15.95    -4.9   15.45    -4.4   13.95    -3.8   13.95
    -3.7   14.55       0   14.55     2.7   12.95     4.2   12.95       6   12.15
     7.8   11.95     8.1   11.75     9.1   11.75     9.3   11.95    12.8   11.95
    15.4   13.65    17.9   13.65    20.4   11.15    30.4   11.15
#Mann= 3 , 0 , 0
    -9.4    .035       0       0    .035       0    15.4    .035       0
#XS Ineff= 2 , 0
               0   14.55    15.4           13.65
Permanent Ineff=
       F       F
Bank Sta=0,15.4
XS Rating Curve= 0
Exp/Cntr=.3,.1

Type RM Length L Ch R = 1 ,350.00  ,50,50,50
BEGIN DESCRIPTION:
7
END DESCRIPTION:
#Sta/Elev= 13
   -4.05   14.92   -1.05   14.92       0   13.52     .45   12.92    2.45   11.42
    4.45   11.42    4.85   11.72    6.35   11.72    8.35   13.52    9.85   13.52
   11.05   13.12   12.65   11.42   22.65   11.42
#Mann= 3 , 0 , 0
   -4.05    .035       0   -1.05    .035       0    8.35    .035       0
#XS Ineff= 2 , 0
       0   -1.05   14.92    8.35       0   13.52
Permanent Ineff=
       F       F
Bank Sta=-1.05,8.35
XS Rating Curve= 0
Exp/Cntr=.3,.1

Type RM Length L Ch R = 1 ,300.00  ,50,50,50
BEGIN DESCRIPTION:
6
END DESCRIPTION:
#Sta/Elev= 12
    -4.5   14.64    -1.5   14.64       0   12.64       2   11.14       4   11.14
     4.4   11.44     5.9   11.44     7.9   12.64     9.4   12.64    10.6   12.24
    12.2   10.54    22.2   10.54
#Mann= 3 , 0 , 0
    -4.5    .035       0    -1.5    .035       0     7.9    .035       0
#XS Ineff= 2 , 0
       0    -1.5   14.64     7.9       0   12.64
Permanent Ineff=
       F       F
Bank Sta=-1.5,7.9
XS Rating Curve= 0
Exp/Cntr=.3,.1