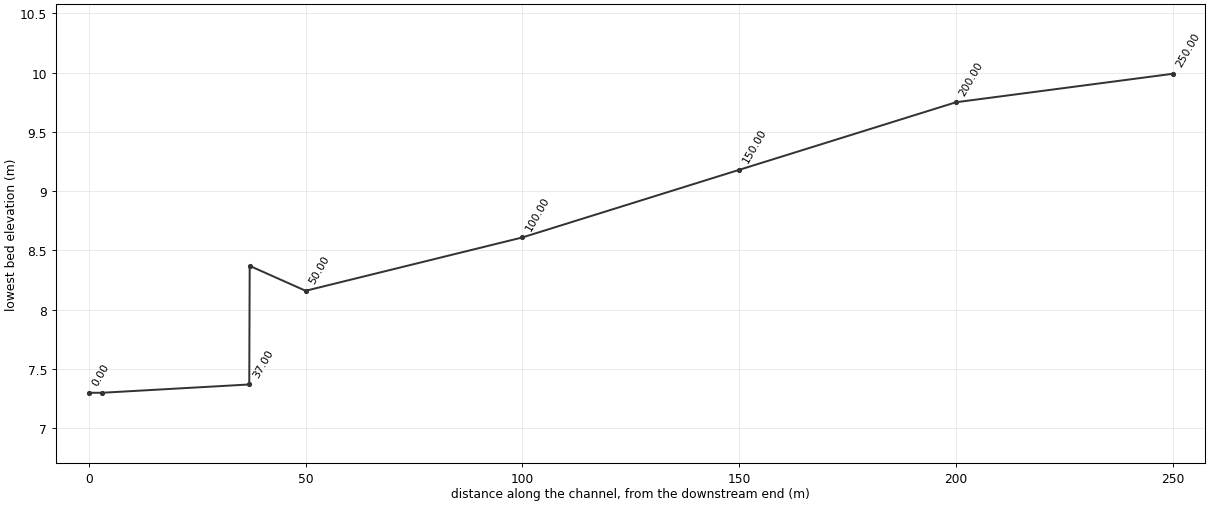
HEC-RAS study kzw.prj: kazawool-ch

--- kzw.g01 (geometry) --- (continued)

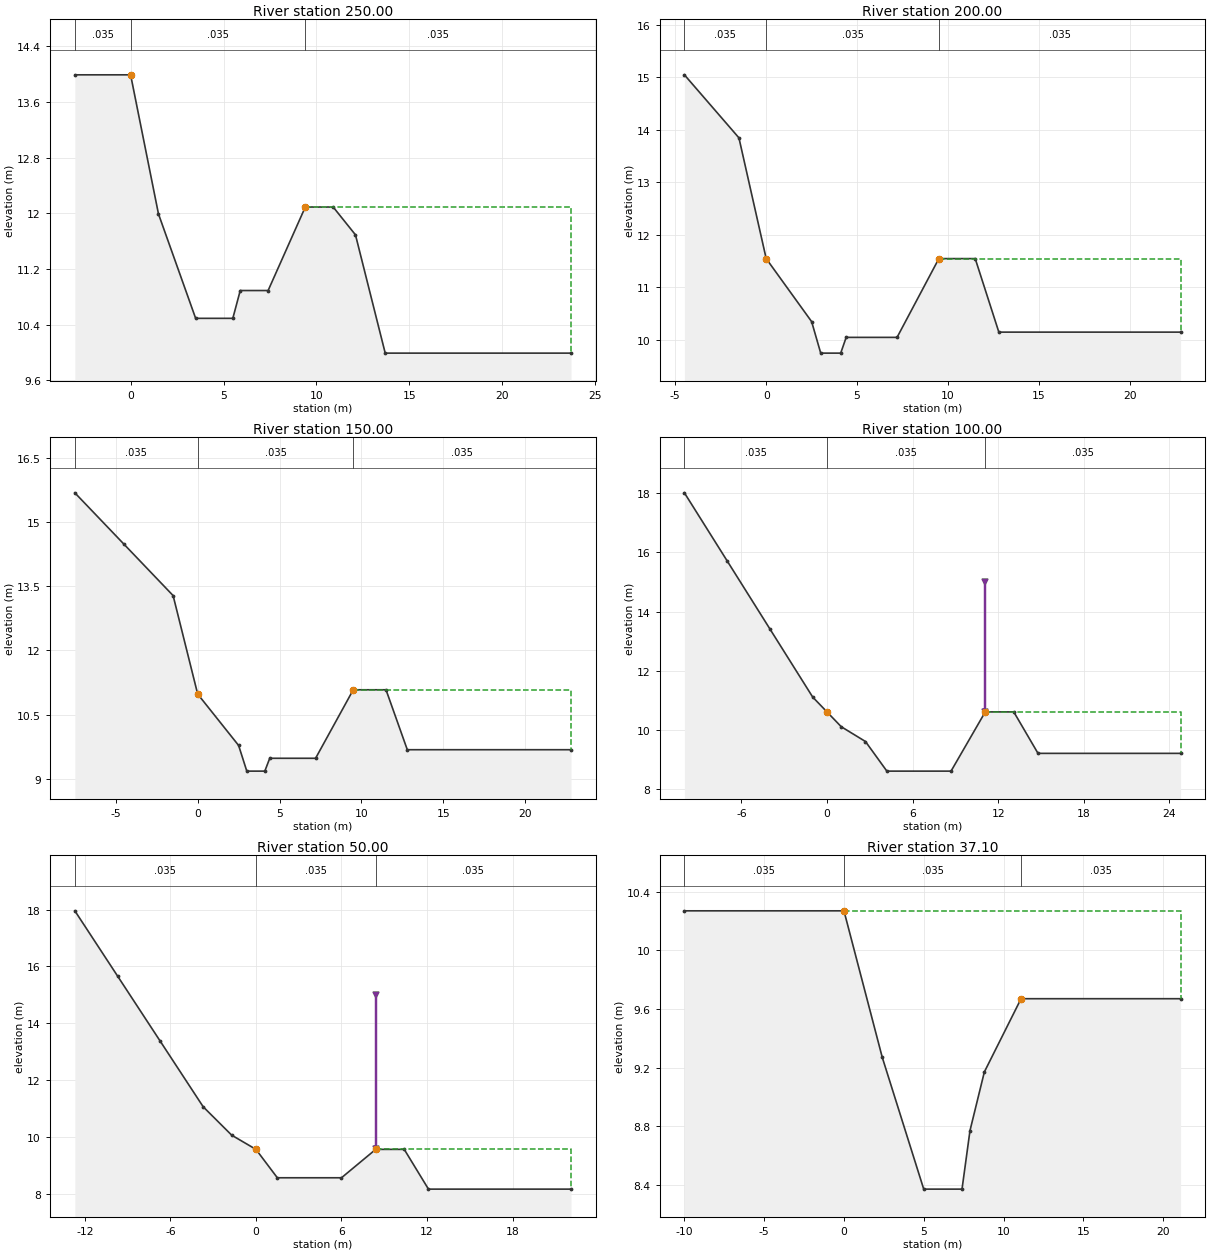
Type RM Length L Ch R = 1 ,250.00  ,50,50,50
BEGIN DESCRIPTION:
5
END DESCRIPTION:
#Sta/Elev= 12
      -3   13.99       0   13.99     1.5   11.99     3.5   10.49     5.5   10.49
     5.9   10.89     7.4   10.89     9.4   12.09    10.9   12.09    12.1   11.69
    13.7    9.99    23.7    9.99
#Mann= 3 , 0 , 0
      -3    .035       0       0    .035       0     9.4    .035       0
#XS Ineff= 2 , 0
               0   13.99     9.4           12.09
Permanent Ineff=
       F       F
Bank Sta=0,9.4
XS Rating Curve= 0
Exp/Cntr=.3,.1

Type RM Length L Ch R = 1 ,200.00  ,50,50,50
BEGIN DESCRIPTION:
4
END DESCRIPTION:
#Sta/Elev= 12
    -4.5   15.05    -1.5   13.85       0   11.55     2.5   10.35       3    9.75
     4.1    9.75     4.4   10.05     7.2   10.05     9.5   11.55    11.5   11.55
    12.8   10.15    22.8   10.15
#Mann= 3 , 0 , 0
    -4.5    .035       0       0    .035       0     9.5    .035       0
#XS Ineff= 2 , 0
               0   11.55     9.5           11.55
Permanent Ineff=
       F       F
Bank Sta=0,9.5
XS Rating Curve= 0
Exp/Cntr=.3,.1

Type RM Length L Ch R = 1 ,150.00  ,50,50,50
BEGIN DESCRIPTION:
3
END DESCRIPTION:
#Sta/Elev= 13
    -7.5   15.68    -4.5   14.48    -1.5   13.28       0   10.98     2.5    9.78
       3    9.18     4.1    9.18     4.4    9.48     7.2    9.48     9.5   11.08
    11.5   11.08    12.8    9.68    22.8    9.68
#Mann= 3 , 0 , 0
    -7.5    .035       0       0    .035       0     9.5    .035       0
#XS Ineff= 2 , 0
               0   10.98     9.5           11.08
Permanent Ineff=
       F       F
Bank Sta=0,9.5
XS Rating Curve= 0
Exp/Cntr=.3,.1

Type RM Length L Ch R = 1 ,100.00  ,50,50,50
BEGIN DESCRIPTION:
2
END DESCRIPTION:
#Sta/Elev= 13
     -10   18.01      -7   15.71      -4   13.41      -1   11.11       0   10.61
       1   10.11     2.7    9.61     4.2    8.61     8.7    8.61    11.1   10.61
    13.1   10.61    14.8    9.21    24.8    9.21
#Mann= 3 , 0 , 0
     -10    .035       0       0    .035       0    11.1    .035       0
Levee=0,,,-1,11.1,15,,
#XS Ineff= 2 , 0
               0   10.61    11.1           10.61
Permanent Ineff=
       F       F
Bank Sta=0,11.1
XS Rating Curve= 0
Exp/Cntr=.3,.1

Type RM Length L Ch R = 1 ,50.00   ,12.9,12.9,12.9
BEGIN DESCRIPTION:
1
END DESCRIPTION:
#Sta/Elev= 12
   -12.7   17.96    -9.7   15.66    -6.7   13.36    -3.7   11.06    -1.7   10.06
       0    9.56     1.5    8.56       6    8.56     8.4    9.56    10.4    9.56
    12.1    8.16    22.1    8.16
#Mann= 3 , 0 , 0
   -12.7    .035       0       0    .035       0     8.4    .035       0
Levee=0,,,-1,8.4,15,,
#XS Ineff= 2 , 0
               0    9.56     8.4            9.56
Permanent Ineff=
       F       F
Bank Sta=0,8.4
XS Rating Curve= 0
Exp/Cntr=.3,.1

Type RM Length L Ch R = 1 ,37.10   ,.1,.1,.1
BEGIN DESCRIPTION:
0.0371
END DESCRIPTION:
#Sta/Elev= 9
     -10   10.27       0   10.27     2.4    9.27       5    8.37     7.4    8.37
     7.9    8.77     8.8    9.17    11.1    9.67    21.1    9.67
#Mann= 3 , 0 , 0
     -10    .035       0       0    .035       0    11.1    .035       0
#XS Ineff= 2 , 0
       0       0   10.27    11.1       0    9.67
Permanent Ineff=
       F       F
Bank Sta=0,11.1
XS Rating Curve= 0
Exp/Cntr=.3,.1

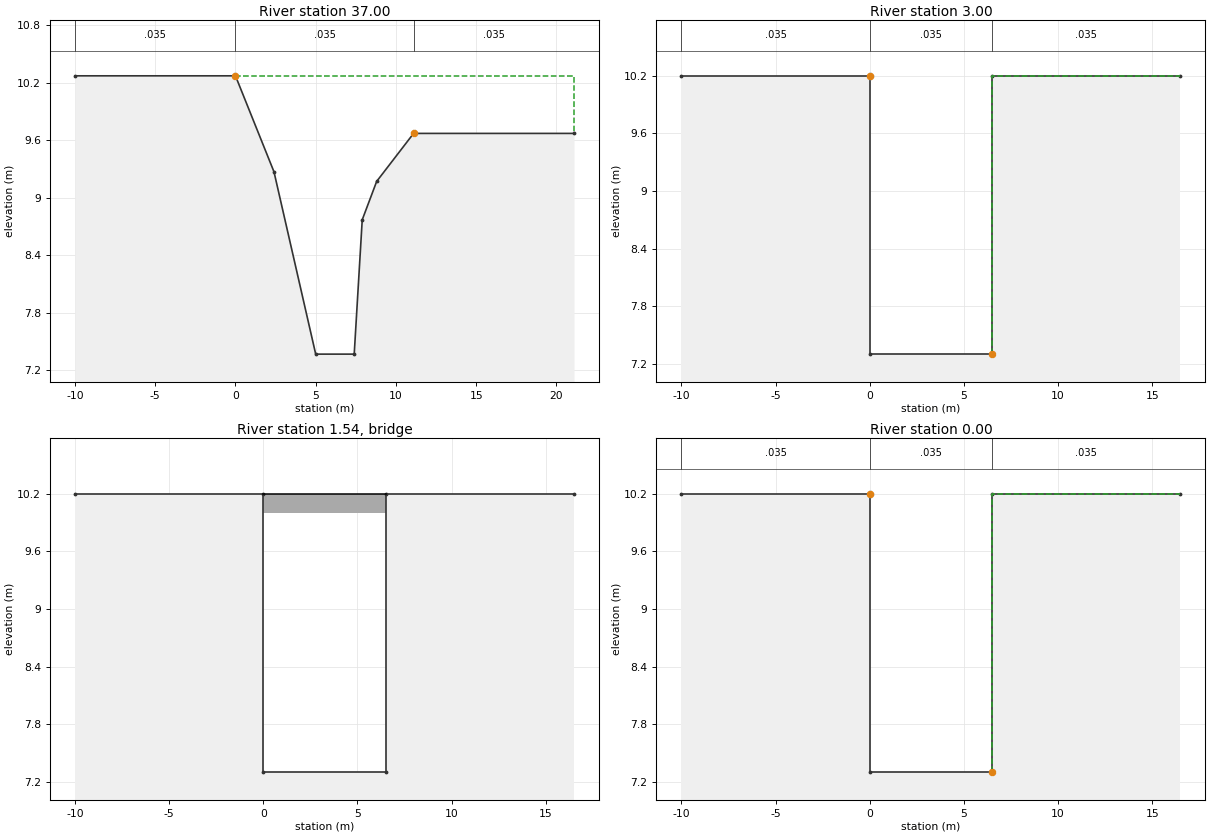
Type RM Length L Ch R = 1 ,37.00   ,34,34,34
BEGIN DESCRIPTION:
0.037
END DESCRIPTION:
#Sta/Elev= 9
     -10   10.27       0   10.27     2.4    9.27       5    7.37     7.4    7.37
     7.9    8.77     8.8    9.17    11.1    9.67    21.1    9.67
#Mann= 3 , 0 , 0
     -10    .035       0       0    .035       0    11.1    .035       0
#XS Ineff= 2 , 0
       0       0   10.27    11.1       0    9.67
Permanent Ineff=
       F       F
Bank Sta=0,11.1
XS Rating Curve= 0
Exp/Cntr=.3,.1

Type RM Length L Ch R = 1 ,3.00    ,3,3,3
BEGIN DESCRIPTION:
0.003
END DESCRIPTION:
#Sta/Elev= 6
     -10    10.2       0    10.2       0     7.3     6.5     7.3     6.5    10.2
    16.5    10.2
#Mann= 3 , 0 , 0
     -10    .035       0       0    .035       0     6.5    .035       0
#XS Ineff= 2 , 0
               0    10.2     6.5            10.2
Permanent Ineff=
       F       F
Bank Sta=0,6.5
XS Rating Curve= 0
Exp/Cntr=.3,.1

Type RM Length L Ch R = 3 ,1.54    ,,,
BEGIN DESCRIPTION:
0.0015
END DESCRIPTION:
Bridge Culvert--1,0,-1,-1, 0
Deck Dist Width WeirC Skew NumUp NumDn MinLoCord MaxHiCord MaxSubmerge Is_Ogee
.01,2.9,1.44,0, 2, 2, , , .95, 0, 0,0,,
       0     6.5
    10.2    10.2
      10      10
       0     6.5
    10.2    10.2
      10      10
BR Coef=-1 , 1 , 0 ,, 0 ,,,.8,-1,1.2,0,
WSPro=,,,, 1 ,,,, 0 ,,,, 0 ,,,,-1 ,-1 ,-1 , 0 , 0 , 0 , 0 , 0
BC Design=,, 0 ,, 0 ,,,,,,

Type RM Length L Ch R = 1 ,0.00    ,0,0,0
BEGIN DESCRIPTION:
0
END DESCRIPTION:
#Sta/Elev= 6
     -10    10.2       0    10.2       0     7.3     6.5     7.3     6.5    10.2
    16.5    10.2
#Mann= 3 , 0 , 0
     -10    .035       0       0    .035       0     6.5    .035       0
#XS Ineff= 2 , 0
               0    10.2     6.5            10.2
Permanent Ineff=
       F       F
Bank Sta=0,6.5
XS Rating Curve= 0
Exp/Cntr=.3,.1

Chan Stop Cuts=-1