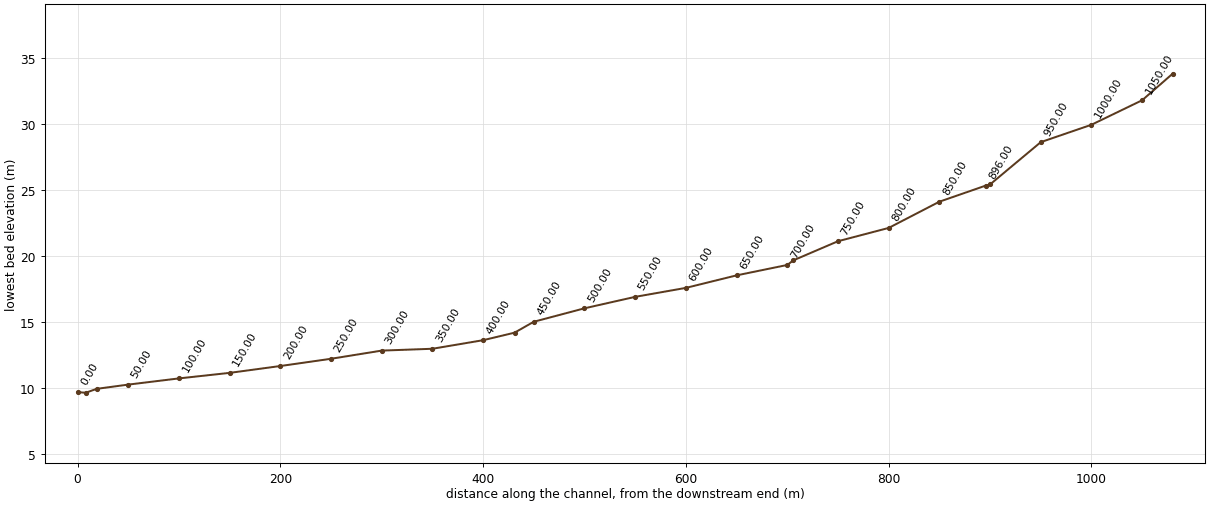
--- hnc.prj (project) ---

Proj Title=hannae-ch
Current Plan=p01
Default Exp/Contr=.3,.1
SI Units
Geom File=g01
Flow File=f01
Plan File=p01
Y Axis Title=Elevation
X Axis Title(PF)=Main Channel Distance
X Axis Title(XS)=Station
BEGIN DESCRIPTION:
           BACK WATER COMPUTATION
      APPLICATION OF HEC-2 BY Samju Construction Engineering
      ÇÑ³»Ãµ(¿ËÃµÀ¾): 30,50,80,100,150³âºóµµ °³¼öÀü
END DESCRIPTION:
DSS Export Rating Curves= 0
DSS Export Rating Curve Sorted= 0
DSS Export Volume Flow Curves= 0
DXF OffsetX= 0
DXF OffsetY= 0
DXF ScaleX= 1
DXF ScaleY= 10

--- hnc.p01 (plan) ---

Plan Title=Imported Plan 01
Version=Version 3.0.1  Mar 2001
Short Identifier=Imported Pla
Geom File=g01
Flow File=f01
Subcritical Flow
K Sum by GR= 0
Std Step Tol= 0.003
Critical Tol= 0.003
Num of Std Step Trials= 20
Max Error Tol= 0.1
Flow Tol Ratio= 0.001
Split Flow NTrial= 30
Split Flow Tol= 0.02
Split Flow Ratio= 0.02
Log Output Level= 0
Friction Slope Method= 1
Unsteady Friction Slope Method= 2
Parabolic Critical Depth
Global Vel Dist= 0 , 0 , 0
Global Log Level= 0
CheckData=True
Encroach Param=-1 ,0,0, 0
Computation Interval=1HOUR
Output Interval=1HOUR
Run HTab= 0
Run UNet= 0
Run PostProcess= 0
UNET Theta= 1
UNET ZTol= 0.02
UNET ZSATol= 0.1
UNET MxIter= 20
UNET MaxInSteps= 20
UNET DtIC= 0
UNET DtMin= 0
UNET MaxCRTS= 20
UNET WFStab= 2
UNET SFStab= 1
UNET WFX= 1
UNET SFX= 1
UNET Convert EG Bridges=-1
UNET Use Existing IB Tables=-1
Instantaneous Interval=1HOUR
Write IC File= 0
Write Velocity= 0
Write Detailed= 0

--- hnc.f01 (steady flow) ---

Flow Title=Imported Flow 01
Version=Version 3.0.1  Mar 2001
Number of Profiles= 5
Profile Names=10yr,20yr,30yr,50yr,80yr
River Rch & RM=RIVER-1,Reach-1         ,21.03
    7.54    8.32    8.77    9.33    9.86
River Rch & RM=hannae,hannae          ,1080.00
    7.54    8.32    8.77    9.33    9.86
Boundary for River Rch & Prof#=hannae,hannae          , 1
Up Type= 0
Dn Type= 3
Dn Slope=.023
Boundary for River Rch & Prof#=hannae,hannae          , 2
Up Type= 0
Dn Type= 3
Dn Slope=.023
Boundary for River Rch & Prof#=hannae,hannae          , 3
Up Type= 0
Dn Type= 3
Dn Slope=.023
Boundary for River Rch & Prof#=hannae,hannae          , 4
Up Type= 0
Dn Type= 3
Dn Slope=.023
Boundary for River Rch & Prof#=hannae,hannae          , 5
Up Type= 0
Dn Type= 3
Dn Slope=.023
DSS Import GetInterval= 0
DSS Import GetPeak= 0
DSS Import FillOption= 0

--- hnc.g01 (geometry) ---

Geom Title=Imported Geom 01
Version=Version 3.0.1  Mar 2001

River Reach=hannae          ,hannae
Reach XY= 2
              .5             .95              .5             .05

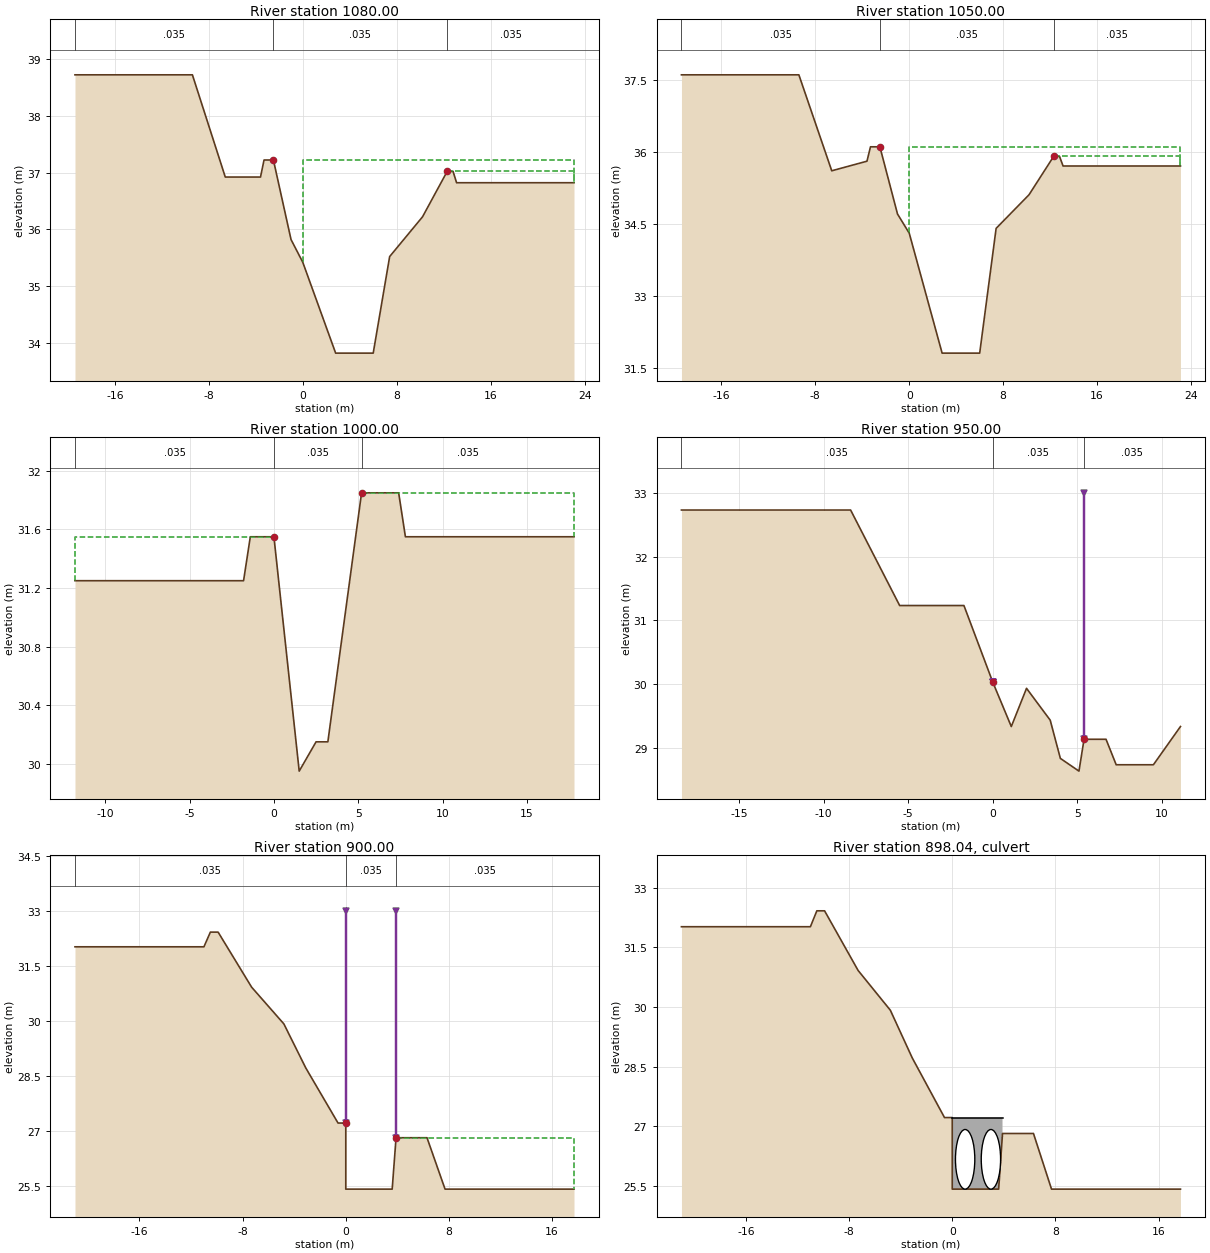
Type RM Length L Ch R = 1 ,1080.00 ,30,30,30
BEGIN DESCRIPTION:
21.03
END DESCRIPTION:
#Sta/Elev= 16
   -19.4   38.72    -9.4   38.72    -6.6   36.92    -3.6   36.92    -3.3   37.22
    -2.5   37.22      -1   35.82       0   35.42     2.8   33.82       6   33.82
     7.4   35.52    10.2   36.22    12.3   37.02    12.8   37.02    13.1   36.82
    23.1   36.82
#Mann= 3 , 0 , 0
   -19.4    .035       0    -2.5    .035       0    12.3    .035       0
#XS Ineff= 2 , 0
       0    -2.5   37.22    12.3       0   37.02
Permanent Ineff=
       F       F
Bank Sta=-2.5,12.3
XS Rating Curve= 0
Exp/Cntr=.3,.1

Type RM Length L Ch R = 1 ,1050.00 ,50,50,50
BEGIN DESCRIPTION:
21
END DESCRIPTION:
#Sta/Elev= 16
   -19.4   37.61    -9.4   37.61    -6.6   35.61    -3.6   35.81    -3.3   36.11
    -2.5   36.11      -1   34.71       0   34.31     2.8   31.81       6   31.81
     7.4   34.41    10.2   35.11    12.3   35.91    12.8   35.91    13.1   35.71
    23.1   35.71
#Mann= 3 , 0 , 0
   -19.4    .035       0    -2.5    .035       0    12.3    .035       0
#XS Ineff= 2 , 0
       0    -2.5   36.11    12.3       0   35.91
Permanent Ineff=
       F       F
Bank Sta=-2.5,12.3
XS Rating Curve= 0
Exp/Cntr=.3,.1

Type RM Length L Ch R = 1 ,1000.00 ,50,50,50
BEGIN DESCRIPTION:
20
END DESCRIPTION:
#Sta/Elev= 11
   -11.8   31.25    -1.8   31.25    -1.4   31.55       0   31.55     1.5   29.95
     2.5   30.15     3.2   30.15     5.2   31.85     7.4   31.85     7.8   31.55
    17.8   31.55
#Mann= 3 , 0 , 0
   -11.8    .035       0       0    .035       0     5.2    .035       0
#XS Ineff= 2 , 0
               0   31.55     5.2           31.85
Permanent Ineff=
       F       F
Bank Sta=0,5.2
XS Rating Curve= 0
Exp/Cntr=.3,.1

Type RM Length L Ch R = 1 ,950.00  ,50,50,50
BEGIN DESCRIPTION:
19
END DESCRIPTION:
#Sta/Elev= 15
   -18.4   32.73    -8.4   32.73    -5.5   31.23    -1.7   31.23       0   30.03
     1.1   29.33       2   29.93     3.4   29.43       4   28.83     5.1   28.63
     5.4   29.13     6.7   29.13     7.3   28.73     9.5   28.73    11.1   29.33
#Mann= 3 , 0 , 0
   -18.4    .035       0       0    .035       0     5.4    .035       0
Levee=-1,0,30.03,-1,5.4,33,,
#XS Ineff= 2 , 0
               0   30.03     5.4           29.13
Permanent Ineff=
       F       F
Bank Sta=0,5.4
XS Rating Curve= 0
Exp/Cntr=.3,.1

Type RM Length L Ch R = 1 ,900.00  ,4,4,4
BEGIN DESCRIPTION:
18
END DESCRIPTION:
#Sta/Elev= 15
     -21   32.02     -11   32.02   -10.5   32.42    -9.9   32.42    -7.3   30.92
    -4.8   29.92    -3.1   28.72     -.6   27.22       0   27.22       0   25.42
     3.6   25.42     3.9   26.82     6.3   26.82     7.7   25.42    17.7   25.42
#Mann= 3 , 0 , 0
     -21    .035       0       0    .035       0     3.9    .035       0
Levee=-1,0,33,-1,3.9,33,,
#XS Ineff= 2 , 0
               0   27.22     3.9           26.82
Permanent Ineff=
       F       F
Bank Sta=0,3.9
XS Rating Curve= 0
Exp/Cntr=.3,.1

Type RM Length L Ch R = 2 ,898.04  ,,,
BEGIN DESCRIPTION:
17.048
END DESCRIPTION:
Bridge Culvert--1,0,-1,-1, 0
Deck Dist Width WeirC Skew NumUp NumDn MinLoCord MaxHiCord MaxSubmerge Is_Ogee
.01,3.9,1.44,0, 2, 2, , , .95, 0, 0,0,,
       0     3.9
   27.22   27.22
   25.42   25.42
       0     3.9
   27.22   26.82
   25.34   25.34
BR Coef=-1 , 1 , 1 ,.9, 0 ,,,.8,-1,1.2,0,
WSPro=,,,, 1 ,,,, 0 ,,,, 0 ,,,,-1 ,-1 ,-1 , 0 , 0 , 0 , 0 , 0
Multiple Barrel Culv=1,1.5,,4,.015,.2,1,1,1,25.42,25.34, 2,Culvert #1  , 0 ,0
       1       1       3       3
Culvert Bottom n=.015
BC Design=,, 0 ,, 0 ,,,,,,

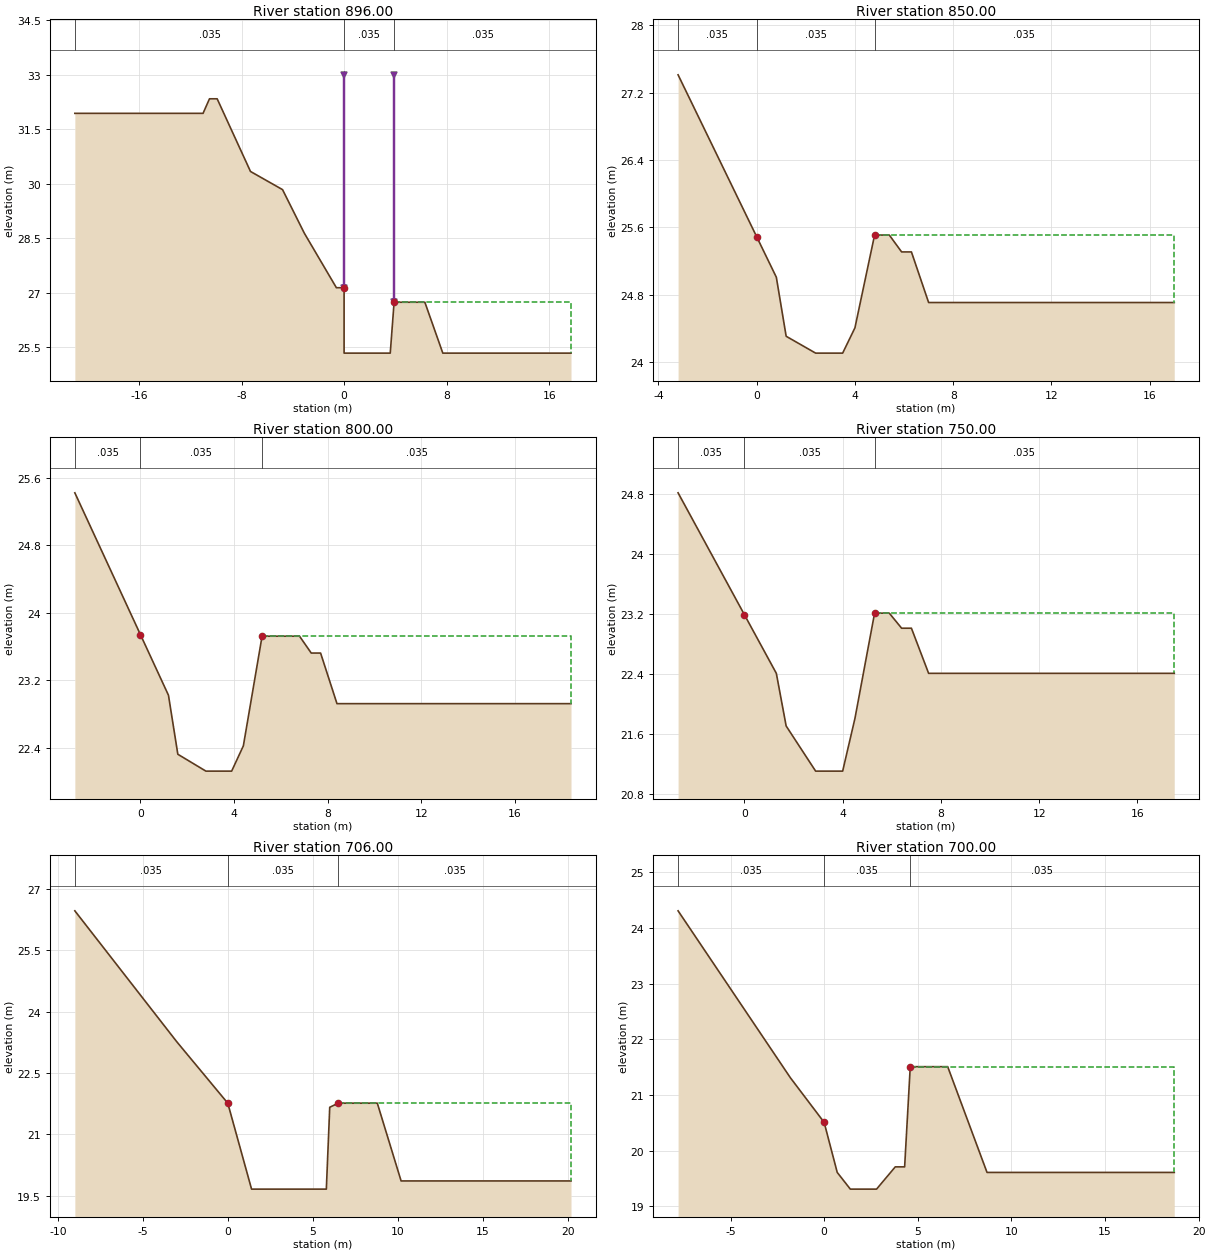
Type RM Length L Ch R = 1 ,896.00  ,46,46,46
BEGIN DESCRIPTION:
17.046
END DESCRIPTION:
#Sta/Elev= 15
     -21   31.94     -11   31.94   -10.5   32.34    -9.9   32.34    -7.3   30.34
    -4.8   29.84    -3.1   28.64     -.6   27.14       0   27.14       0   25.34
     3.6   25.34     3.9   26.74     6.3   26.74     7.7   25.34    17.7   25.34
#Mann= 3 , 0 , 0
     -21    .035       0       0    .035       0     3.9    .035       0
Levee=-1,0,33,-1,3.9,33,,
#XS Ineff= 2 , 0
               0   27.14     3.9           26.74
Permanent Ineff=
       F       F
Bank Sta=0,3.9
XS Rating Curve= 0
Exp/Cntr=.3,.1

Type RM Length L Ch R = 1 ,850.00  ,50,50,50
BEGIN DESCRIPTION:
17
END DESCRIPTION:
#Sta/Elev= 14
    -3.2   27.41    -1.2   26.21       0   25.49      .8   25.01     1.2   24.31
     2.4   24.11     3.5   24.11       4   24.41     4.8   25.51     5.4   25.51
     5.9   25.31     6.3   25.31       7   24.71      17   24.71
#Mann= 3 , 0 , 0
    -3.2    .035       0       0    .035       0     4.8    .035       0
#XS Ineff= 2 , 0
               0   25.49     4.8           25.51
Permanent Ineff=
       F       F
Bank Sta=0,4.8
XS Rating Curve= 0
Exp/Cntr=.3,.1

Type RM Length L Ch R = 1 ,800.00  ,50,50,50
BEGIN DESCRIPTION:
16
END DESCRIPTION:
#Sta/Elev= 14
    -2.8   25.42     -.8   24.22       0   23.74     1.2   23.02     1.6   22.32
     2.8   22.12     3.9   22.12     4.4   22.42     5.2   23.72     6.8   23.72
     7.3   23.52     7.7   23.52     8.4   22.92    18.4   22.92
#Mann= 3 , 0 , 0
    -2.8    .035       0       0    .035       0     5.2    .035       0
#XS Ineff= 2 , 0
               0   23.74     5.2           23.72
Permanent Ineff=
       F       F
Bank Sta=0,5.2
XS Rating Curve= 0
Exp/Cntr=.3,.1

Type RM Length L Ch R = 1 ,750.00  ,44,44,44
BEGIN DESCRIPTION:
15
END DESCRIPTION:
#Sta/Elev= 14
    -2.7   24.81     -.7   23.61       0   23.19     1.3   22.41     1.7   21.71
     2.9   21.11       4   21.11     4.5   21.81     5.3   23.21     5.9   23.21
     6.4   23.01     6.8   23.01     7.5   22.41    17.5   22.41
#Mann= 3 , 0 , 0
    -2.7    .035       0       0    .035       0     5.3    .035       0
#XS Ineff= 2 , 0
               0   23.19     5.3           23.21
Permanent Ineff=
       F       F
Bank Sta=0,5.3
XS Rating Curve= 0
Exp/Cntr=.3,.1

Type RM Length L Ch R = 1 ,706.00  ,6,6,6
BEGIN DESCRIPTION:
14.006
END DESCRIPTION:
#Sta/Elev= 11
      -9   26.46      -6   24.86      -3   23.26       0   21.76     1.4   19.66
     5.8   19.66       6   21.66     6.5   21.76     8.8   21.76    10.2   19.86
    20.2   19.86
#Mann= 3 , 0 , 0
      -9    .035       0       0    .035       0     6.5    .035       0
#XS Ineff= 2 , 0
               0   21.76     6.5           21.76
Permanent Ineff=
       F       F
Bank Sta=0,6.5
XS Rating Curve= 0
Exp/Cntr=.3,.1

Type RM Length L Ch R = 1 ,700.00  ,50,50,50
BEGIN DESCRIPTION:
14
END DESCRIPTION:
#Sta/Elev= 13
    -7.8   24.31    -4.8   22.81    -1.8   21.31       0   20.51      .7   19.61
     1.4   19.31     2.8   19.31     3.8   19.71     4.3   19.71     4.6   21.51
     6.6   21.51     8.7   19.61    18.7   19.61
#Mann= 3 , 0 , 0
    -7.8    .035       0       0    .035       0     4.6    .035       0
#XS Ineff= 2 , 0
               0   20.51     4.6           21.51
Permanent Ineff=
       F       F
Bank Sta=0,4.6
XS Rating Curve= 0
Exp/Cntr=.3,.1

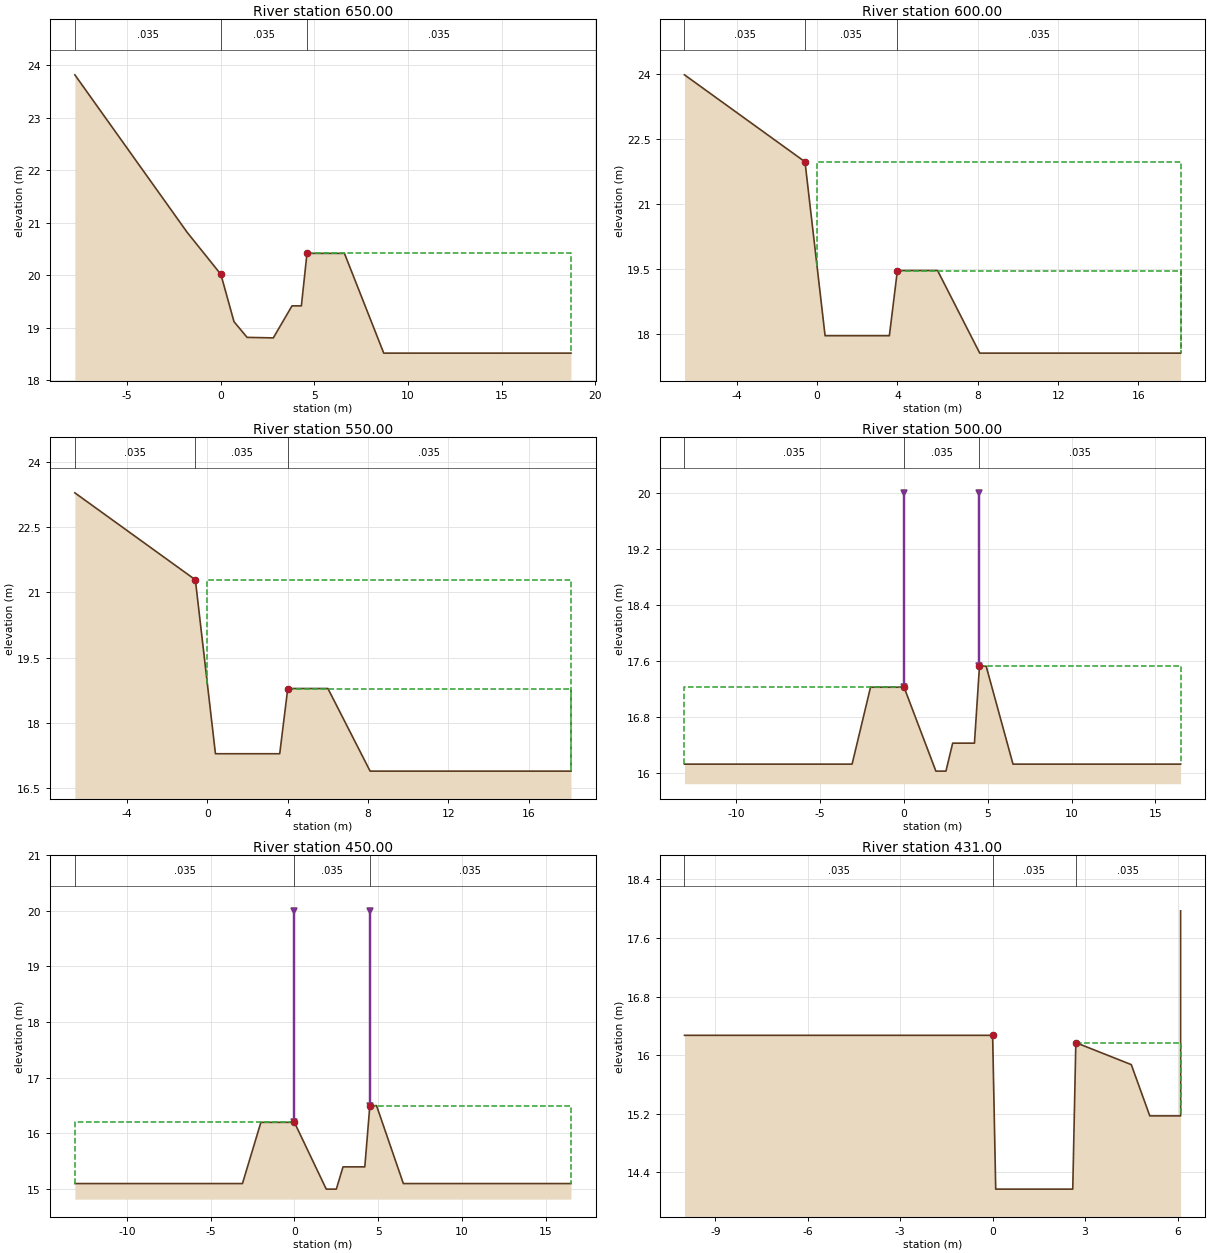
Type RM Length L Ch R = 1 ,650.00  ,50,50,50
BEGIN DESCRIPTION:
13
END DESCRIPTION:
#Sta/Elev= 13
    -7.8   23.82    -4.8   22.32    -1.8   20.82       0   20.02      .7   19.12
     1.4   18.82     2.8   18.81     3.8   19.42     4.3   19.42     4.6   20.42
     6.6   20.42     8.7   18.52    18.7   18.52
#Mann= 3 , 0 , 0
    -7.8    .035       0       0    .035       0     4.6    .035       0
#XS Ineff= 2 , 0
               0   20.02     4.6           20.42
Permanent Ineff=
       F       F
Bank Sta=0,4.6
XS Rating Curve= 0
Exp/Cntr=.3,.1

Type RM Length L Ch R = 1 ,600.00  ,50,50,50
BEGIN DESCRIPTION:
12
END DESCRIPTION:
#Sta/Elev= 10
    -6.6   23.97    -3.6   22.97     -.6   21.97       0   19.57      .4   17.97
     3.6   17.97       4   19.47       6   19.47     8.1   17.57    18.1   17.57
#Mann= 3 , 0 , 0
    -6.6    .035       0     -.6    .035       0       4    .035       0
#XS Ineff= 2 , 0
       0     -.6   21.97       4       0   19.47
Permanent Ineff=
       F       F
Bank Sta=-.6,4
XS Rating Curve= 0
Exp/Cntr=.3,.1

Type RM Length L Ch R = 1 ,550.00  ,50,50,50
BEGIN DESCRIPTION:
11
END DESCRIPTION:
#Sta/Elev= 10
    -6.6   23.29    -3.6   22.29     -.6   21.29       0   18.89      .4   17.29
     3.6   17.29       4   18.79       6   18.79     8.1   16.89    18.1   16.89
#Mann= 3 , 0 , 0
    -6.6    .035       0     -.6    .035       0       4    .035       0
#XS Ineff= 2 , 0
       0     -.6   21.29       4       0   18.79
Permanent Ineff=
       F       F
Bank Sta=-.6,4
XS Rating Curve= 0
Exp/Cntr=.3,.1

Type RM Length L Ch R = 1 ,500.00  ,50,50,50
BEGIN DESCRIPTION:
10
END DESCRIPTION:
#Sta/Elev= 12
   -13.1   16.12    -3.1   16.12      -2   17.22       0   17.22     1.9   16.02
     2.5   16.02     2.9   16.42     4.2   16.42     4.5   17.52     4.9   17.52
     6.5   16.12    16.5   16.12
#Mann= 3 , 0 , 0
   -13.1    .035       0       0    .035       0     4.5    .035       0
Levee=-1,0,20,-1,4.5,20,,
#XS Ineff= 2 , 0
               0   17.22     4.5           17.52
Permanent Ineff=
       F       F
Bank Sta=0,4.5
XS Rating Curve= 0
Exp/Cntr=.3,.1

Type RM Length L Ch R = 1 ,450.00  ,19,19,19
BEGIN DESCRIPTION:
9
END DESCRIPTION:
#Sta/Elev= 12
   -13.1    15.1    -3.1    15.1      -2    16.2       0    16.2     1.9      15
     2.5      15     2.9    15.4     4.2    15.4     4.5    16.5     4.9    16.5
     6.5    15.1    16.5    15.1
#Mann= 3 , 0 , 0
   -13.1    .035       0       0    .035       0     4.5    .035       0
Levee=-1,0,20,-1,4.5,20,,
#XS Ineff= 2 , 0
               0    16.2     4.5            16.5
Permanent Ineff=
       F       F
Bank Sta=0,4.5
XS Rating Curve= 0
Exp/Cntr=.3,.1

Type RM Length L Ch R = 1 ,431.00  ,31,31,31
BEGIN DESCRIPTION:
8.031
END DESCRIPTION:
#Sta/Elev= 9
     -10   16.27       0   16.27      .1   14.17     2.6   14.17     2.7   16.17
     4.5   15.87     5.1   15.17     6.1   15.17     6.1   17.97
#Mann= 3 , 0 , 0
     -10    .035       0       0    .035       0     2.7    .035       0
#XS Ineff= 2 , 0
               0   16.27     2.7           16.17
Permanent Ineff=
       F       F
Bank Sta=0,2.7
XS Rating Curve= 0
Exp/Cntr=.3,.1

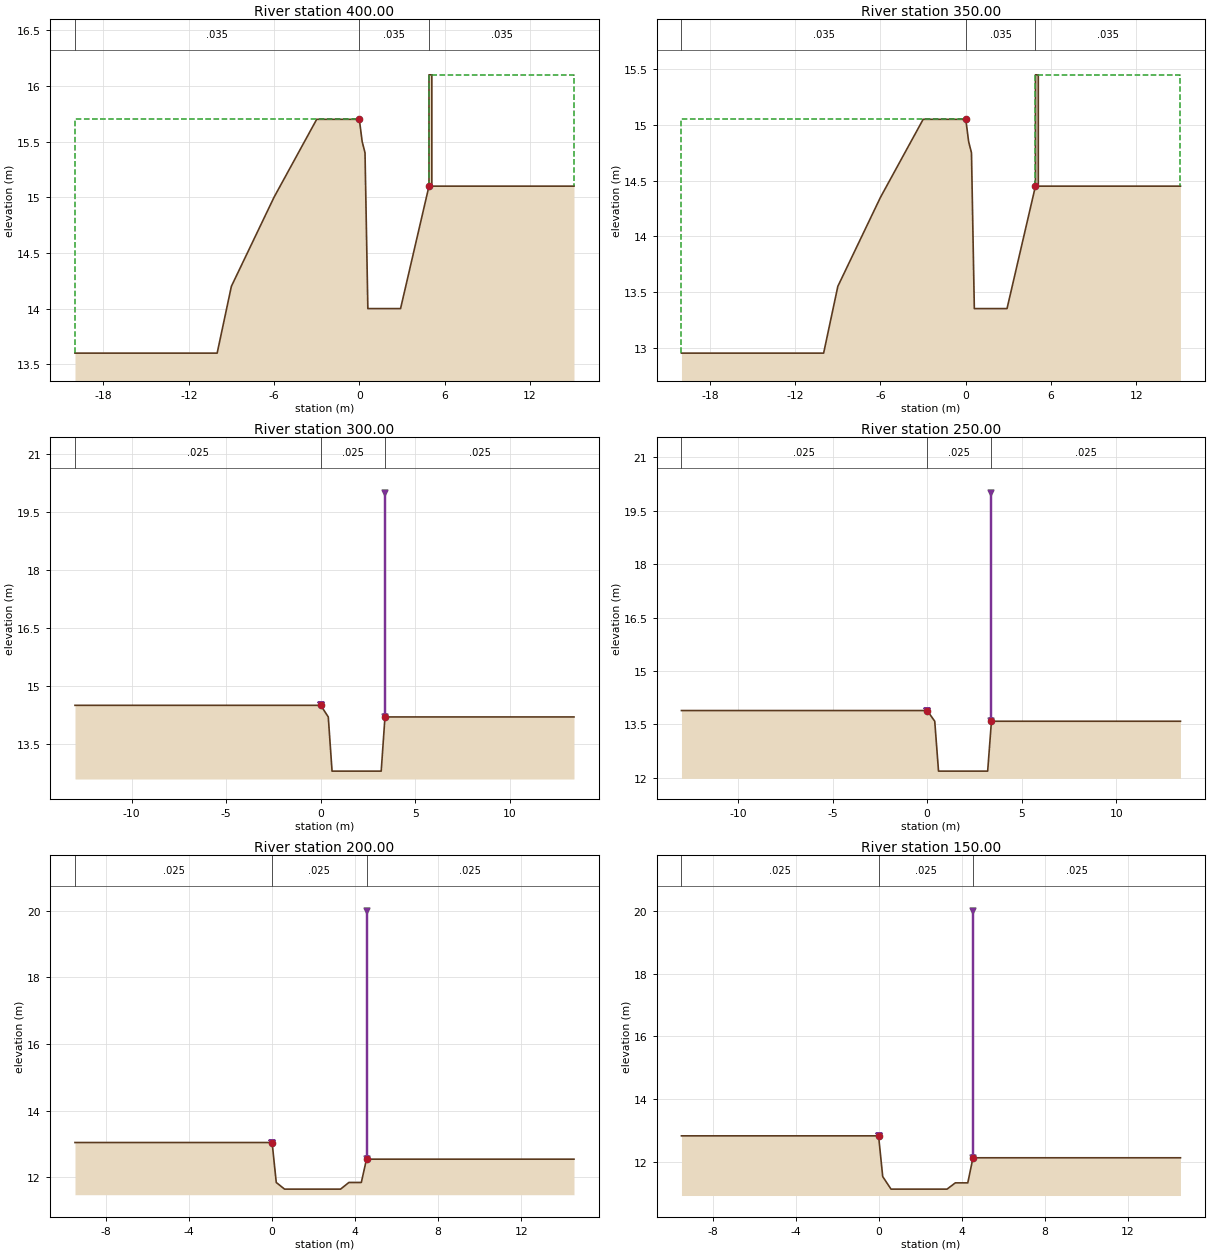
Type RM Length L Ch R = 1 ,400.00  ,50,50,50
BEGIN DESCRIPTION:
8
END DESCRIPTION:
#Sta/Elev= 15
     -20    13.6     -10    13.6      -9    14.2      -6      15      -3    15.7
       0    15.7      .2    15.5      .4    15.4      .6      14     2.9      14
     4.9    15.1     4.9    16.1     5.1    16.1     5.1    15.1    15.1    15.1
#Mann= 3 , 0 , 0
     -20    .035       0       0    .035       0     4.9    .035       0
#XS Ineff= 2 , 0
               0    15.7     4.9            16.1
Permanent Ineff=
       F       F
Bank Sta=0,4.9
XS Rating Curve= 0
Exp/Cntr=.3,.1

Type RM Length L Ch R = 1 ,350.00  ,50,50,50
BEGIN DESCRIPTION:
7
END DESCRIPTION:
#Sta/Elev= 15
     -20   12.95     -10   12.95      -9   13.55      -6   14.35      -3   15.05
       0   15.05      .2   14.85      .4   14.75      .6   13.35     2.9   13.35
     4.9   14.45     4.9   15.45     5.1   15.45     5.1   14.45    15.1   14.45
#Mann= 3 , 0 , 0
     -20    .035       0       0    .035       0     4.9    .035       0
#XS Ineff= 2 , 0
               0   15.05     4.9           15.45
Permanent Ineff=
       F       F
Bank Sta=0,4.9
XS Rating Curve= 0
Exp/Cntr=.3,.1

Type RM Length L Ch R = 1 ,300.00  ,50,50,50
BEGIN DESCRIPTION:
6
END DESCRIPTION:
#Sta/Elev= 8
     -13   14.51      -3   14.51       0   14.51      .4   14.21      .6   12.81
     3.2   12.81     3.4   14.21    13.4   14.21
#Mann= 3 , 0 , 0
     -13    .025       0       0    .025       0     3.4    .025       0
Levee=-1,0,14.51,-1,3.4,20,,
#XS Ineff= 2 , 0
               0   14.51     3.4           14.21
Permanent Ineff=
       F       F
Bank Sta=0,3.4
XS Rating Curve= 0
Exp/Cntr=.3,.1

Type RM Length L Ch R = 1 ,250.00  ,50,50,50
BEGIN DESCRIPTION:
5
END DESCRIPTION:
#Sta/Elev= 8
     -13   13.89      -3   13.89       0   13.89      .4   13.59      .6   12.19
     3.2   12.19     3.4   13.59    13.4   13.59
#Mann= 3 , 0 , 0
     -13    .025       0       0    .025       0     3.4    .025       0
Levee=-1,0,13.89,-1,3.4,20,,
#XS Ineff= 2 , 0
               0   13.89     3.4           13.59
Permanent Ineff=
       F       F
Bank Sta=0,3.4
XS Rating Curve= 0
Exp/Cntr=.3,.1

Type RM Length L Ch R = 1 ,200.00  ,50,50,50
BEGIN DESCRIPTION:
4
END DESCRIPTION:
#Sta/Elev= 9
    -9.5   13.04       0   13.04      .2   11.84      .6   11.64     3.3   11.64
     3.7   11.84     4.3   11.84    4.55   12.54   14.55   12.54
#Mann= 3 , 0 , 0
    -9.5    .025       0       0    .025       0    4.55    .025       0
Levee=-1,0,13.04,-1,4.55,20,,
#XS Ineff= 2 , 0
               0   13.04    4.55           12.54
Permanent Ineff=
       F       F
Bank Sta=0,4.55
XS Rating Curve= 0
Exp/Cntr=.3,.1

Type RM Length L Ch R = 1 ,150.00  ,50,50,50
BEGIN DESCRIPTION:
3
END DESCRIPTION:
#Sta/Elev= 9
    -9.5   12.82       0   12.82      .2   11.52      .6   11.12     3.3   11.12
     3.7   11.32     4.3   11.32    4.55   12.12   14.55   12.12
#Mann= 3 , 0 , 0
    -9.5    .025       0       0    .025       0    4.55    .025       0
Levee=-1,0,12.82,-1,4.55,20,,
#XS Ineff= 2 , 0
               0   12.82    4.55           12.12
Permanent Ineff=
       F       F
Bank Sta=0,4.55
XS Rating Curve= 0
Exp/Cntr=.3,.1

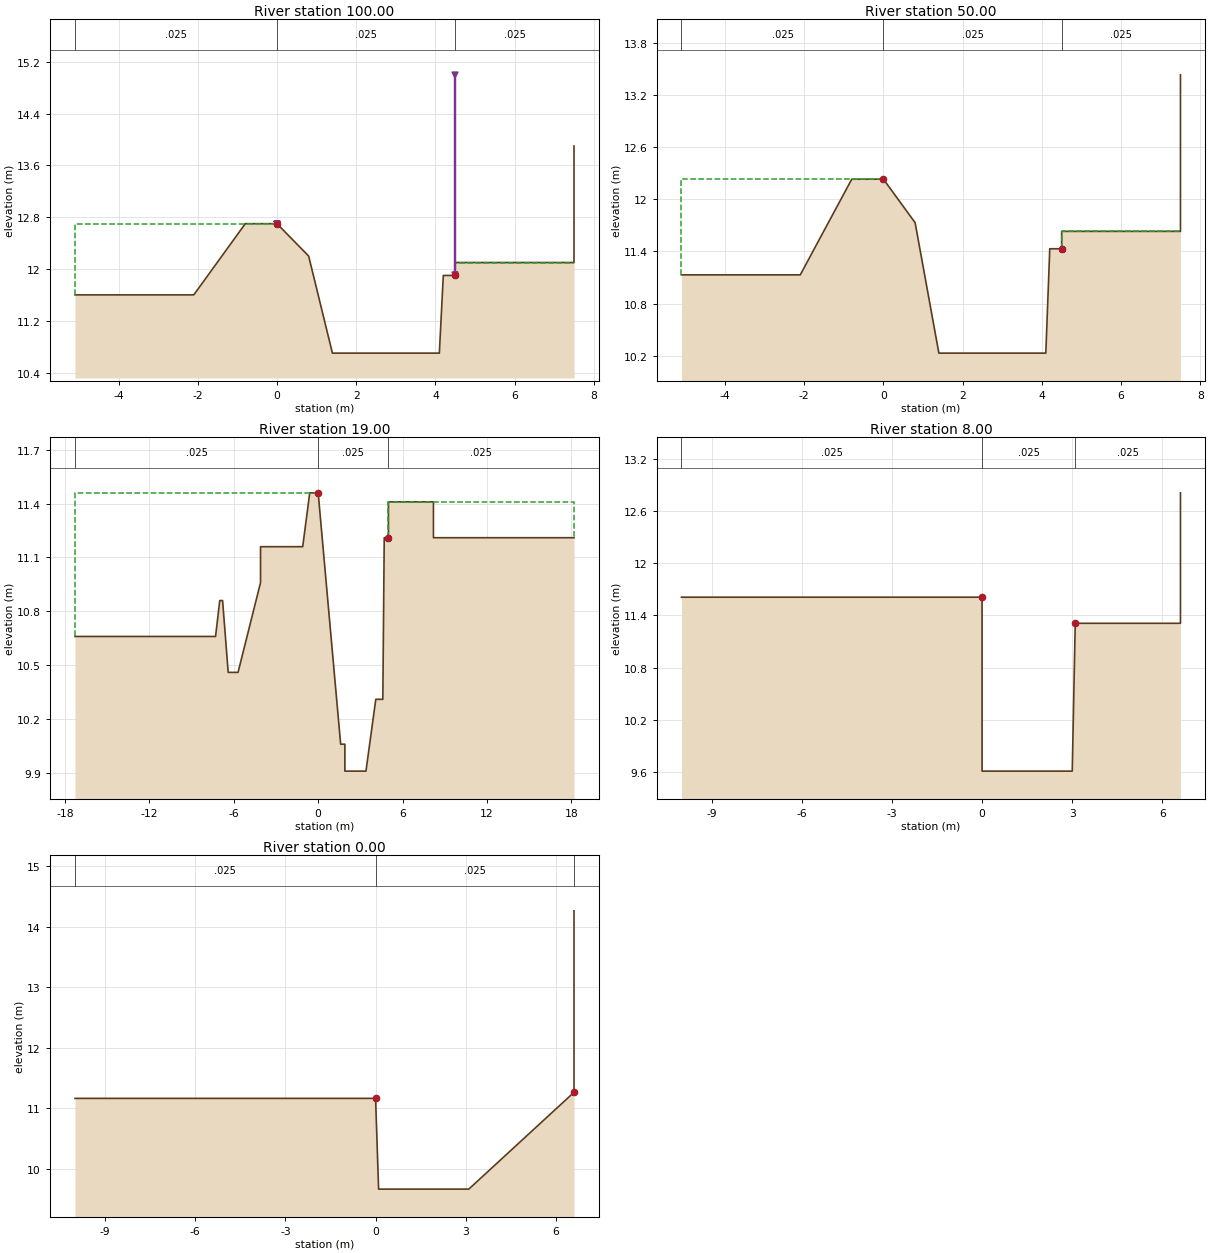
Type RM Length L Ch R = 1 ,100.00  ,50,50,50
BEGIN DESCRIPTION:
2
END DESCRIPTION:
#Sta/Elev= 12
    -5.1    11.6    -2.1    11.6     -.8    12.7       0    12.7      .8    12.2
     1.4    10.7     4.1    10.7     4.2    11.9     4.5    11.9     4.5    12.1
     7.5    12.1     7.5    13.9
#Mann= 3 , 0 , 0
    -5.1    .025       0       0    .025       0     4.5    .025       0
Levee=-1,0,12.7,-1,4.5,15,,
#XS Ineff= 2 , 0
               0    12.7     4.5            12.1
Permanent Ineff=
       F       F
Bank Sta=0,4.5
XS Rating Curve= 0
Exp/Cntr=.3,.1

Type RM Length L Ch R = 1 ,50.00   ,31,31,31
BEGIN DESCRIPTION:
1
END DESCRIPTION:
#Sta/Elev= 12
    -5.1   11.13    -2.1   11.13     -.8   12.23       0   12.23      .8   11.73
     1.4   10.23     4.1   10.23     4.2   11.43     4.5   11.43     4.5   11.63
     7.5   11.63     7.5   13.43
#Mann= 3 , 0 , 0
    -5.1    .025       0       0    .025       0     4.5    .025       0
#XS Ineff= 2 , 0
               0   12.23     4.5           11.63
Permanent Ineff=
       F       F
Bank Sta=0,4.5
XS Rating Curve= 0
Exp/Cntr=.3,.1

Type RM Length L Ch R = 1 ,19.00   ,11,11,11
BEGIN DESCRIPTION:
0.019
END DESCRIPTION:
#Sta/Elev= 23
   -17.3   10.66    -7.3   10.66      -7   10.86    -6.8   10.86    -6.4   10.46
    -5.7   10.46    -4.1   10.96    -4.1   11.16    -1.1   11.16     -.6   11.46
       0   11.46     1.6   10.06     1.9   10.06     1.9    9.91     3.4    9.91
     4.1   10.31     4.6   10.31     4.7   11.21       5   11.21       5   11.41
     8.2   11.41     8.2   11.21    18.2   11.21
#Mann= 3 , 0 , 0
   -17.3    .025       0       0    .025       0       5    .025       0
#XS Ineff= 2 , 0
               0   11.46       5           11.41
Permanent Ineff=
       F       F
Bank Sta=0,5
XS Rating Curve= 0
Exp/Cntr=.3,.1

Type RM Length L Ch R = 1 ,8.00    ,8,8,8
BEGIN DESCRIPTION:
0.008
END DESCRIPTION:
#Sta/Elev= 7
     -10   11.61       0   11.61       0    9.61       3    9.61     3.1   11.31
     6.6   11.31     6.6   12.81
#Mann= 3 , 0 , 0
     -10    .025       0       0    .025       0     3.1    .025       0
#XS Ineff= 2 , 0
               0   11.61     3.1           11.31
Permanent Ineff=
       F       F
Bank Sta=0,3.1
XS Rating Curve= 0
Exp/Cntr=.3,.1

Type RM Length L Ch R = 1 ,0.00    ,0,0,0
BEGIN DESCRIPTION:
0
END DESCRIPTION:
#Sta/Elev= 6
     -10   11.16       0   11.16      .1    9.66     3.1    9.66     6.6   11.26
     6.6   14.26
#Mann= 3 , 0 , 0
     -10    .025       0       0    .025       0     6.6    .025       0
#XS Ineff= 2 , 0
               0   11.16     6.6           14.26
Permanent Ineff=
       F       F
Bank Sta=0,6.6
XS Rating Curve= 0
Exp/Cntr=.3,.1

Chan Stop Cuts=-1