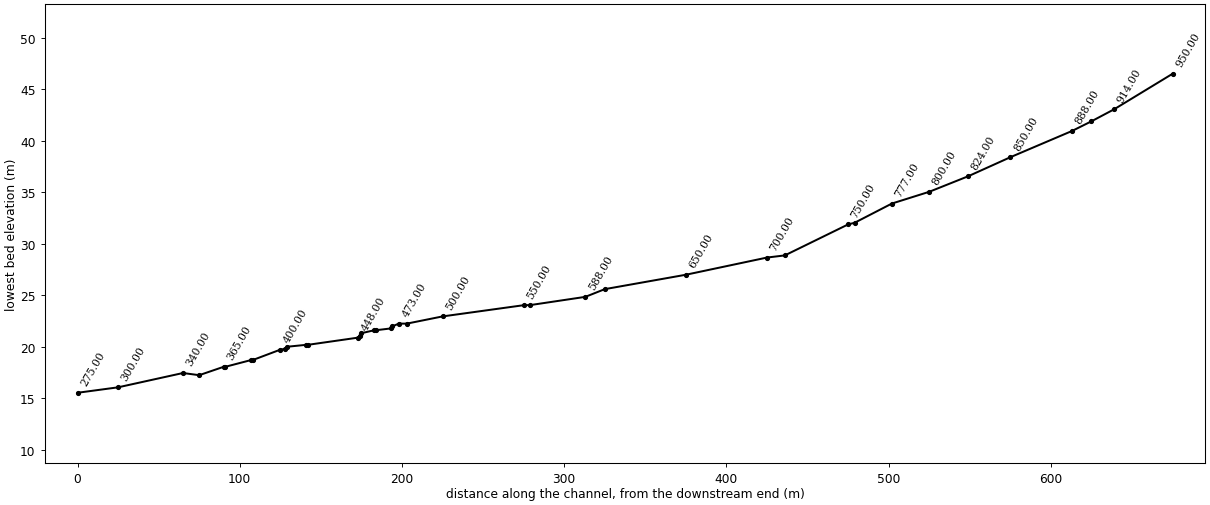
--- dcc.prj (project) ---

Proj Title=daechang-ch
Current Plan=p01
Default Exp/Contr=.3,.1
SI Units
Geom File=g01
Flow File=f01
Plan File=p01
Y Axis Title=Elevation
X Axis Title(PF)=Main Channel Distance
X Axis Title(XS)=Station
BEGIN DESCRIPTION:
           BACK WATER COMPUTATION
      APPLICATION OF HEC-2 BY Samju Construction Engineering
      ³»Ã¢Ãµ(¿ËÃµÀ¾): 30,50,80,100,150³âºóµµ °³¼öÀü
END DESCRIPTION:
DSS Export Rating Curves= 0
DSS Export Rating Curve Sorted= 0
DSS Export Volume Flow Curves= 0
DXF OffsetX= 0
DXF OffsetY= 0
DXF ScaleX= 1
DXF ScaleY= 10

--- dcc.p01 (plan) ---

Plan Title=Imported Plan 01
Version=Version 3.0.1  Mar 2001
Short Identifier=Imported Pla
Geom File=g01
Flow File=f01
Subcritical Flow
K Sum by GR= 0
Std Step Tol= 0.003
Critical Tol= 0.003
Num of Std Step Trials= 20
Max Error Tol= 0.1
Flow Tol Ratio= 0.001
Split Flow NTrial= 30
Split Flow Tol= 0.02
Split Flow Ratio= 0.02
Log Output Level= 0
Friction Slope Method= 1
Unsteady Friction Slope Method= 2
Parabolic Critical Depth
Global Vel Dist= 0 , 0 , 0
Global Log Level= 0
CheckData=True
Encroach Param=-1 ,0,0, 0
Computation Interval=1HOUR
Output Interval=1HOUR
Run HTab= 0
Run UNet= 0
Run PostProcess= 0
UNET Theta= 1
UNET ZTol= 0.02
UNET ZSATol= 0.1
UNET MxIter= 20
UNET MaxInSteps= 20
UNET DtIC= 0
UNET DtMin= 0
UNET MaxCRTS= 20
UNET WFStab= 2
UNET SFStab= 1
UNET WFX= 1
UNET SFX= 1
UNET Convert EG Bridges=-1
UNET Use Existing IB Tables=-1
Instantaneous Interval=1HOUR
Write IC File= 0
Write Velocity= 0
Write Detailed= 0

--- dcc.f01 (steady flow) ---

Flow Title=Imported Flow 01
Version=Version 3.0.1  Mar 2001
Number of Profiles= 5
Profile Names=10yr,20yr,30yr,50yr,80yr
River Rch & RM=RIVER-1,Reach-1         ,19
    6.61    7.28    7.67    8.17    8.62
River Rch & RM=daechang,daechang        ,950.00
    6.61    7.28    7.67    8.17    8.62
Boundary for River Rch & Prof#=daechang,daechang        , 1
Up Type= 0
Dn Type= 3
Dn Slope=.037
Boundary for River Rch & Prof#=daechang,daechang        , 2
Up Type= 0
Dn Type= 3
Dn Slope=.037
Boundary for River Rch & Prof#=daechang,daechang        , 3
Up Type= 0
Dn Type= 3
Dn Slope=.037
Boundary for River Rch & Prof#=daechang,daechang        , 4
Up Type= 0
Dn Type= 3
Dn Slope=.037
Boundary for River Rch & Prof#=daechang,daechang        , 5
Up Type= 0
Dn Type= 3
Dn Slope=.037
DSS Import GetInterval= 0
DSS Import GetPeak= 0
DSS Import FillOption= 0

--- dcc.g01 (geometry) ---

Geom Title=Imported Geom 01
Version=Version 3.0.1  Mar 2001

River Reach=daechang        ,daechang
Reach XY= 2
              .5             .95              .5             .05

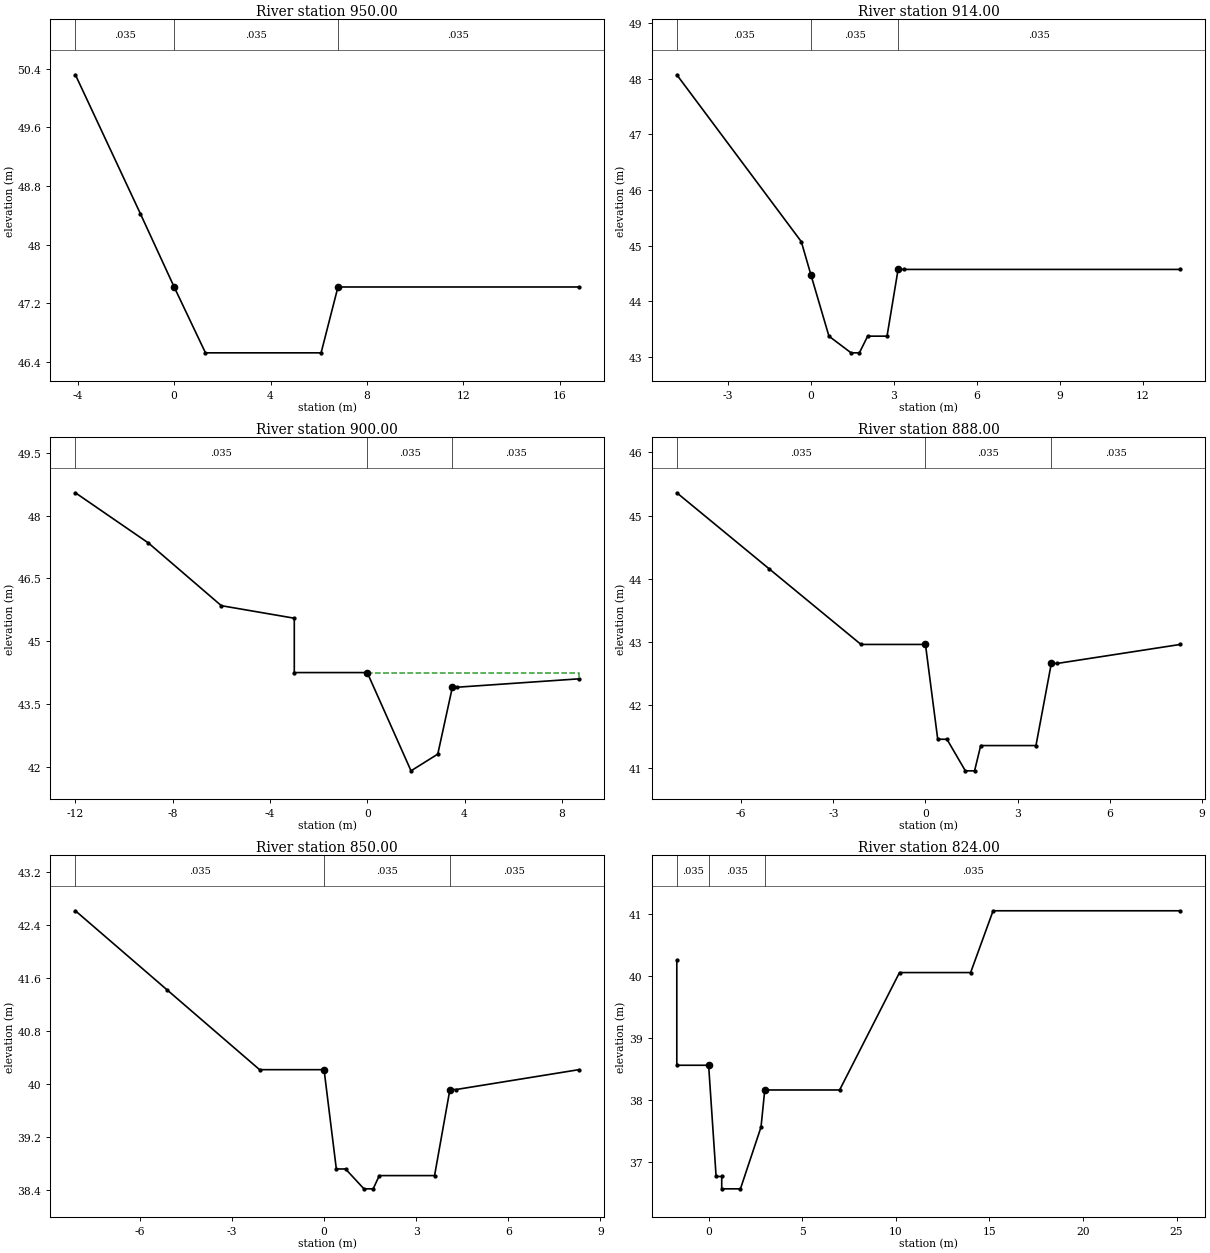
Type RM Length L Ch R = 1 ,950.00  ,36,36,36
BEGIN DESCRIPTION:
19
END DESCRIPTION:
#Sta/Elev= 7
    -4.1   50.32    -1.4   48.42       0   47.42     1.3   46.52     6.1   46.52
     6.8   47.42    16.8   47.42
#Mann= 3 , 0 , 0
    -4.1    .035       0       0    .035       0     6.8    .035       0
#XS Ineff= 2 , 0
               0   47.42     6.8           47.42
Permanent Ineff=
       F       F
Bank Sta=0,6.8
XS Rating Curve= 0
Exp/Cntr=.3,.1

Type RM Length L Ch R = 1 ,914.00  ,14,14,14
BEGIN DESCRIPTION:
18.014
END DESCRIPTION:
#Sta/Elev= 11
   -4.85   48.07    -.35   45.07       0   44.47     .65   43.37    1.45   43.07
    1.75   43.07    2.05   43.37    2.75   43.37    3.15   44.57    3.35   44.57
   13.35   44.57
#Mann= 3 , 0 , 0
   -4.85    .035       0       0    .035       0    3.15    .035       0
#XS Ineff= 2 , 0
               0   44.47    3.15           44.57
Permanent Ineff=
       F       F
Bank Sta=0,3.15
XS Rating Curve= 0
Exp/Cntr=.3,.1

Type RM Length L Ch R = 1 ,900.00  ,12,12,12
BEGIN DESCRIPTION:
18
END DESCRIPTION:
#Sta/Elev= 11
     -12   48.55      -9   47.35      -6   45.85      -3   45.55      -3   44.25
       0   44.25     1.8    41.9     2.9    42.3     3.5    43.9     3.7    43.9
     8.7    44.1
#Mann= 3 , 0 , 0
     -12    .035       0       0    .035       0     3.5    .035       0
#XS Ineff= 2 , 0
       0       0   44.25     3.5       0    43.9
Permanent Ineff=
       F       F
Bank Sta=0,3.5
XS Rating Curve= 0
Exp/Cntr=.3,.1

Type RM Length L Ch R = 1 ,888.00  ,38,38,38
BEGIN DESCRIPTION:
17.038
END DESCRIPTION:
#Sta/Elev= 13
    -8.1   45.36    -5.1   44.16    -2.1   42.96       0   42.96      .4   41.46
      .7   41.46     1.3   40.96     1.6   40.96     1.8   41.36     3.6   41.36
     4.1   42.66     4.3   42.66     8.3   42.96
#Mann= 3 , 0 , 0
    -8.1    .035       0       0    .035       0     4.1    .035       0
#XS Ineff= 2 , 0
               0   42.96     4.1           42.66
Permanent Ineff=
       F       F
Bank Sta=0,4.1
XS Rating Curve= 0
Exp/Cntr=.3,.1

Type RM Length L Ch R = 1 ,850.00  ,26,26,26
BEGIN DESCRIPTION:
17
END DESCRIPTION:
#Sta/Elev= 13
    -8.1   42.61    -5.1   41.41    -2.1   40.21       0   40.21      .4   38.71
      .7   38.71     1.3   38.41     1.6   38.41     1.8   38.61     3.6   38.61
     4.1   39.91     4.3   39.91     8.3   40.21
#Mann= 3 , 0 , 0
    -8.1    .035       0       0    .035       0     4.1    .035       0
#XS Ineff= 2 , 0
       0       0   40.21     4.1       0   39.91
Permanent Ineff=
       F       F
Bank Sta=0,4.1
XS Rating Curve= 0
Exp/Cntr=.3,.1

Type RM Length L Ch R = 1 ,824.00  ,24,24,24
BEGIN DESCRIPTION:
16.024
END DESCRIPTION:
#Sta/Elev= 14
    -1.7   40.26    -1.7   38.56       0   38.56      .4   36.76      .7   36.76
      .7   36.56     1.7   36.56     2.8   37.56       3   38.16       7   38.16
    10.2   40.06      14   40.06    15.2   41.06    25.2   41.06
#Mann= 3 , 0 , 0
    -1.7    .035       0       0    .035       0       3    .035       0
#XS Ineff= 2 , 0
               0   38.56       3           38.16
Permanent Ineff=
       F       F
Bank Sta=0,3
XS Rating Curve= 0
Exp/Cntr=.3,.1

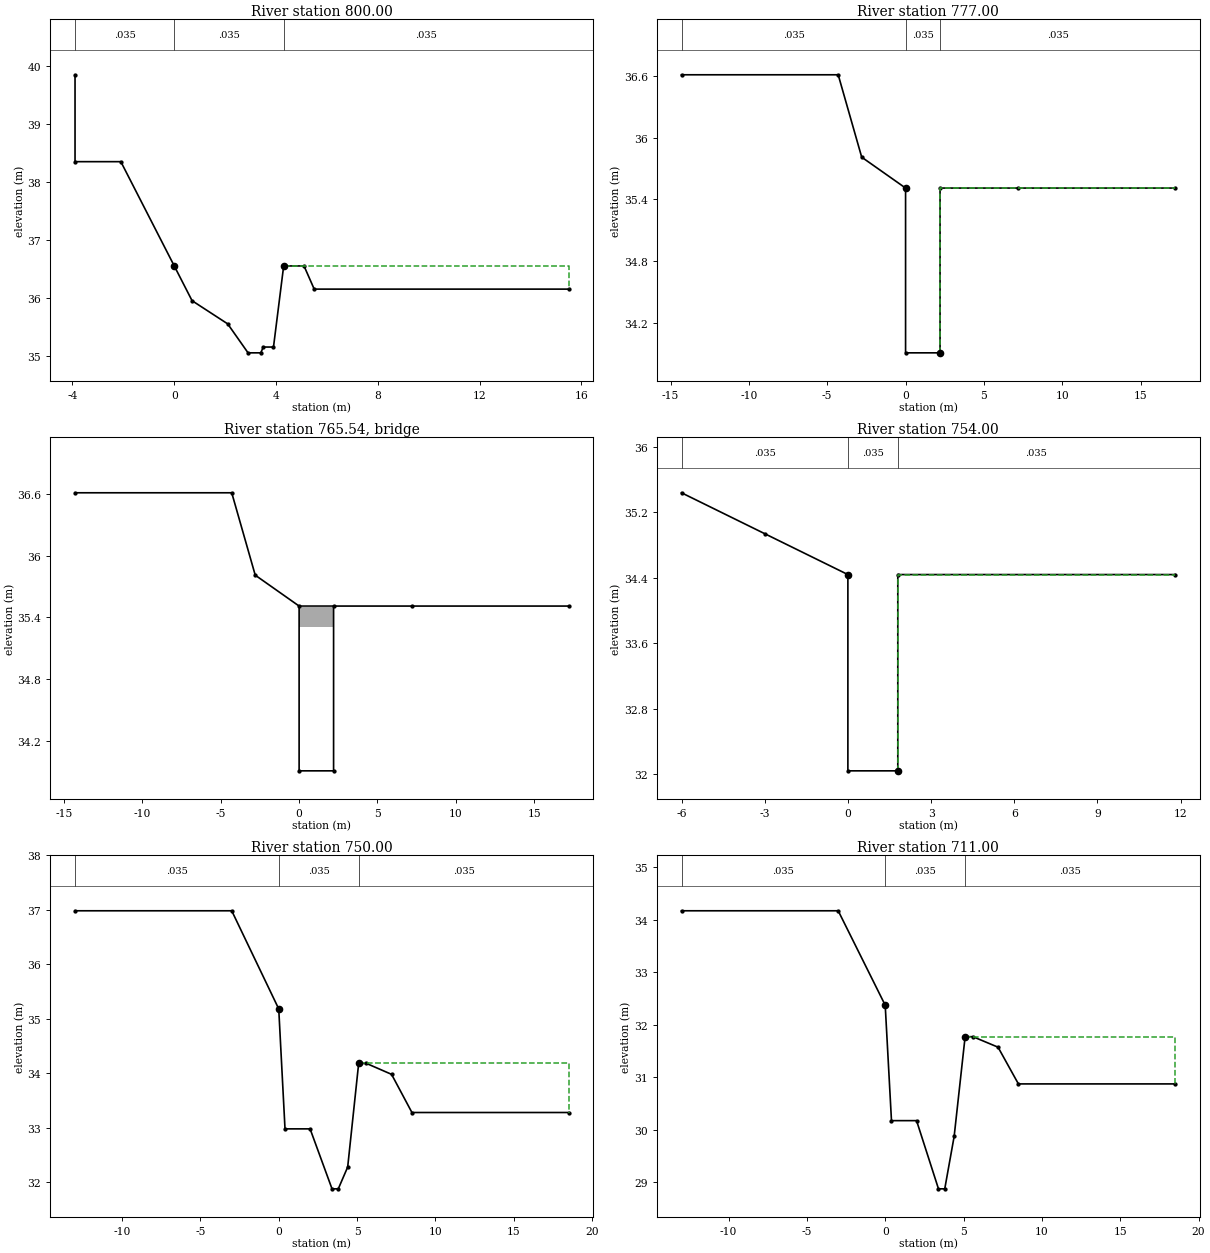
Type RM Length L Ch R = 1 ,800.00  ,23,23,23
BEGIN DESCRIPTION:
16
END DESCRIPTION:
#Sta/Elev= 14
    -3.9   39.85    -3.9   38.35    -2.1   38.35       0   36.55      .7   35.95
     2.1   35.55     2.9   35.05     3.4   35.05     3.5   35.15     3.9   35.15
     4.3   36.55     5.1   36.55     5.5   36.15    15.5   36.15
#Mann= 3 , 0 , 0
    -3.9    .035       0       0    .035       0     4.3    .035       0
#XS Ineff= 2 , 0
               0   36.55     4.3           36.55
Permanent Ineff=
       F       F
Bank Sta=0,4.3
XS Rating Curve= 0
Exp/Cntr=.3,.1

Type RM Length L Ch R = 1 ,777.00  ,23,23,23
BEGIN DESCRIPTION:
15.027
END DESCRIPTION:
#Sta/Elev= 9
   -14.3   36.61    -4.3   36.61    -2.8   35.81       0   35.51       0   33.91
     2.2   33.91     2.2   35.51     7.2   35.51    17.2   35.51
#Mann= 3 , 0 , 0
   -14.3    .035       0       0    .035       0     2.2    .035       0
#XS Ineff= 2 , 0
               0   35.51     2.2           35.51
Permanent Ineff=
       F       F
Bank Sta=0,2.2
XS Rating Curve= 0
Exp/Cntr=.3,.1

Type RM Length L Ch R = 3 ,765.54  ,,,
BEGIN DESCRIPTION:
15.0115
END DESCRIPTION:
Bridge Culvert--1,0,-1,-1, 0
Deck Dist Width WeirC Skew NumUp NumDn MinLoCord MaxHiCord MaxSubmerge Is_Ogee
.01,22.9,1.44,0, 2, 2, , , .95, 0, 0,0,,
       0     2.2
   35.51   35.51
   35.31   35.31
       0     1.8
   34.44   34.44
   34.24   34.24
BR Coef=-1 , 1 , 0 ,, 0 ,,,.8,-1,1.2,0,
WSPro=,,,, 1 ,,,, 0 ,,,, 0 ,,,,-1 ,-1 ,-1 , 0 , 0 , 0 , 0 , 0
BC Design=,, 0 ,, 0 ,,,,,,

Type RM Length L Ch R = 1 ,754.00  ,4,4,4
BEGIN DESCRIPTION:
15.004
END DESCRIPTION:
#Sta/Elev= 7
      -6   35.44      -3   34.94       0   34.44       0   32.04     1.8   32.04
     1.8   34.44    11.8   34.44
#Mann= 3 , 0 , 0
      -6    .035       0       0    .035       0     1.8    .035       0
#XS Ineff= 2 , 0
               0   34.44     1.8           34.44
Permanent Ineff=
       F       F
Bank Sta=0,1.8
XS Rating Curve= 0
Exp/Cntr=.3,.1

Type RM Length L Ch R = 1 ,750.00  ,39,39,39
BEGIN DESCRIPTION:
15
END DESCRIPTION:
#Sta/Elev= 13
     -13   36.98      -3   36.98       0   35.18      .4   32.98       2   32.98
     3.4   31.88     3.8   31.88     4.4   32.28     5.1   34.18     5.6   34.18
     7.2   33.98     8.5   33.28    18.5   33.28
#Mann= 3 , 0 , 0
     -13    .035       0       0    .035       0     5.1    .035       0
#XS Ineff= 2 , 0
               0   35.18     5.1           34.18
Permanent Ineff=
       F       F
Bank Sta=0,5.1
XS Rating Curve= 0
Exp/Cntr=.3,.1

Type RM Length L Ch R = 1 ,711.00  ,11,11,11
BEGIN DESCRIPTION:
14.011
END DESCRIPTION:
#Sta/Elev= 13
     -13   34.17      -3   34.17       0   32.37      .4   30.17       2   30.17
     3.4   28.87     3.8   28.87     4.4   29.87     5.1   31.77     5.6   31.77
     7.2   31.57     8.5   30.87    18.5   30.87
#Mann= 3 , 0 , 0
     -13    .035       0       0    .035       0     5.1    .035       0
#XS Ineff= 2 , 0
               0   32.37     5.1           31.77
Permanent Ineff=
       F       F
Bank Sta=0,5.1
XS Rating Curve= 0
Exp/Cntr=.3,.1

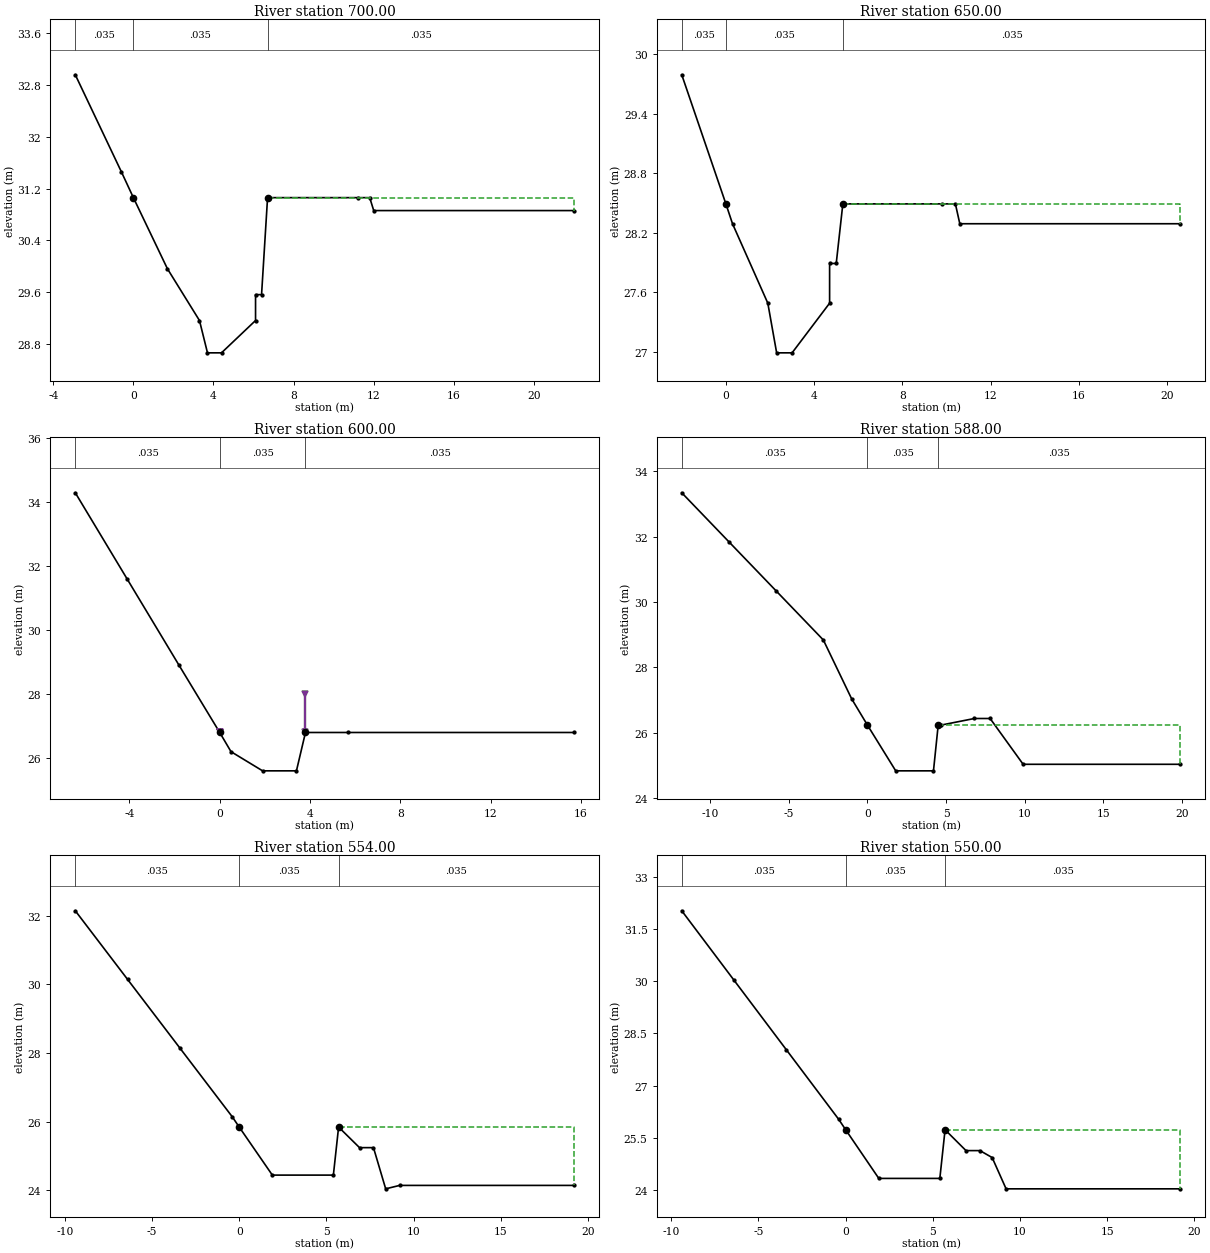
Type RM Length L Ch R = 1 ,700.00  ,50,50,50
BEGIN DESCRIPTION:
14
END DESCRIPTION:
#Sta/Elev= 15
    -2.9   32.96     -.6   31.46       0   31.06     1.7   29.96     3.3   29.16
     3.7   28.66     4.4   28.66     6.1   29.16     6.1   29.56     6.4   29.56
     6.7   31.06    11.2   31.06    11.8   31.06      12   30.86      22   30.86
#Mann= 3 , 0 , 0
    -2.9    .035       0       0    .035       0     6.7    .035       0
#XS Ineff= 2 , 0
               0   31.06     6.7           31.06
Permanent Ineff=
       F       F
Bank Sta=0,6.7
XS Rating Curve= 0
Exp/Cntr=.3,.1

Type RM Length L Ch R = 1 ,650.00  ,50,50,50
BEGIN DESCRIPTION:
13
END DESCRIPTION:
#Sta/Elev= 14
      -2   29.79       0   28.49      .3   28.29     1.9   27.49     2.3   26.99
       3   26.99     4.7   27.49     4.7   27.89       5   27.89     5.3   28.49
     9.8   28.49    10.4   28.49    10.6   28.29    20.6   28.29
#Mann= 3 , 0 , 0
      -2    .035       0       0    .035       0     5.3    .035       0
#XS Ineff= 2 , 0
               0   28.49     5.3           28.49
Permanent Ineff=
       F       F
Bank Sta=0,5.3
XS Rating Curve= 0
Exp/Cntr=.3,.1

Type RM Length L Ch R = 1 ,600.00  ,12,12,12
BEGIN DESCRIPTION:
12
END DESCRIPTION:
#Sta/Elev= 10
    -6.4   34.29    -4.1   31.59    -1.8   28.89       0   26.79      .5   26.19
     1.9   25.59     3.4   25.59     3.8   26.79     5.7   26.79    15.7   26.79
#Mann= 3 , 0 , 0
    -6.4    .035       0       0    .035       0     3.8    .035       0
Levee=-1,0,26.79,-1,3.8,28,,
#XS Ineff= 2 , 0
               0   26.79     3.8           26.79
Permanent Ineff=
       F       F
Bank Sta=0,3.8
XS Rating Curve= 0
Exp/Cntr=.3,.1

Type RM Length L Ch R = 1 ,588.00  ,34,34,34
BEGIN DESCRIPTION:
11.038
END DESCRIPTION:
#Sta/Elev= 14
   -11.8   33.34    -8.8   31.84    -5.8   30.34    -2.8   28.84      -1   27.04
       0   26.24     1.8   24.84     4.2   24.84     4.5   26.24     4.7   26.24
     6.8   26.44     7.8   26.44     9.9   25.04    19.9   25.04
#Mann= 3 , 0 , 0
   -11.8    .035       0       0    .035       0     4.5    .035       0
#XS Ineff= 2 , 0
               0   26.24     4.5           26.24
Permanent Ineff=
       F       F
Bank Sta=0,4.5
XS Rating Curve= 0
Exp/Cntr=.3,.1

Type RM Length L Ch R = 1 ,554.00  ,4,4,4
BEGIN DESCRIPTION:
11.004
END DESCRIPTION:
#Sta/Elev= 13
    -9.4   32.14    -6.4   30.14    -3.4   28.14     -.4   26.14       0   25.84
     1.9   24.44     5.4   24.44     5.7   25.84     6.9   25.24     7.7   25.24
     8.4   24.04     9.2   24.14    19.2   24.14
#Mann= 3 , 0 , 0
    -9.4    .035       0       0    .035       0     5.7    .035       0
#XS Ineff= 2 , 0
               0   25.84     5.7           25.84
Permanent Ineff=
       F       F
Bank Sta=0,5.7
XS Rating Curve= 0
Exp/Cntr=.3,.1

Type RM Length L Ch R = 1 ,550.00  ,50,50,50
BEGIN DESCRIPTION:
11
END DESCRIPTION:
#Sta/Elev= 13
    -9.4   32.03    -6.4   30.03    -3.4   28.03     -.4   26.03       0   25.73
     1.9   24.33     5.4   24.33     5.7   25.73     6.9   25.13     7.7   25.13
     8.4   24.93     9.2   24.03    19.2   24.03
#Mann= 3 , 0 , 0
    -9.4    .035       0       0    .035       0     5.7    .035       0
#XS Ineff= 2 , 0
               0   25.73     5.7           25.73
Permanent Ineff=
       F       F
Bank Sta=0,5.7
XS Rating Curve= 0
Exp/Cntr=.3,.1

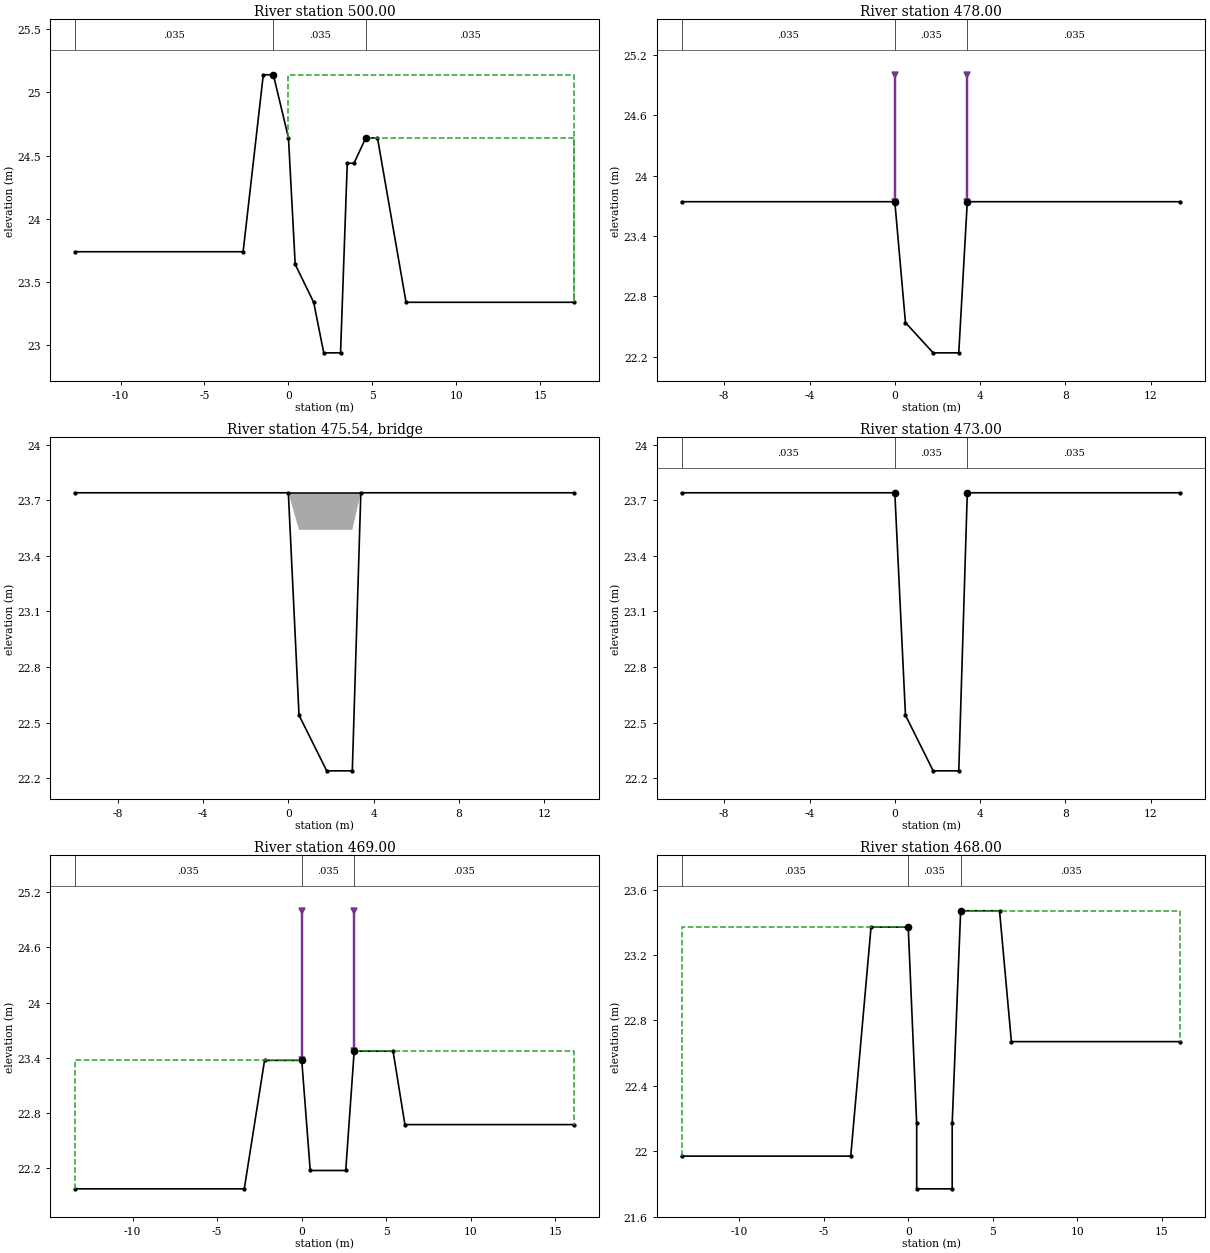
Type RM Length L Ch R = 1 ,500.00  ,22,22,22
BEGIN DESCRIPTION:
10
END DESCRIPTION:
#Sta/Elev= 15
   -12.7   23.74    -2.7   23.74    -1.5   25.14     -.9   25.14       0   24.64
      .4   23.64     1.5   23.34     2.1   22.94     3.1   22.94     3.5   24.44
     3.9   24.44     4.6   24.64     5.3   24.64       7   23.34      17   23.34
#Mann= 3 , 0 , 0
   -12.7    .035       0     -.9    .035       0     4.6    .035       0
#XS Ineff= 2 , 0
       0     -.9   25.14     4.6       0   24.64
Permanent Ineff=
       F       F
Bank Sta=-.9,4.6
XS Rating Curve= 0
Exp/Cntr=.3,.1

Type RM Length L Ch R = 1 ,478.00  ,5,5,5
BEGIN DESCRIPTION:
9.028
END DESCRIPTION:
#Sta/Elev= 7
     -10   23.74       0   23.74      .5   22.54     1.8   22.24       3   22.24
     3.4   23.74    13.4   23.74
#Mann= 3 , 0 , 0
     -10    .035       0       0    .035       0     3.4    .035       0
Levee=-1,0,25,-1,3.4,25,,
#XS Ineff= 2 , 0
               0   23.74     3.4           23.74
Permanent Ineff=
       F       F
Bank Sta=0,3.4
XS Rating Curve= 0
Exp/Cntr=.3,.1

Type RM Length L Ch R = 3 ,475.54  ,,,
BEGIN DESCRIPTION:
9.0255
END DESCRIPTION:
Bridge Culvert--1,0,-1,-1, 0
Deck Dist Width WeirC Skew NumUp NumDn MinLoCord MaxHiCord MaxSubmerge Is_Ogee
.01,4.9,1.44,0, 2, 2, , , .95, 0, 0,0,,
       0     3.4
   23.74   23.74
   23.54   23.54
       0     3.4
   23.74   23.74
   23.54   23.54
BR Coef=-1 , 1 , 0 ,, 0 ,,,.8,-1,1.2,0,
WSPro=,,,, 1 ,,,, 0 ,,,, 0 ,,,,-1 ,-1 ,-1 , 0 , 0 , 0 , 0 , 0
BC Design=,, 0 ,, 0 ,,,,,,

Type RM Length L Ch R = 1 ,473.00  ,4,4,4
BEGIN DESCRIPTION:
9.023
END DESCRIPTION:
#Sta/Elev= 7
     -10   23.74       0   23.74      .5   22.54     1.8   22.24       3   22.24
     3.4   23.74    13.4   23.74
#Mann= 3 , 0 , 0
     -10    .035       0       0    .035       0     3.4    .035       0
#XS Ineff= 2 , 0
               0   23.74     3.4           23.74
Permanent Ineff=
       F       F
Bank Sta=0,3.4
XS Rating Curve= 0
Exp/Cntr=.3,.1

Type RM Length L Ch R = 1 ,469.00  ,1,1,1
BEGIN DESCRIPTION:
9.019
END DESCRIPTION:
#Sta/Elev= 10
   -13.4   21.97    -3.4   21.97    -2.2   23.37       0   23.37      .5   22.17
     2.6   22.17     3.1   23.47     5.4   23.47     6.1   22.67    16.1   22.67
#Mann= 3 , 0 , 0
   -13.4    .035       0       0    .035       0     3.1    .035       0
Levee=-1,0,25,-1,3.1,25,,
#XS Ineff= 2 , 0
               0   23.37     3.1           23.47
Permanent Ineff=
       F       F
Bank Sta=0,3.1
XS Rating Curve= 0
Exp/Cntr=.3,.1

Type RM Length L Ch R = 1 ,468.00  ,9,9,9
BEGIN DESCRIPTION:
9.018
END DESCRIPTION:
#Sta/Elev= 12
   -13.4   21.97    -3.4   21.97    -2.2   23.37       0   23.37      .5   22.17
      .5   21.77     2.6   21.77     2.6   22.17     3.1   23.47     5.4   23.47
     6.1   22.67    16.1   22.67
#Mann= 3 , 0 , 0
   -13.4    .035       0       0    .035       0     3.1    .035       0
#XS Ineff= 2 , 0
               0   23.37     3.1           23.47
Permanent Ineff=
       F       F
Bank Sta=0,3.1
XS Rating Curve= 0
Exp/Cntr=.3,.1

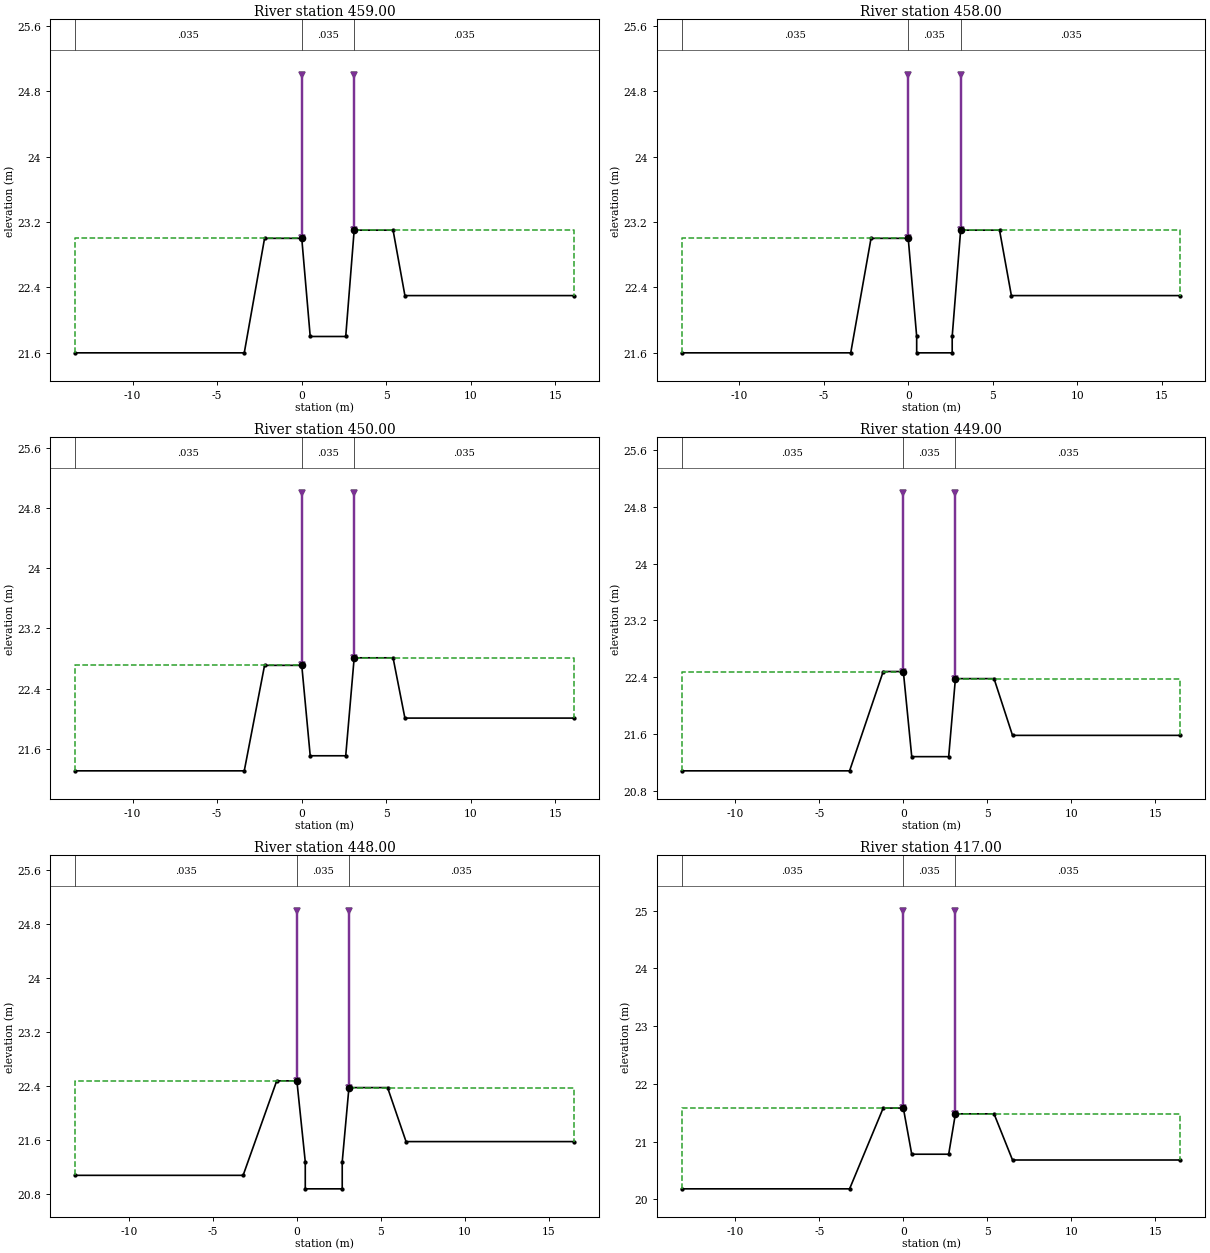
Type RM Length L Ch R = 1 ,459.00  ,1,1,1
BEGIN DESCRIPTION:
9.009
END DESCRIPTION:
#Sta/Elev= 10
   -13.4    21.6    -3.4    21.6    -2.2      23       0      23      .5    21.8
     2.6    21.8     3.1    23.1     5.4    23.1     6.1    22.3    16.1    22.3
#Mann= 3 , 0 , 0
   -13.4    .035       0       0    .035       0     3.1    .035       0
Levee=-1,0,25,-1,3.1,25,,
#XS Ineff= 2 , 0
               0      23     3.1            23.1
Permanent Ineff=
       F       F
Bank Sta=0,3.1
XS Rating Curve= 0
Exp/Cntr=.3,.1

Type RM Length L Ch R = 1 ,458.00  ,8,8,8
BEGIN DESCRIPTION:
9.008
END DESCRIPTION:
#Sta/Elev= 12
   -13.4    21.6    -3.4    21.6    -2.2      23       0      23      .5    21.8
      .5    21.6     2.6    21.6     2.6    21.8     3.1    23.1     5.4    23.1
     6.1    22.3    16.1    22.3
#Mann= 3 , 0 , 0
   -13.4    .035       0       0    .035       0     3.1    .035       0
Levee=-1,0,25,-1,3.1,25,,
#XS Ineff= 2 , 0
               0      23     3.1            23.1
Permanent Ineff=
       F       F
Bank Sta=0,3.1
XS Rating Curve= 0
Exp/Cntr=.3,.1

Type RM Length L Ch R = 1 ,450.00  ,1,1,1
BEGIN DESCRIPTION:
9
END DESCRIPTION:
#Sta/Elev= 10
   -13.4   21.31    -3.4   21.31    -2.2   22.71       0   22.71      .5   21.51
     2.6   21.51     3.1   22.81     5.4   22.81     6.1   22.01    16.1   22.01
#Mann= 3 , 0 , 0
   -13.4    .035       0       0    .035       0     3.1    .035       0
Levee=-1,0,25,-1,3.1,25,,
#XS Ineff= 2 , 0
               0   22.71     3.1           22.81
Permanent Ineff=
       F       F
Bank Sta=0,3.1
XS Rating Curve= 0
Exp/Cntr=.3,.1

Type RM Length L Ch R = 1 ,449.00  ,1,1,1
BEGIN DESCRIPTION:
8.049
END DESCRIPTION:
#Sta/Elev= 10
   -13.2   21.08    -3.2   21.08    -1.2   22.48       0   22.48      .5   21.28
     2.7   21.28     3.1   22.38     5.4   22.38     6.5   21.58    16.5   21.58
#Mann= 3 , 0 , 0
   -13.2    .035       0       0    .035       0     3.1    .035       0
Levee=-1,0,25,-1,3.1,25,,
#XS Ineff= 2 , 0
               0   22.48     3.1           22.38
Permanent Ineff=
       F       F
Bank Sta=0,3.1
XS Rating Curve= 0
Exp/Cntr=.3,.1

Type RM Length L Ch R = 1 ,448.00  ,31,31,31
BEGIN DESCRIPTION:
8.048
END DESCRIPTION:
#Sta/Elev= 12
   -13.2   21.08    -3.2   21.08    -1.2   22.48       0   22.48      .5   21.28
      .5   20.88     2.7   20.88     2.7   21.28     3.1   22.38     5.4   22.38
     6.5   21.58    16.5   21.58
#Mann= 3 , 0 , 0
   -13.2    .035       0       0    .035       0     3.1    .035       0
Levee=-1,0,25,-1,3.1,25,,
#XS Ineff= 2 , 0
               0   22.48     3.1           22.38
Permanent Ineff=
       F       F
Bank Sta=0,3.1
XS Rating Curve= 0
Exp/Cntr=.3,.1

Type RM Length L Ch R = 1 ,417.00  ,1,1,1
BEGIN DESCRIPTION:
8.017
END DESCRIPTION:
#Sta/Elev= 10
   -13.2   20.18    -3.2   20.18    -1.2   21.58       0   21.58      .5   20.78
     2.7   20.78     3.1   21.48     5.4   21.48     6.5   20.68    16.5   20.68
#Mann= 3 , 0 , 0
   -13.2    .035       0       0    .035       0     3.1    .035       0
Levee=-1,0,25,-1,3.1,25,,
#XS Ineff= 2 , 0
               0   21.58     3.1           21.48
Permanent Ineff=
       F       F
Bank Sta=0,3.1
XS Rating Curve= 0
Exp/Cntr=.3,.1

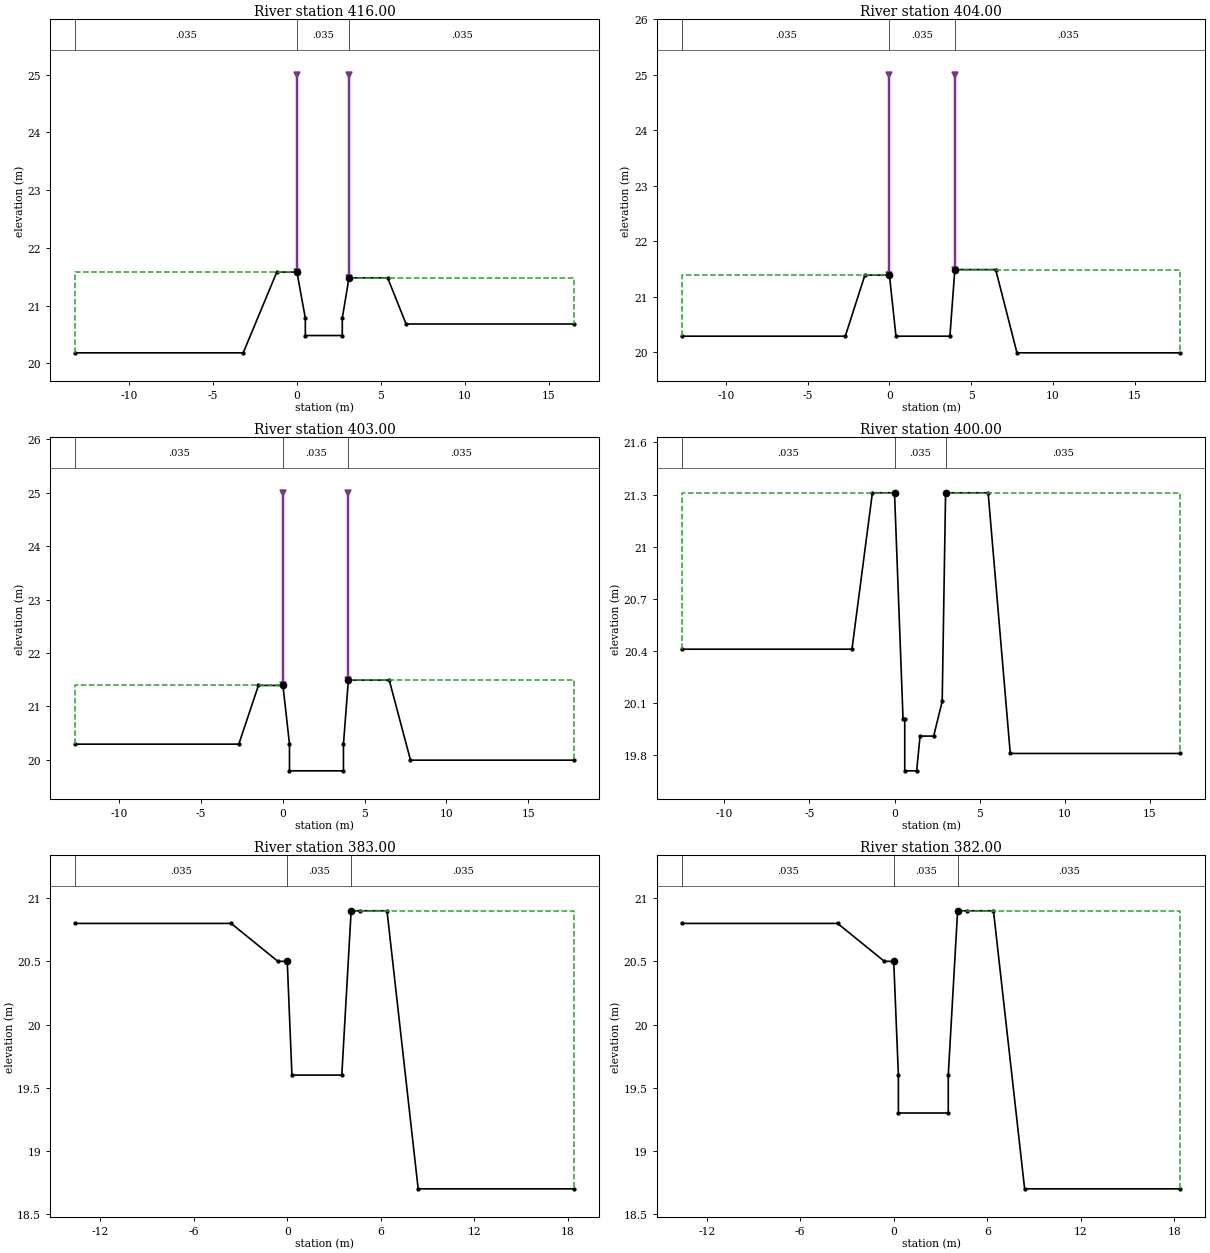
Type RM Length L Ch R = 1 ,416.00  ,12,12,12
BEGIN DESCRIPTION:
8.016
END DESCRIPTION:
#Sta/Elev= 12
   -13.2   20.18    -3.2   20.18    -1.2   21.58       0   21.58      .5   20.78
      .5   20.48     2.7   20.48     2.7   20.78     3.1   21.48     5.4   21.48
     6.5   20.68    16.5   20.68
#Mann= 3 , 0 , 0
   -13.2    .035       0       0    .035       0     3.1    .035       0
Levee=-1,0,25,-1,3.1,25,,
#XS Ineff= 2 , 0
               0   21.58     3.1           21.48
Permanent Ineff=
       F       F
Bank Sta=0,3.1
XS Rating Curve= 0
Exp/Cntr=.3,.1

Type RM Length L Ch R = 1 ,404.00  ,1,1,1
BEGIN DESCRIPTION:
8.004
END DESCRIPTION:
#Sta/Elev= 10
   -12.7   20.29    -2.7   20.29    -1.5   21.39       0   21.39      .4   20.29
     3.7   20.29       4   21.49     6.5   21.49     7.8   19.99    17.8   19.99
#Mann= 3 , 0 , 0
   -12.7    .035       0       0    .035       0       4    .035       0
Levee=-1,0,25,-1,4,25,,
#XS Ineff= 2 , 0
               0   21.39       4           21.49
Permanent Ineff=
       F       F
Bank Sta=0,4
XS Rating Curve= 0
Exp/Cntr=.3,.1

Type RM Length L Ch R = 1 ,403.00  ,3,3,3
BEGIN DESCRIPTION:
8.003
END DESCRIPTION:
#Sta/Elev= 12
   -12.7   20.29    -2.7   20.29    -1.5   21.39       0   21.39      .4   20.29
      .4   19.79     3.7   19.79     3.7   20.29       4   21.49     6.5   21.49
     7.8   19.99    17.8   19.99
#Mann= 3 , 0 , 0
   -12.7    .035       0       0    .035       0       4    .035       0
Levee=-1,0,25,-1,4,25,,
#XS Ineff= 2 , 0
               0   21.39       4           21.49
Permanent Ineff=
       F       F
Bank Sta=0,4
XS Rating Curve= 0
Exp/Cntr=.3,.1

Type RM Length L Ch R = 1 ,400.00  ,17,17,17
BEGIN DESCRIPTION:
8
END DESCRIPTION:
#Sta/Elev= 15
   -12.5   20.41    -2.5   20.41    -1.3   21.31       0   21.31      .5   20.01
      .6   20.01      .6   19.71     1.3   19.71     1.5   19.91     2.3   19.91
     2.8   20.11       3   21.31     5.5   21.31     6.8   19.81    16.8   19.81
#Mann= 3 , 0 , 0
   -12.5    .035       0       0    .035       0       3    .035       0
#XS Ineff= 2 , 0
               0   21.31       3           21.31
Permanent Ineff=
       F       F
Bank Sta=0,3
XS Rating Curve= 0
Exp/Cntr=.3,.1

Type RM Length L Ch R = 1 ,383.00  ,1,1,1
BEGIN DESCRIPTION:
7.033
END DESCRIPTION:
#Sta/Elev= 11
   -13.6    20.8    -3.6    20.8     -.6    20.5       0    20.5      .3    19.6
     3.5    19.6     4.1    20.9     4.7    20.9     6.4    20.9     8.4    18.7
    18.4    18.7
#Mann= 3 , 0 , 0
   -13.6    .035       0       0    .035       0     4.1    .035       0
#XS Ineff= 2 , 0
               0    20.5     4.1            20.9
Permanent Ineff=
       F       F
Bank Sta=0,4.1
XS Rating Curve= 0
Exp/Cntr=.3,.1

Type RM Length L Ch R = 1 ,382.00  ,16,16,16
BEGIN DESCRIPTION:
7.032
END DESCRIPTION:
#Sta/Elev= 13
   -13.6    20.8    -3.6    20.8     -.6    20.5       0    20.5      .3    19.6
      .3    19.3     3.5    19.3     3.5    19.6     4.1    20.9     4.7    20.9
     6.4    20.9     8.4    18.7    18.4    18.7
#Mann= 3 , 0 , 0
   -13.6    .035       0       0    .035       0     4.1    .035       0
#XS Ineff= 2 , 0
               0    20.5     4.1            20.9
Permanent Ineff=
       F       F
Bank Sta=0,4.1
XS Rating Curve= 0
Exp/Cntr=.3,.1

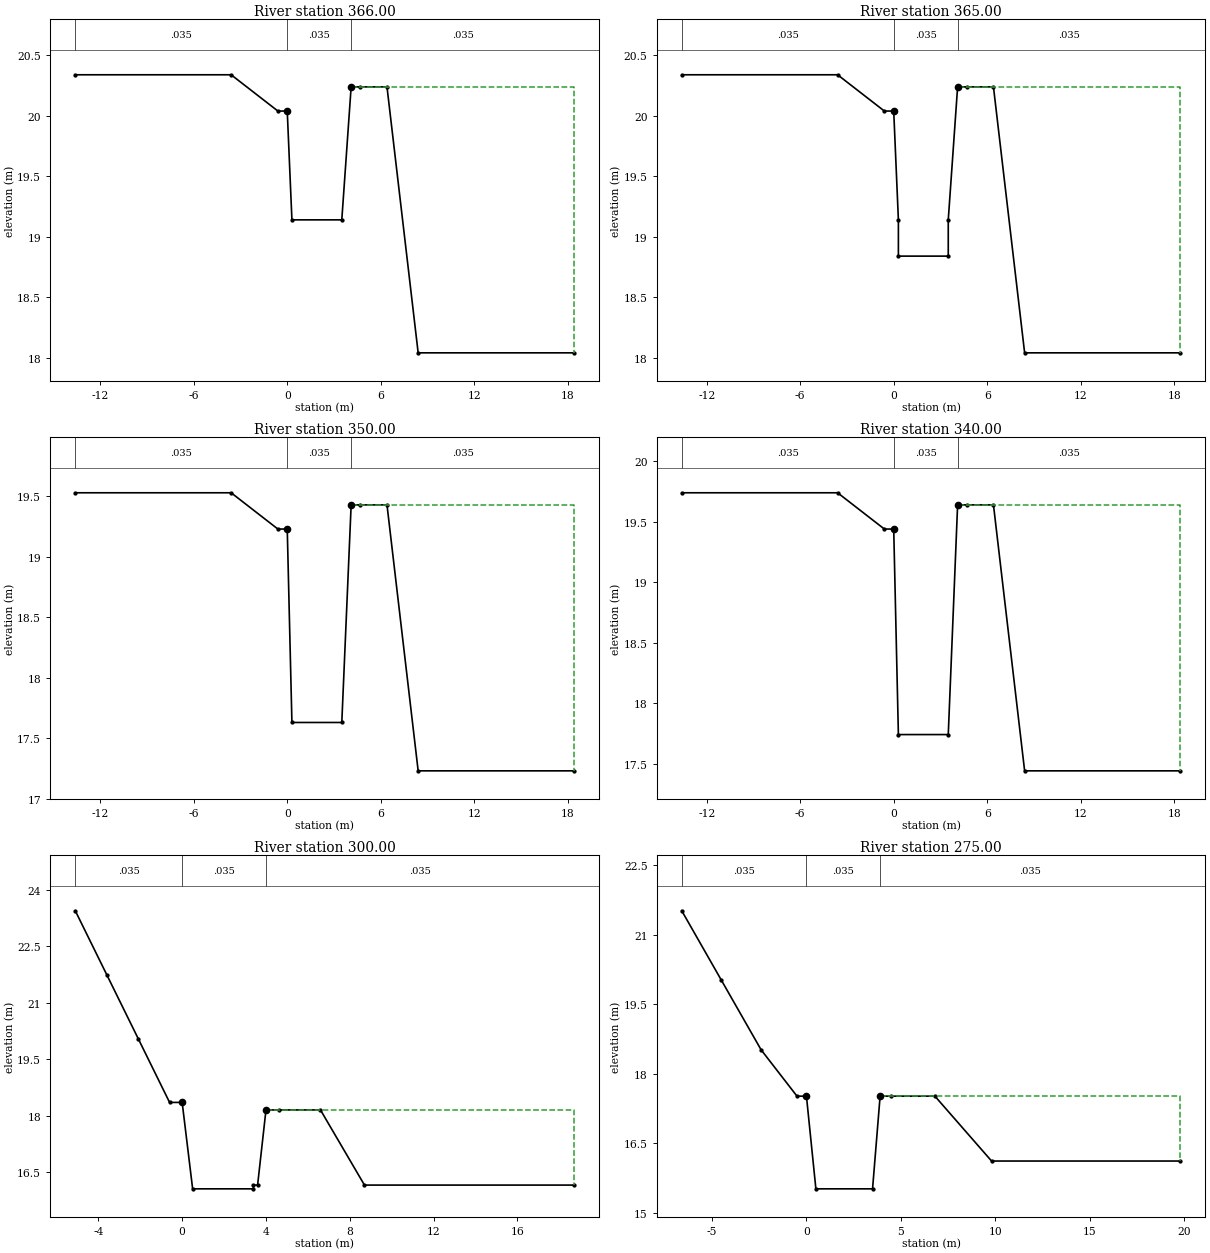
Type RM Length L Ch R = 1 ,366.00  ,1,1,1
BEGIN DESCRIPTION:
7.016
END DESCRIPTION:
#Sta/Elev= 11
   -13.6   20.34    -3.6   20.34     -.6   20.04       0   20.04      .3   19.14
     3.5   19.14     4.1   20.24     4.7   20.24     6.4   20.24     8.4   18.04
    18.4   18.04
#Mann= 3 , 0 , 0
   -13.6    .035       0       0    .035       0     4.1    .035       0
#XS Ineff= 2 , 0
               0   20.04     4.1           20.24
Permanent Ineff=
       F       F
Bank Sta=0,4.1
XS Rating Curve= 0
Exp/Cntr=.3,.1

Type RM Length L Ch R = 1 ,365.00  ,15,15,15
BEGIN DESCRIPTION:
7.015
END DESCRIPTION:
#Sta/Elev= 13
   -13.6   20.34    -3.6   20.34     -.6   20.04       0   20.04      .3   19.14
      .3   18.84     3.5   18.84     3.5   19.14     4.1   20.24     4.7   20.24
     6.4   20.24     8.4   18.04    18.4   18.04
#Mann= 3 , 0 , 0
   -13.6    .035       0       0    .035       0     4.1    .035       0
#XS Ineff= 2 , 0
               0   20.04     4.1           20.24
Permanent Ineff=
       F       F
Bank Sta=0,4.1
XS Rating Curve= 0
Exp/Cntr=.3,.1

Type RM Length L Ch R = 1 ,350.00  ,10,10,10
BEGIN DESCRIPTION:
7
END DESCRIPTION:
#Sta/Elev= 11
   -13.6   19.53    -3.6   19.53     -.6   19.23       0   19.23      .3   17.63
     3.5   17.63     4.1   19.43     4.7   19.43     6.4   19.43     8.4   17.23
    18.4   17.23
#Mann= 3 , 0 , 0
   -13.6    .035       0       0    .035       0     4.1    .035       0
#XS Ineff= 2 , 0
               0   19.23     4.1           19.43
Permanent Ineff=
       F       F
Bank Sta=0,4.1
XS Rating Curve= 0
Exp/Cntr=.3,.1

Type RM Length L Ch R = 1 ,340.00  ,40,40,40
BEGIN DESCRIPTION:
6.04
END DESCRIPTION:
#Sta/Elev= 11
   -13.6   19.74    -3.6   19.74     -.6   19.44       0   19.44      .3   17.74
     3.5   17.74     4.1   19.64     4.7   19.64     6.4   19.64     8.4   17.44
    18.4   17.44
#Mann= 3 , 0 , 0
   -13.6    .035       0       0    .035       0     4.1    .035       0
#XS Ineff= 2 , 0
               0   19.44     4.1           19.64
Permanent Ineff=
       F       F
Bank Sta=0,4.1
XS Rating Curve= 0
Exp/Cntr=.3,.1

Type RM Length L Ch R = 1 ,300.00  ,25,25,25
BEGIN DESCRIPTION:
6
END DESCRIPTION:
#Sta/Elev= 14
    -5.1   23.45    -3.6   21.75    -2.1   20.05     -.6   18.35       0   18.35
      .5   16.05     3.4   16.05     3.4   16.15     3.6   16.15       4   18.15
     4.6   18.15     6.6   18.15     8.7   16.15    18.7   16.15
#Mann= 3 , 0 , 0
    -5.1    .035       0       0    .035       0       4    .035       0
#XS Ineff= 2 , 0
               0   18.35       4           18.15
Permanent Ineff=
       F       F
Bank Sta=0,4
XS Rating Curve= 0
Exp/Cntr=.3,.1

Type RM Length L Ch R = 1 ,275.00  ,25,25,25
BEGIN DESCRIPTION:
5.025
END DESCRIPTION:
#Sta/Elev= 12
    -6.6   21.52    -4.5   20.02    -2.4   18.52     -.5   17.52       0   17.52
      .5   15.52     3.5   15.52     3.9   17.52     4.5   17.52     6.8   17.52
     9.8   16.12    19.8   16.12
#Mann= 3 , 0 , 0
    -6.6    .035       0       0    .035       0     3.9    .035       0
#XS Ineff= 2 , 0
               0   17.52     3.9           17.52
Permanent Ineff=
       F       F
Bank Sta=0,3.9
XS Rating Curve= 0
Exp/Cntr=.3,.1