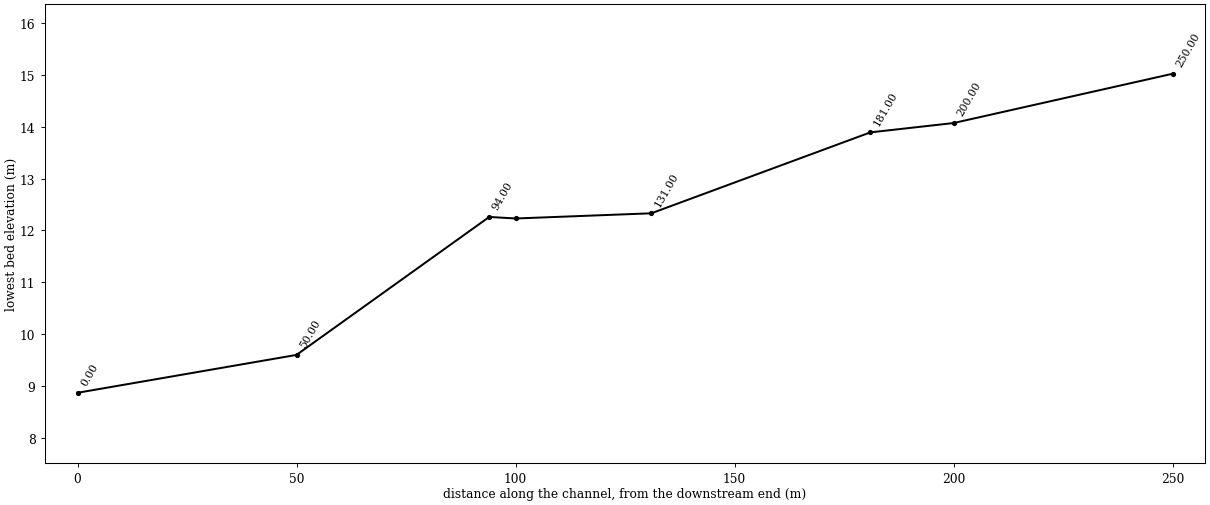
HEC-RAS study dcc.prj: daechang-ch

--- dcc.g01 (geometry) --- (continued)

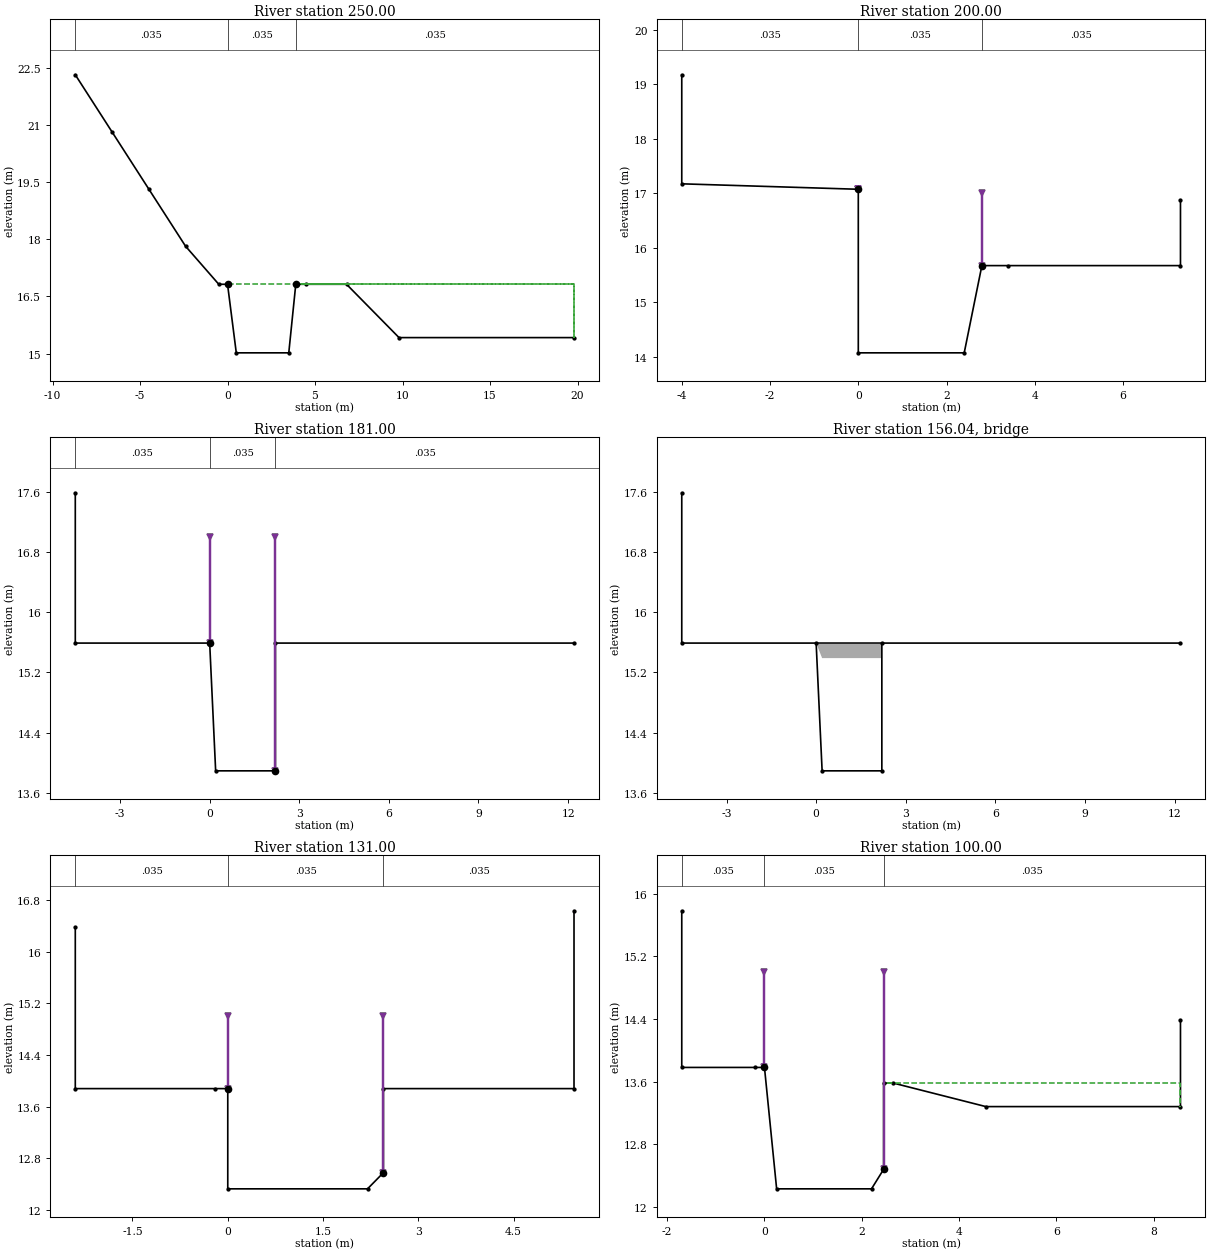
Type RM Length L Ch R = 1 ,250.00  ,50,50,50
BEGIN DESCRIPTION:
5
END DESCRIPTION:
#Sta/Elev= 13
    -8.7   22.32    -6.6   20.82    -4.5   19.32    -2.4   17.82     -.5   16.82
       0   16.82      .5   15.02     3.5   15.02     3.9   16.82     4.5   16.82
     6.8   16.82     9.8   15.42    19.8   15.42
#Mann= 3 , 0 , 0
    -8.7    .035       0       0    .035       0     3.9    .035       0
#XS Ineff= 2 , 0
       0       0   16.82     3.9       0   16.82
Permanent Ineff=
       F       F
Bank Sta=0,3.9
XS Rating Curve= 0
Exp/Cntr=.3,.1

Type RM Length L Ch R = 1 ,200.00  ,19,19,19
BEGIN DESCRIPTION:
4
END DESCRIPTION:
#Sta/Elev= 9
      -4   19.17      -4   17.17       0   17.07       0   14.07     2.4   14.07
     2.8   15.67     3.4   15.67     7.3   15.67     7.3   16.87
#Mann= 3 , 0 , 0
      -4    .035       0       0    .035       0     2.8    .035       0
Levee=-1,0,17.07,-1,2.8,17,,
#XS Ineff= 2 , 0
               0   17.07     2.8           15.67
Permanent Ineff=
       F       F
Bank Sta=0,2.8
XS Rating Curve= 0
Exp/Cntr=.3,.1

Type RM Length L Ch R = 1 ,181.00  ,50,50,50
BEGIN DESCRIPTION:
3.031
END DESCRIPTION:
#Sta/Elev= 7
    -4.5   17.59    -4.5   15.59       0   15.59      .2   13.89     2.2   13.89
     2.2   15.59    12.2   15.59
#Mann= 3 , 0 , 0
    -4.5    .035       0       0    .035       0     2.2    .035       0
Levee=-1,0,17,-1,2.2,17,,
#XS Ineff= 2 , 0
       0       0   15.59     2.2       0   13.89
Permanent Ineff=
       F       F
Bank Sta=0,2.2
XS Rating Curve= 0
Exp/Cntr=.3,.1

Type RM Length L Ch R = 3 ,156.04  ,,,
BEGIN DESCRIPTION:
3.006
END DESCRIPTION:
Bridge Culvert--1,0,-1,-1, 0
Deck Dist Width WeirC Skew NumUp NumDn MinLoCord MaxHiCord MaxSubmerge Is_Ogee
.01,49.9,1.44,0, 2, 2, , , .95, 0, 0,0,,
       0     2.2
   15.59   15.59
   15.39   15.39
       0    2.45
   13.88   13.88
   13.68   13.68
BR Coef=-1 , 1 , 0 ,, 0 ,,,.8,-1,1.2,0,
WSPro=,,,, 1 ,,,, 0 ,,,, 0 ,,,,-1 ,-1 ,-1 , 0 , 0 , 0 , 0 , 0
BC Design=,, 0 ,, 0 ,,,,,,

Type RM Length L Ch R = 1 ,131.00  ,31,31,31
BEGIN DESCRIPTION:
2.031
END DESCRIPTION:
#Sta/Elev= 10
    -2.4   16.38    -2.4   13.88     -.2   13.88       0   13.88       0   12.33
     2.2   12.33    2.45   12.58    2.45   13.88    5.45   13.88    5.45   16.63
#Mann= 3 , 0 , 0
    -2.4    .035       0       0    .035       0    2.45    .035       0
Levee=-1,0,15,-1,2.45,15,,
#XS Ineff= 2 , 0
       0       0   13.88    2.45       0   12.58
Permanent Ineff=
       F       F
Bank Sta=0,2.45
XS Rating Curve= 0
Exp/Cntr=.3,.1

Type RM Length L Ch R = 1 ,100.00  ,6,6,6
BEGIN DESCRIPTION:
2
END DESCRIPTION:
#Sta/Elev= 12
    -1.7   15.78    -1.7   13.78     -.2   13.78       0   13.78     .25   12.23
     2.2   12.23    2.45   12.48    2.45   13.58    2.65   13.58    4.55   13.28
    8.55   13.28    8.55   14.38
#Mann= 3 , 0 , 0
    -1.7    .035       0       0    .035       0    2.45    .035       0
Levee=-1,0,15,-1,2.45,15,,
#XS Ineff= 2 , 0
               0   13.78    2.45           13.58
Permanent Ineff=
       F       F
Bank Sta=0,2.45
XS Rating Curve= 0
Exp/Cntr=.3,.1

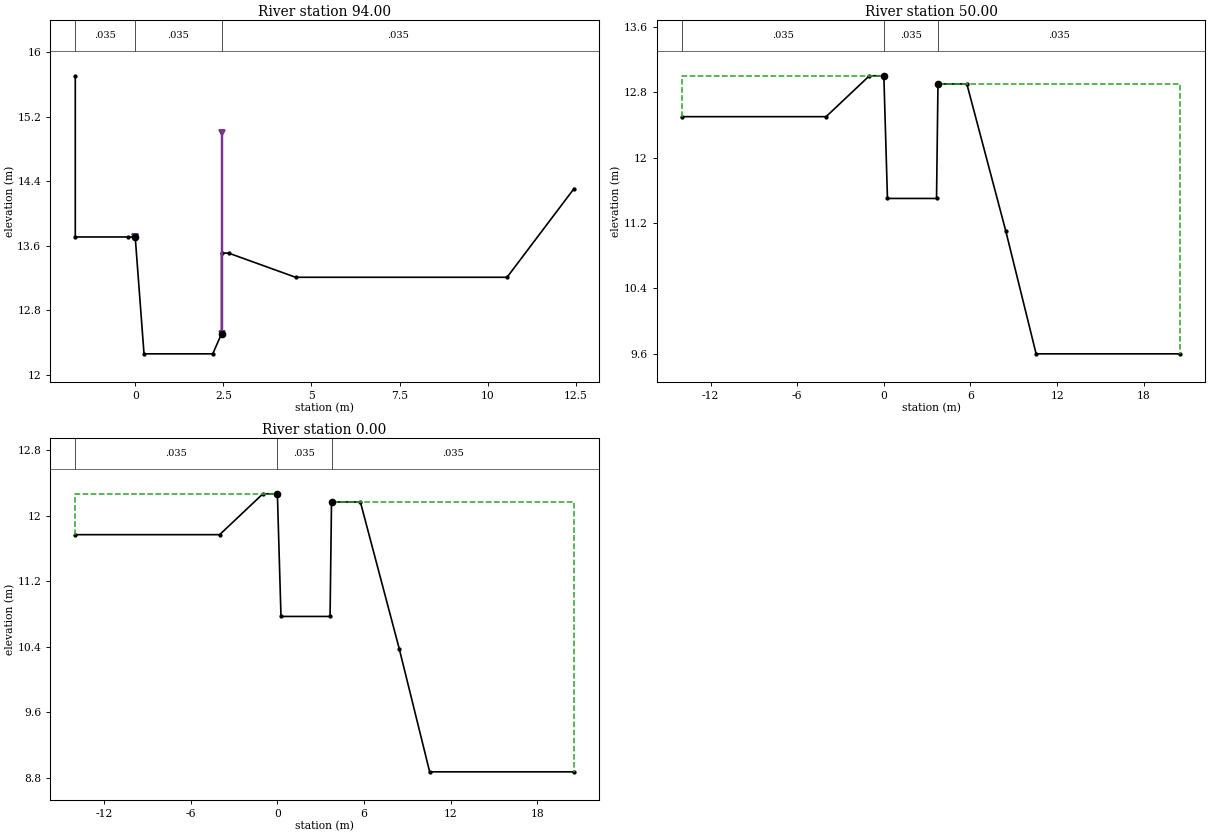
Type RM Length L Ch R = 1 ,94.00   ,44,44,44
BEGIN DESCRIPTION:
1.044
END DESCRIPTION:
#Sta/Elev= 12
    -1.7   15.71    -1.7   13.71     -.2   13.71       0   13.71     .25   12.26
     2.2   12.26    2.45   12.51    2.45   13.51    2.65   13.51    4.55   13.21
   10.55   13.21   12.45   14.31
#Mann= 3 , 0 , 0
    -1.7    .035       0       0    .035       0    2.45    .035       0
Levee=-1,0,13.71,-1,2.45,15,,
#XS Ineff= 2 , 0
       0       0   13.71    2.45       0   12.51
Permanent Ineff=
       F       F
Bank Sta=0,2.45
XS Rating Curve= 0
Exp/Cntr=.3,.1

Type RM Length L Ch R = 1 ,50.00   ,50,50,50
BEGIN DESCRIPTION:
1
END DESCRIPTION:
#Sta/Elev= 11
     -14    12.5      -4    12.5      -1      13       0      13     .25    11.5
    3.65    11.5    3.75    12.9    5.75    12.9    8.45    11.1   10.55     9.6
   20.55     9.6
#Mann= 3 , 0 , 0
     -14    .035       0       0    .035       0    3.75    .035       0
#XS Ineff= 2 , 0
               0      13    3.75            12.9
Permanent Ineff=
       F       F
Bank Sta=0,3.75
XS Rating Curve= 0
Exp/Cntr=.3,.1

Type RM Length L Ch R = 1 ,0.00    ,0,0,0
BEGIN DESCRIPTION:
0
END DESCRIPTION:
#Sta/Elev= 11
     -14   11.77      -4   11.77      -1   12.27       0   12.27     .25   10.77
    3.65   10.77    3.75   12.17    5.75   12.17    8.45   10.37   10.55    8.87
   20.55    8.87
#Mann= 3 , 0 , 0
     -14    .035       0       0    .035       0    3.75    .035       0
#XS Ineff= 2 , 0
               0   12.27    3.75           12.17
Permanent Ineff=
       F       F
Bank Sta=0,3.75
XS Rating Curve= 0
Exp/Cntr=.3,.1

Chan Stop Cuts=-1