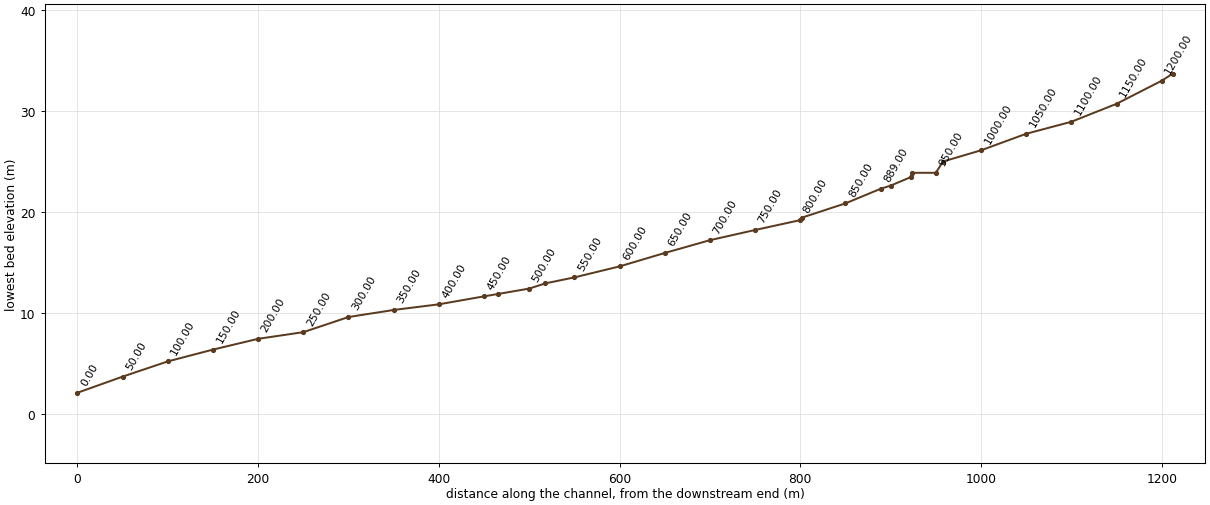
--- jdc.prj (project) ---

Proj Title=jeopdong-ch
Current Plan=p01
Default Exp/Contr=.3,.1
SI Units
Geom File=g01
Flow File=f01
Plan File=p01
Y Axis Title=Elevation
X Axis Title(PF)=Main Channel Distance
X Axis Title(XS)=Station
BEGIN DESCRIPTION:
           BACK WATER COMPUTATION
      APPLICATION OF HEC-2 BY Samju Construction Engineering
      Á¢µ¿Ãµ(¿ËÃµÀ¾): 30,50,80,100,150³âºóµµ °³¼öÀü
END DESCRIPTION:
DSS Export Rating Curves= 0
DSS Export Rating Curve Sorted= 0
DSS Export Volume Flow Curves= 0
DXF OffsetX= 0
DXF OffsetY= 0
DXF ScaleX= 1
DXF ScaleY= 10

--- jdc.p01 (plan) ---

Plan Title=Imported Plan 01
Version=Version 3.0.1  Mar 2001
Short Identifier=Imported Pla
Geom File=g01
Flow File=f01
Subcritical Flow
K Sum by GR= 0
Std Step Tol= 0.003
Critical Tol= 0.003
Num of Std Step Trials= 20
Max Error Tol= 0.1
Flow Tol Ratio= 0.001
Split Flow NTrial= 30
Split Flow Tol= 0.02
Split Flow Ratio= 0.02
Log Output Level= 0
Friction Slope Method= 1
Unsteady Friction Slope Method= 2
Parabolic Critical Depth
Global Vel Dist= 0 , 0 , 0
Global Log Level= 0
CheckData=True
Encroach Param=-1 ,0,0, 0
Computation Interval=1HOUR
Output Interval=1HOUR
Run HTab= 0
Run UNet= 0
Run PostProcess= 0
UNET Theta= 1
UNET ZTol= 0.02
UNET ZSATol= 0.1
UNET MxIter= 20
UNET MaxInSteps= 20
UNET DtIC= 0
UNET DtMin= 0
UNET MaxCRTS= 20
UNET WFStab= 2
UNET SFStab= 1
UNET WFX= 1
UNET SFX= 1
UNET Convert EG Bridges=-1
UNET Use Existing IB Tables=-1
Instantaneous Interval=1HOUR
Write IC File= 0
Write Velocity= 0
Write Detailed= 0

--- jdc.f01 (steady flow) ---

Flow Title=Imported Flow 01
Version=Version 3.0.1  Mar 2001
Number of Profiles= 5
Profile Names=10YR,20YR,30YR,50YR,80YR
River Rch & RM=RIVER-1,Reach-1         ,24.012
   14.58   16.06   16.93   18.02   19.03
River Rch & RM=jeopdong,jeopdong        ,1212.00
   14.58   16.06   16.93   18.02   19.03
Boundary for River Rch & Prof#=jeopdong,jeopdong        , 1
Up Type= 0
Dn Type= 3
Dn Slope=.026
Boundary for River Rch & Prof#=jeopdong,jeopdong        , 2
Up Type= 0
Dn Type= 3
Dn Slope=.026
Boundary for River Rch & Prof#=jeopdong,jeopdong        , 3
Up Type= 0
Dn Type= 3
Dn Slope=.026
Boundary for River Rch & Prof#=jeopdong,jeopdong        , 4
Up Type= 0
Dn Type= 3
Dn Slope=.026
Boundary for River Rch & Prof#=jeopdong,jeopdong        , 5
Up Type= 0
Dn Type= 3
Dn Slope=.026
DSS Import GetInterval= 0
DSS Import GetPeak= 0
DSS Import FillOption= 0

--- jdc.g01 (geometry) ---

Geom Title=Imported Geom 01
Version=Version 3.0.1  Mar 2001

River Reach=jeopdong        ,jeopdong
Reach XY= 2
              .5             .95              .5             .05

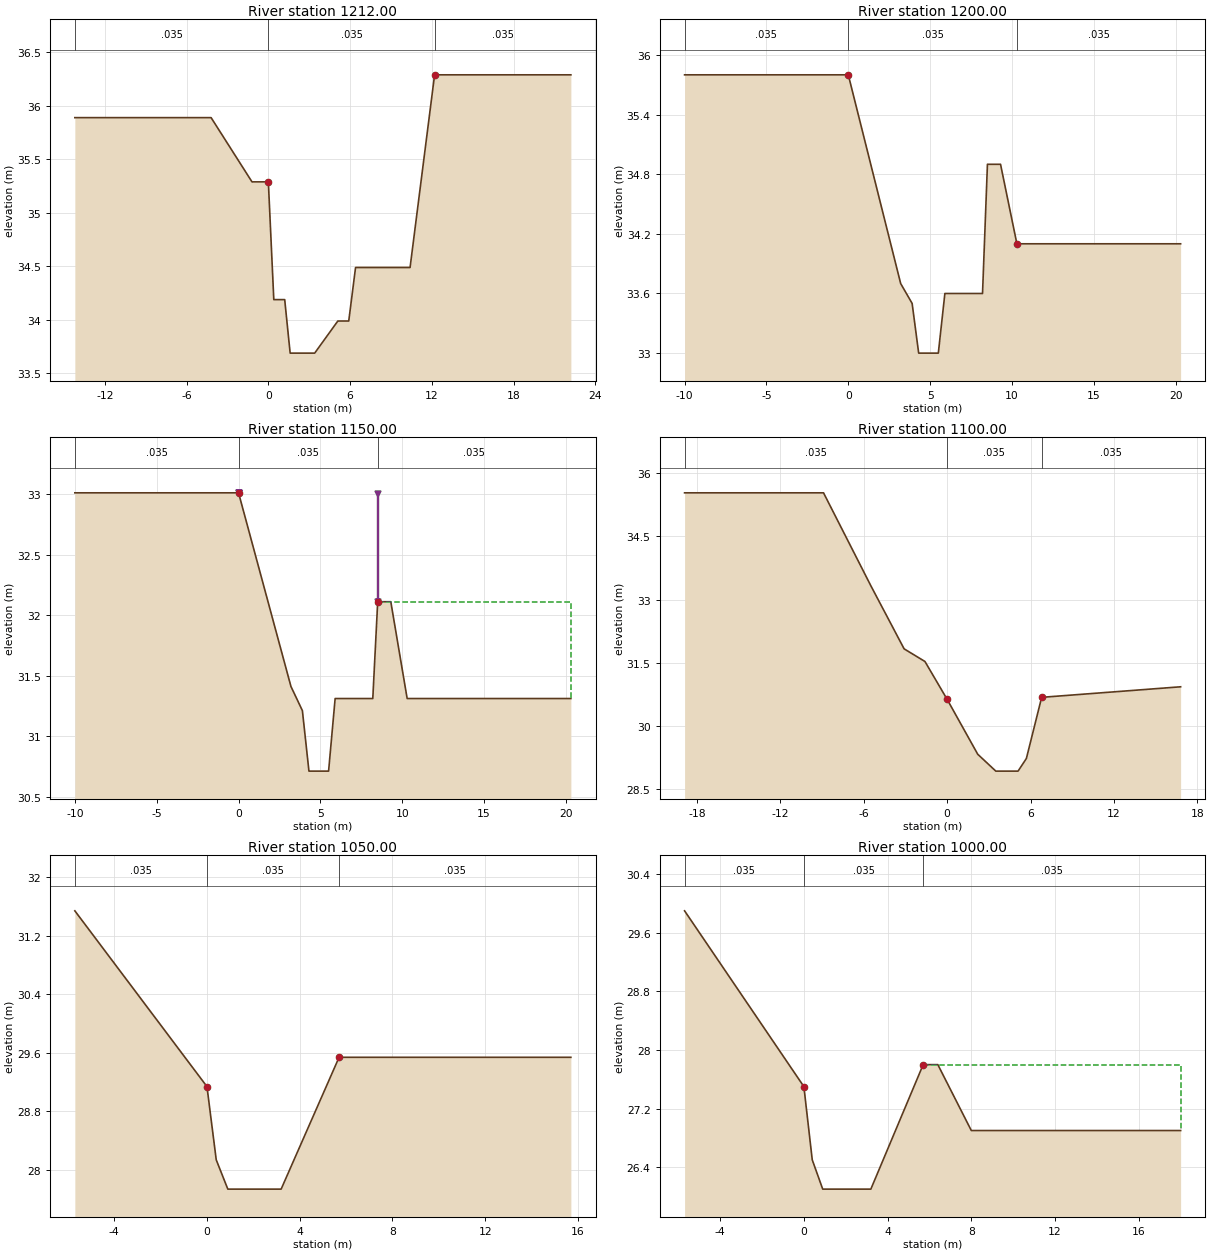
Type RM Length L Ch R = 1 ,1212.00 ,12,12,12
BEGIN DESCRIPTION:
24.012
END DESCRIPTION:
#Sta/Elev= 14
   -14.2   35.89    -4.2   35.89    -1.2   35.29       0   35.29      .4   34.19
     1.2   34.19     1.6   33.69     3.4   33.69     5.1   33.99     5.9   33.99
     6.4   34.49    10.4   34.49    12.2   36.29    22.2   36.29
#Mann= 3 , 0 , 0
   -14.2    .035       0       0    .035       0    12.2    .035       0
#XS Ineff= 2 , 0
               0   35.29    12.2           36.29
Permanent Ineff=
       F       F
Bank Sta=0,12.2
XS Rating Curve= 0
Exp/Cntr=.3,.1

Type RM Length L Ch R = 1 ,1200.00 ,50,50,50
BEGIN DESCRIPTION:
24
END DESCRIPTION:
#Sta/Elev= 12
     -10    35.8       0    35.8     3.2    33.7     3.9    33.5     4.3      33
     5.5      33     5.9    33.6     8.2    33.6     8.5    34.9     9.3    34.9
    10.3    34.1    20.3    34.1
#Mann= 3 , 0 , 0
     -10    .035       0       0    .035       0    10.3    .035       0
#XS Ineff= 2 , 0
               0    35.8    10.3            34.1
Permanent Ineff=
       F       F
Bank Sta=0,10.3
XS Rating Curve= 0
Exp/Cntr=.3,.1

Type RM Length L Ch R = 1 ,1150.00 ,50,50,50
BEGIN DESCRIPTION:
23
END DESCRIPTION:
#Sta/Elev= 12
     -10   33.01       0   33.01     3.2   31.41     3.9   31.21     4.3   30.71
     5.5   30.71     5.9   31.31     8.2   31.31     8.5   32.11     9.3   32.11
    10.3   31.31    20.3   31.31
#Mann= 3 , 0 , 0
     -10    .035       0       0    .035       0     8.5    .035       0
Levee=-1,0,33.01,-1,8.5,33,,
#XS Ineff= 2 , 0
               0   33.01     8.5           32.11
Permanent Ineff=
       F       F
Bank Sta=0,8.5
XS Rating Curve= 0
Exp/Cntr=.3,.1

Type RM Length L Ch R = 1 ,1100.00 ,50,50,50
BEGIN DESCRIPTION:
22
END DESCRIPTION:
#Sta/Elev= 12
   -18.9   35.53    -8.9   35.53    -5.5   33.33    -3.1   31.83    -1.6   31.53
       0   30.63     2.2   29.33     3.5   28.93     5.1   28.93     5.7   29.23
     6.8   30.68    16.8   30.93
#Mann= 3 , 0 , 0
   -18.9    .035       0       0    .035       0     6.8    .035       0
#XS Ineff= 2 , 0
               0   30.63     6.8           30.68
Permanent Ineff=
       F       F
Bank Sta=0,6.8
XS Rating Curve= 0
Exp/Cntr=.3,.1

Type RM Length L Ch R = 1 ,1050.00 ,50,50,50
BEGIN DESCRIPTION:
21
END DESCRIPTION:
#Sta/Elev= 9
    -5.7   31.54    -3.8   30.74    -1.9   29.94       0   29.14      .4   28.14
      .9   27.74     3.2   27.74     5.7   29.54    15.7   29.54
#Mann= 3 , 0 , 0
    -5.7    .035       0       0    .035       0     5.7    .035       0
#XS Ineff= 2 , 0
               0   29.14     5.7           29.54
Permanent Ineff=
       F       F
Bank Sta=0,5.7
XS Rating Curve= 0
Exp/Cntr=.3,.1

Type RM Length L Ch R = 1 ,1000.00 ,42,42,42
BEGIN DESCRIPTION:
20
END DESCRIPTION:
#Sta/Elev= 11
    -5.7    29.9    -3.8    29.1    -1.9    28.3       0    27.5      .4    26.5
      .9    26.1     3.2    26.1     5.7    27.8     6.4    27.8       8    26.9
      18    26.9
#Mann= 3 , 0 , 0
    -5.7    .035       0       0    .035       0     5.7    .035       0
#XS Ineff= 2 , 0
               0    27.5     5.7            27.8
Permanent Ineff=
       F       F
Bank Sta=0,5.7
XS Rating Curve= 0
Exp/Cntr=.3,.1

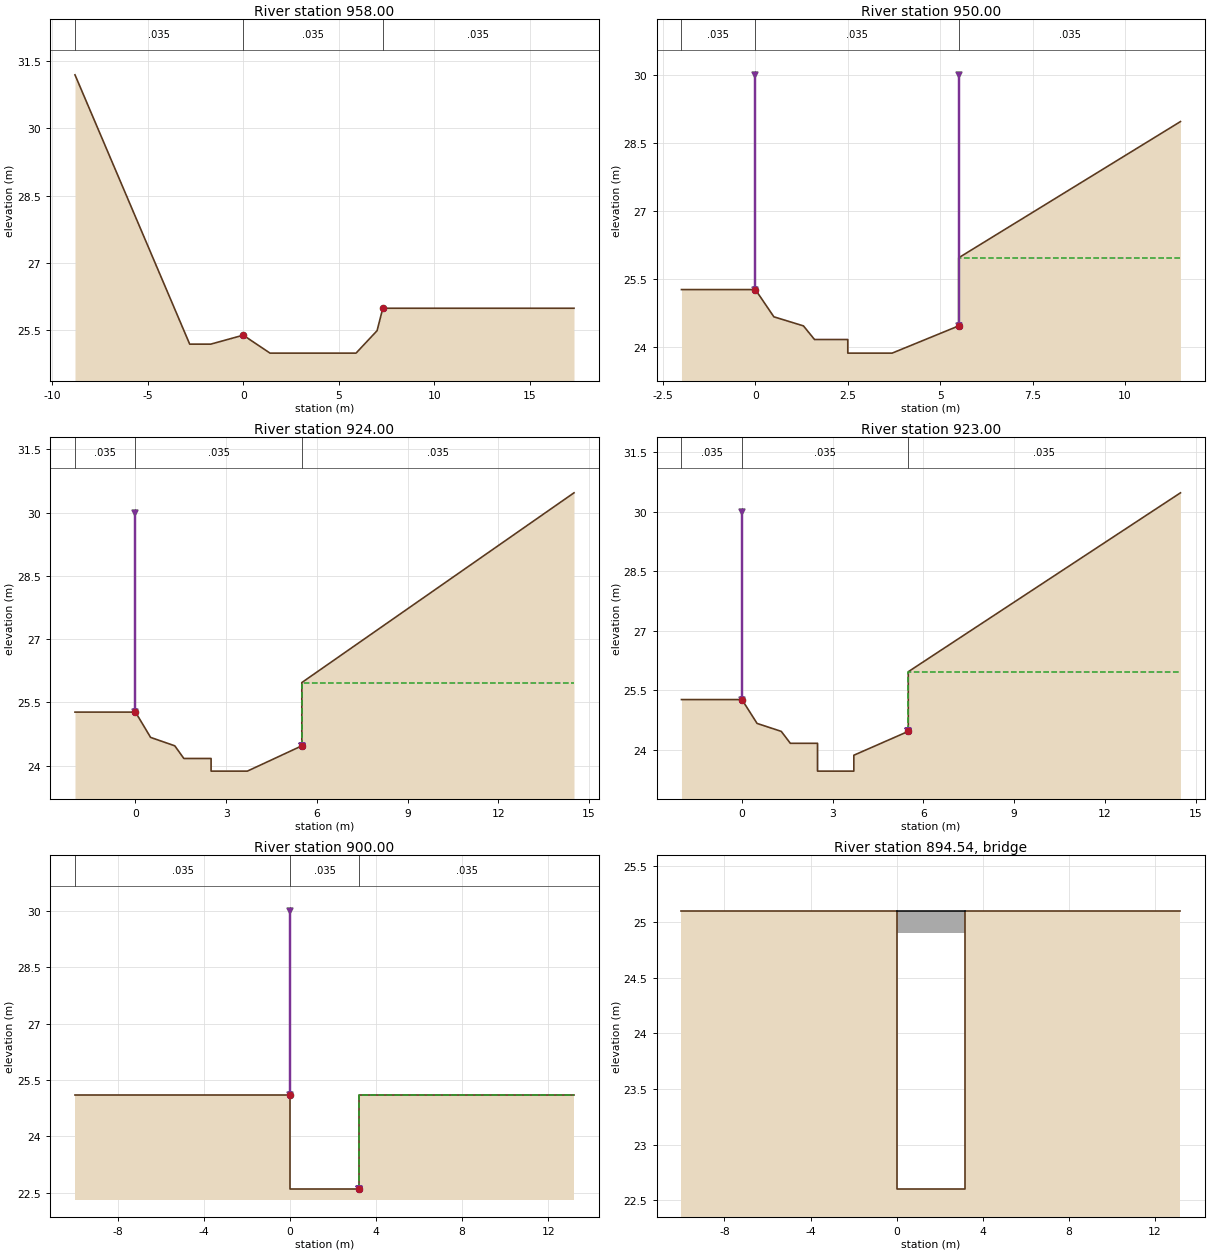
Type RM Length L Ch R = 1 ,958.00  ,8,8,8
BEGIN DESCRIPTION:
19.008
END DESCRIPTION:
#Sta/Elev= 10
    -8.8   31.19    -5.8   28.19    -2.8   25.19    -1.7   25.19       0   25.39
     1.4   24.99     5.9   24.99       7   25.49     7.3   25.99    17.3   25.99
#Mann= 3 , 0 , 0
    -8.8    .035       0       0    .035       0     7.3    .035       0
#XS Ineff= 2 , 0
               0   25.39     7.3           25.99
Permanent Ineff=
       F       F
Bank Sta=0,7.3
XS Rating Curve= 0
Exp/Cntr=.3,.1

Type RM Length L Ch R = 1 ,950.00  ,26,26,26
BEGIN DESCRIPTION:
19
END DESCRIPTION:
#Sta/Elev= 12
      -2   25.27       0   25.27      .5   24.67     1.3   24.47     1.6   24.17
     2.5   24.17     2.5   23.87     3.7   23.87     5.5   24.47     5.5   25.97
     8.5   27.47    11.5   28.97
#Mann= 3 , 0 , 0
      -2    .035       0       0    .035       0     5.5    .035       0
Levee=-1,0,30,-1,5.5,30,,
#XS Ineff= 2 , 0
               0   25.27     5.5           25.97
Permanent Ineff=
       F       F
Bank Sta=0,5.5
XS Rating Curve= 0
Exp/Cntr=.3,.1

Type RM Length L Ch R = 1 ,924.00  ,1,1,1
BEGIN DESCRIPTION:
18.024
END DESCRIPTION:
#Sta/Elev= 13
      -2   25.27       0   25.27      .5   24.67     1.3   24.47     1.6   24.17
     2.5   24.17     2.5   23.87     3.7   23.87     5.5   24.47     5.5   25.97
     8.5   27.47    11.5   28.97    14.5   30.47
#Mann= 3 , 0 , 0
      -2    .035       0       0    .035       0     5.5    .035       0
Levee=-1,0,30,-1,5.5,24.47,,
#XS Ineff= 2 , 0
               0   25.27     5.5           25.97
Permanent Ineff=
       F       F
Bank Sta=0,5.5
XS Rating Curve= 0
Exp/Cntr=.3,.1

Type RM Length L Ch R = 1 ,923.00  ,23,23,23
BEGIN DESCRIPTION:
18.023
END DESCRIPTION:
#Sta/Elev= 15
      -2   25.27       0   25.27      .5   24.67     1.3   24.47     1.6   24.17
     2.5   24.17     2.5   23.87     2.5   23.47     3.7   23.47     3.7   23.87
     5.5   24.47     5.5   25.97     8.5   27.47    11.5   28.97    14.5   30.47
#Mann= 3 , 0 , 0
      -2    .035       0       0    .035       0     5.5    .035       0
Levee=-1,0,30,-1,5.5,24.47,,
#XS Ineff= 2 , 0
               0   25.27     5.5           25.97
Permanent Ineff=
       F       F
Bank Sta=0,5.5
XS Rating Curve= 0
Exp/Cntr=.3,.1

Type RM Length L Ch R = 1 ,900.00  ,11,11,11
BEGIN DESCRIPTION:
18
END DESCRIPTION:
#Sta/Elev= 6
     -10    25.1       0    25.1       0    22.6     3.2    22.6     3.2    25.1
    13.2    25.1
#Mann= 3 , 0 , 0
     -10    .035       0       0    .035       0     3.2    .035       0
Levee=-1,0,30,-1,3.2,22.6,,
#XS Ineff= 2 , 0
               0    25.1     3.2            25.1
Permanent Ineff=
       F       F
Bank Sta=0,3.2
XS Rating Curve= 0
Exp/Cntr=.3,.1

Type RM Length L Ch R = 3 ,894.54  ,,,
BEGIN DESCRIPTION:
17.0445
END DESCRIPTION:
Bridge Culvert--1,0,-1,-1, 0
Deck Dist Width WeirC Skew NumUp NumDn MinLoCord MaxHiCord MaxSubmerge Is_Ogee
.01,10.9,1.44,0, 2, 2, , , .95, 0, 0,0,,
       0     3.2
    25.1    25.1
    24.9    24.9
       0     3.2
   24.79   24.79
   24.59   24.59
BR Coef=-1 , 1 , 0 ,, 0 ,,,.8,-1,1.2,0,
WSPro=,,,, 1 ,,,, 0 ,,,, 0 ,,,,-1 ,-1 ,-1 , 0 , 0 , 0 , 0 , 0
BC Design=,, 0 ,, 0 ,,,,,,

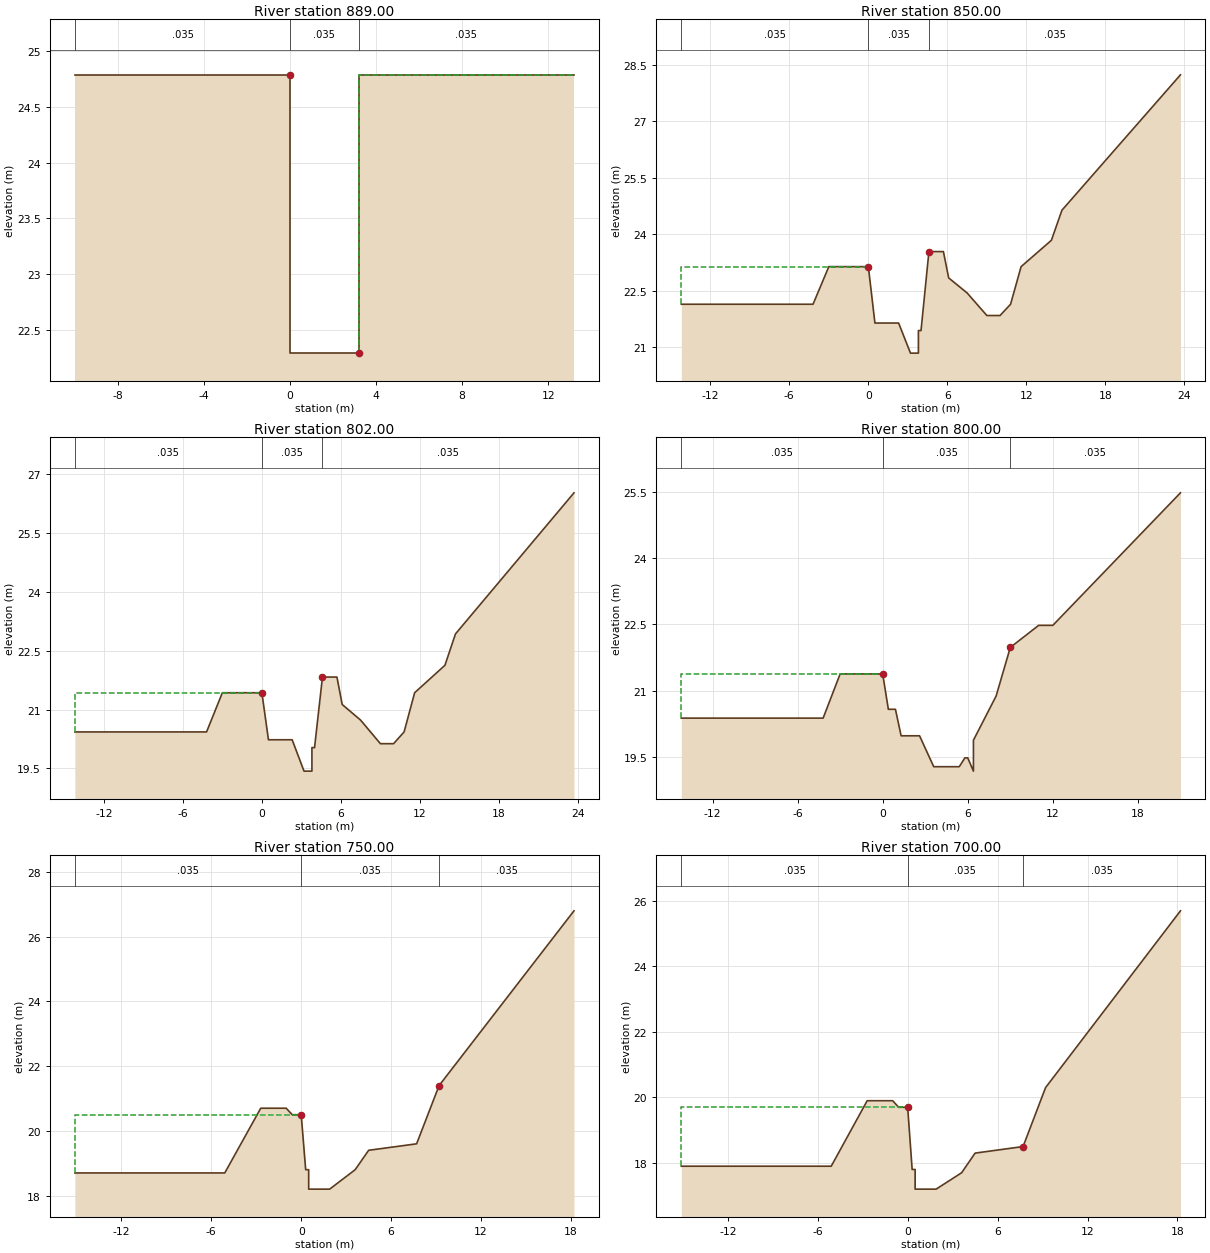
Type RM Length L Ch R = 1 ,889.00  ,39,39,39
BEGIN DESCRIPTION:
17.039
END DESCRIPTION:
#Sta/Elev= 6
     -10   24.79       0   24.79       0   22.29     3.2   22.29     3.2   24.79
    13.2   24.79
#Mann= 3 , 0 , 0
     -10    .035       0       0    .035       0     3.2    .035       0
#XS Ineff= 2 , 0
               0   24.79     3.2           24.79
Permanent Ineff=
       F       F
Bank Sta=0,3.2
XS Rating Curve= 0
Exp/Cntr=.3,.1

Type RM Length L Ch R = 1 ,850.00  ,48,48,48
BEGIN DESCRIPTION:
17
END DESCRIPTION:
#Sta/Elev= 23
   -14.2   22.14    -4.2   22.14      -3   23.14       0   23.14      .5   21.64
     2.3   21.64     3.2   20.84     3.8   20.84     3.8   21.44       4   21.44
     4.6   23.54     5.7   23.54     6.1   22.84     7.5   22.44       9   21.84
      10   21.84    10.8   22.14    11.6   23.14    13.9   23.84    14.7   24.64
    17.7   25.84    20.7   27.04    23.7   28.24
#Mann= 3 , 0 , 0
   -14.2    .035       0       0    .035       0     4.6    .035       0
#XS Ineff= 2 , 0
               0   23.14     4.6           23.54
Permanent Ineff=
       F       F
Bank Sta=0,4.6
XS Rating Curve= 0
Exp/Cntr=.3,.1

Type RM Length L Ch R = 1 ,802.00  ,2,2,2
BEGIN DESCRIPTION:
16.002
END DESCRIPTION:
#Sta/Elev= 23
   -14.2   20.43    -4.2   20.43      -3   21.43       0   21.43      .5   20.23
     2.3   20.23     3.2   19.43     3.8   19.43     3.8   20.03       4   20.03
     4.6   21.83     5.7   21.83     6.1   21.13     7.5   20.73       9   20.13
      10   20.13    10.8   20.43    11.6   21.43    13.9   22.13    14.7   22.93
    17.7   24.13    20.7   25.33    23.7   26.53
#Mann= 3 , 0 , 0
   -14.2    .035       0       0    .035       0     4.6    .035       0
#XS Ineff= 2 , 0
               0   21.43     4.6           21.83
Permanent Ineff=
       F       F
Bank Sta=0,4.6
XS Rating Curve= 0
Exp/Cntr=.3,.1

Type RM Length L Ch R = 1 ,800.00  ,50,50,50
BEGIN DESCRIPTION:
16
END DESCRIPTION:
#Sta/Elev= 21
   -14.2   20.38    -4.2   20.38      -3   21.38       0   21.38      .4   20.58
      .9   20.58     1.3   19.98     2.6   19.98     3.6   19.28     5.4   19.28
     5.8   19.48       6   19.48     6.4   19.18     6.4   19.88       8   20.88
       9   21.98      11   22.48      12   22.48      15   23.48      18   24.48
      21   25.48
#Mann= 3 , 0 , 0
   -14.2    .035       0       0    .035       0       9    .035       0
#XS Ineff= 2 , 0
               0   21.38       9           21.98
Permanent Ineff=
       F       F
Bank Sta=0,9
XS Rating Curve= 0
Exp/Cntr=.3,.1

Type RM Length L Ch R = 1 ,750.00  ,50,50,50
BEGIN DESCRIPTION:
15
END DESCRIPTION:
#Sta/Elev= 17
   -15.1    18.7    -5.1    18.7    -2.7    20.7      -1    20.7     -.6    20.5
       0    20.5      .3    18.8      .5    18.8      .5    18.2     1.9    18.2
     3.6    18.8     4.5    19.4     7.7    19.6     9.2    21.4    12.2    23.2
    15.2      25    18.2    26.8
#Mann= 3 , 0 , 0
   -15.1    .035       0       0    .035       0     9.2    .035       0
#XS Ineff= 2 , 0
               0    20.5     9.2            21.4
Permanent Ineff=
       F       F
Bank Sta=0,9.2
XS Rating Curve= 0
Exp/Cntr=.3,.1

Type RM Length L Ch R = 1 ,700.00  ,50,50,50
BEGIN DESCRIPTION:
14
END DESCRIPTION:
#Sta/Elev= 17
   -15.1   17.89    -5.1   17.89    -2.7   19.89      -1   19.89     -.6   19.69
       0   19.69      .3   17.79      .5   17.79      .5   17.19     1.9   17.19
     3.6   17.69     4.5   18.29     7.7   18.49     9.2   20.29    12.2   22.09
    15.2   23.89    18.2   25.69
#Mann= 3 , 0 , 0
   -15.1    .035       0       0    .035       0     7.7    .035       0
#XS Ineff= 2 , 0
               0   19.69     7.7           18.49
Permanent Ineff=
       F       F
Bank Sta=0,7.7
XS Rating Curve= 0
Exp/Cntr=.3,.1

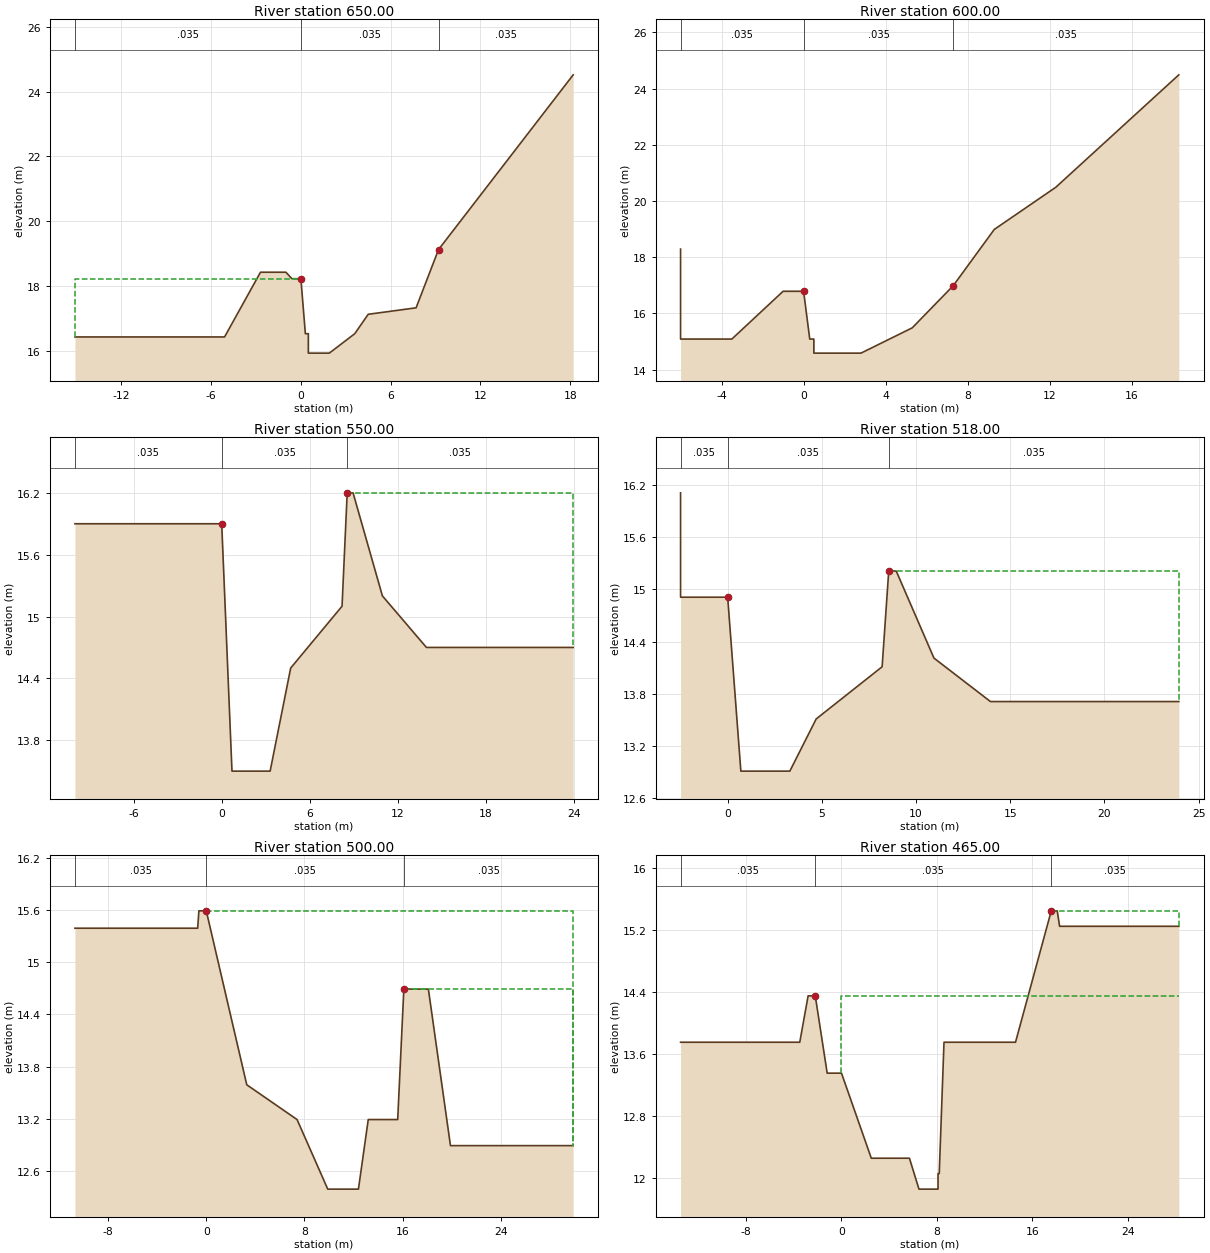
Type RM Length L Ch R = 1 ,650.00  ,50,50,50
BEGIN DESCRIPTION:
13
END DESCRIPTION:
#Sta/Elev= 17
   -15.1   16.42    -5.1   16.42    -2.7   18.42      -1   18.42     -.6   18.22
       0   18.22      .3   16.52      .5   16.52      .5   15.92     1.9   15.92
     3.6   16.52     4.5   17.12     7.7   17.32     9.2   19.12    12.2   20.92
    15.2   22.72    18.2   24.52
#Mann= 3 , 0 , 0
   -15.1    .035       0       0    .035       0     9.2    .035       0
#XS Ineff= 2 , 0
               0   18.22     9.2           19.12
Permanent Ineff=
       F       F
Bank Sta=0,9.2
XS Rating Curve= 0
Exp/Cntr=.3,.1

Type RM Length L Ch R = 1 ,600.00  ,50,50,50
BEGIN DESCRIPTION:
12
END DESCRIPTION:
#Sta/Elev= 15
      -6   18.29      -6   15.09    -3.5   15.09      -1   16.79       0   16.79
      .3   15.09      .5   15.09      .5   14.59     2.8   14.59     5.3   15.49
     7.3   16.99     9.3   18.99    12.3   20.49    15.3   22.49    18.3   24.49
#Mann= 3 , 0 , 0
      -6    .035       0       0    .035       0     7.3    .035       0
#XS Ineff= 2 , 0
               0   16.79     7.3           16.99
Permanent Ineff=
       F       F
Bank Sta=0,7.3
XS Rating Curve= 0
Exp/Cntr=.3,.1

Type RM Length L Ch R = 1 ,550.00  ,32,32,32
BEGIN DESCRIPTION:
11
END DESCRIPTION:
#Sta/Elev= 11
     -10    15.9       0    15.9      .7    13.5     3.3    13.5     4.7    14.5
     8.2    15.1    8.55    16.2    8.95    16.2   10.95    15.2   13.95    14.7
   23.95    14.7
#Mann= 3 , 0 , 0
     -10    .035       0       0    .035       0    8.55    .035       0
#XS Ineff= 2 , 0
               0    15.9    8.55            16.2
Permanent Ineff=
       F       F
Bank Sta=0,8.55
XS Rating Curve= 0
Exp/Cntr=.3,.1

Type RM Length L Ch R = 1 ,518.00  ,18,18,18
BEGIN DESCRIPTION:
10.018
END DESCRIPTION:
#Sta/Elev= 12
    -2.5   16.11    -2.5   14.91       0   14.91      .7   12.91     3.3   12.91
     4.7   13.51     8.2   14.11    8.55   15.21    8.95   15.21   10.95   14.21
   13.95   13.71   23.95   13.71
#Mann= 3 , 0 , 0
    -2.5    .035       0       0    .035       0    8.55    .035       0
#XS Ineff= 2 , 0
               0   14.91    8.55           15.21
Permanent Ineff=
       F       F
Bank Sta=0,8.55
XS Rating Curve= 0
Exp/Cntr=.3,.1

Type RM Length L Ch R = 1 ,500.00  ,35,35,35
BEGIN DESCRIPTION:
10
END DESCRIPTION:
#Sta/Elev= 14
   -10.7   15.39     -.7   15.39     -.6   15.59       0   15.59     3.3   13.59
     7.4   13.19     9.9   12.39    12.4   12.39    13.2   13.19    15.6   13.19
    16.1   14.69    18.1   14.69    19.9   12.89    29.9   12.89
#Mann= 3 , 0 , 0
   -10.7    .035       0       0    .035       0    16.1    .035       0
#XS Ineff= 2 , 0
       0       0   15.59    16.1       0   14.69
Permanent Ineff=
       F       F
Bank Sta=0,16.1
XS Rating Curve= 0
Exp/Cntr=.3,.1

Type RM Length L Ch R = 1 ,465.00  ,15,15,15
BEGIN DESCRIPTION:
9.015
END DESCRIPTION:
#Sta/Elev= 18
   -13.5   13.75    -3.5   13.75    -2.8   14.35    -2.2   14.35    -1.2   13.35
       0   13.35     2.5   12.25     5.7   12.25     6.5   11.85     8.1   11.85
     8.1   12.05     8.2   12.05     8.6   13.75    14.6   13.75    17.6   15.45
    18.1   15.45    18.3   15.25    28.3   15.25
#Mann= 3 , 0 , 0
   -13.5    .035       0    -2.2    .035       0    17.6    .035       0
#XS Ineff= 2 , 0
       0    -2.2   14.35    17.6       0   15.45
Permanent Ineff=
       F       F
Bank Sta=-2.2,17.6
XS Rating Curve= 0
Exp/Cntr=.3,.1

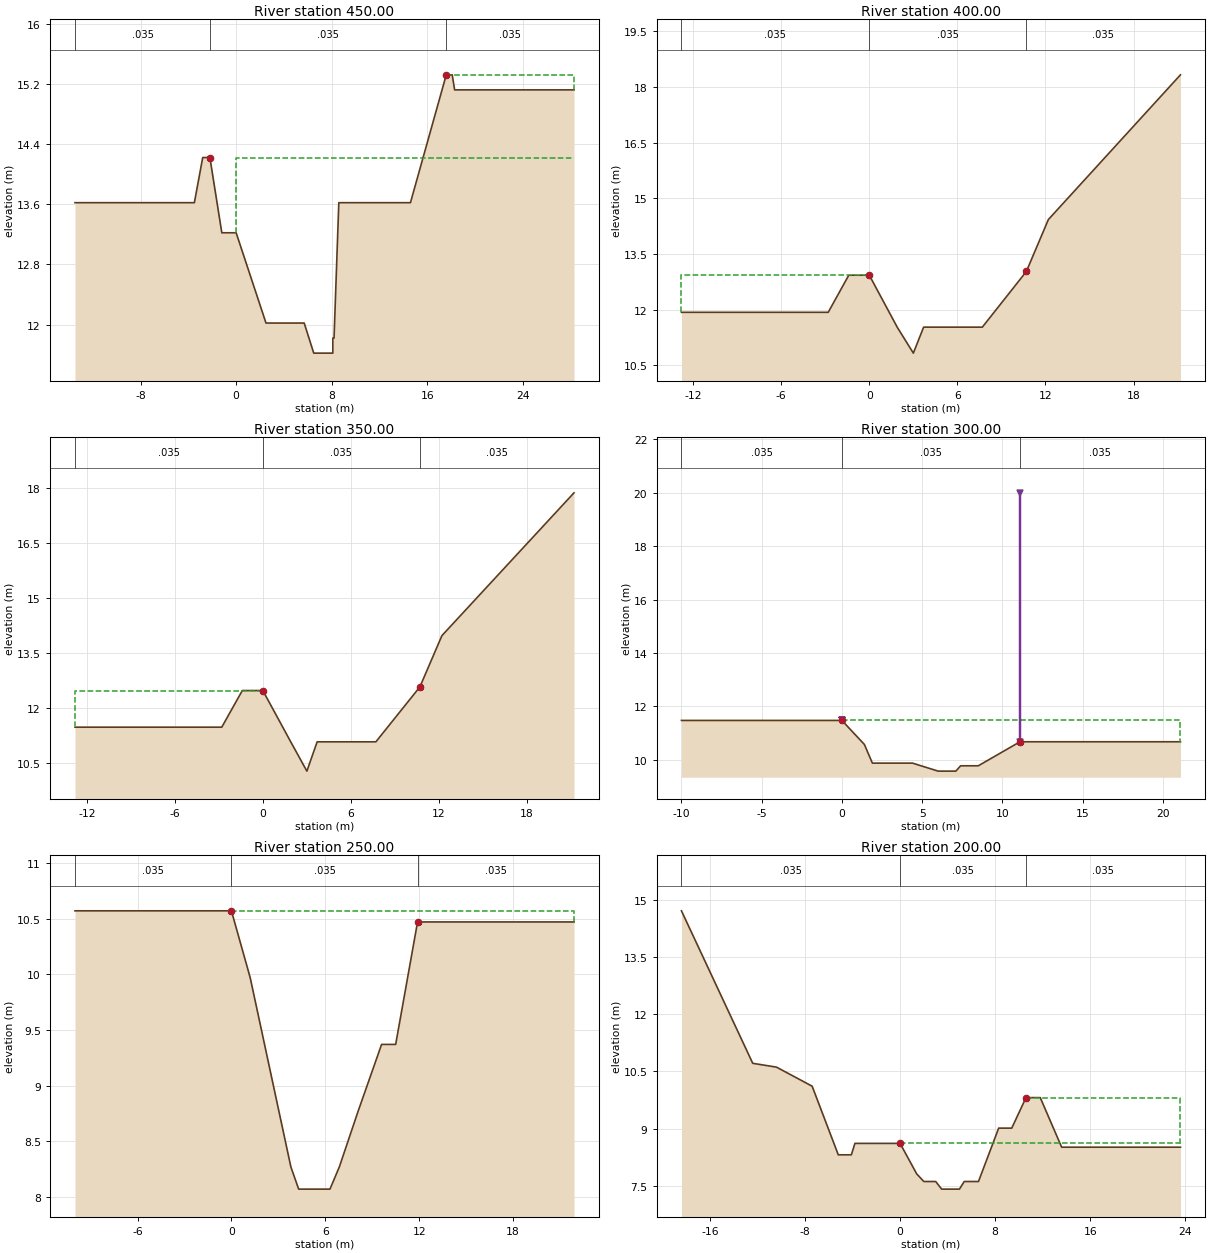
Type RM Length L Ch R = 1 ,450.00  ,50,50,50
BEGIN DESCRIPTION:
9
END DESCRIPTION:
#Sta/Elev= 18
   -13.5   13.62    -3.5   13.62    -2.8   14.22    -2.2   14.22    -1.2   13.22
       0   13.22     2.5   12.02     5.7   12.02     6.5   11.62     8.1   11.62
     8.1   11.82     8.2   11.82     8.6   13.62    14.6   13.62    17.6   15.32
    18.1   15.32    18.3   15.12    28.3   15.12
#Mann= 3 , 0 , 0
   -13.5    .035       0    -2.2    .035       0    17.6    .035       0
#XS Ineff= 2 , 0
       0    -2.2   14.22    17.6       0   15.32
Permanent Ineff=
       F       F
Bank Sta=-2.2,17.6
XS Rating Curve= 0
Exp/Cntr=.3,.1

Type RM Length L Ch R = 1 ,400.00  ,50,50,50
BEGIN DESCRIPTION:
8
END DESCRIPTION:
#Sta/Elev= 13
   -12.8   11.93    -2.8   11.93    -1.4   12.93       0   12.93     1.9   11.53
       3   10.83     3.7   11.53     7.7   11.53    10.7   13.03    12.2   14.43
    15.2   15.73    18.2   17.03    21.2   18.33
#Mann= 3 , 0 , 0
   -12.8    .035       0       0    .035       0    10.7    .035       0
#XS Ineff= 2 , 0
               0   12.93    10.7           13.03
Permanent Ineff=
       F       F
Bank Sta=0,10.7
XS Rating Curve= 0
Exp/Cntr=.3,.1

Type RM Length L Ch R = 1 ,350.00  ,50,50,50
BEGIN DESCRIPTION:
7
END DESCRIPTION:
#Sta/Elev= 13
   -12.8   11.47    -2.8   11.47    -1.4   12.47       0   12.47     1.9   11.07
       3   10.27     3.7   11.07     7.7   11.07    10.7   12.57    12.2   13.97
    15.2   15.27    18.2   16.57    21.2   17.87
#Mann= 3 , 0 , 0
   -12.8    .035       0       0    .035       0    10.7    .035       0
#XS Ineff= 2 , 0
               0   12.47    10.7           12.57
Permanent Ineff=
       F       F
Bank Sta=0,10.7
XS Rating Curve= 0
Exp/Cntr=.3,.1

Type RM Length L Ch R = 1 ,300.00  ,50,50,50
BEGIN DESCRIPTION:
6
END DESCRIPTION:
#Sta/Elev= 11
     -10   11.47       0   11.47     1.4   10.57     1.9    9.87     4.4    9.87
       6    9.57     7.1    9.57     7.4    9.77     8.5    9.77    11.1   10.67
    21.1   10.67
#Mann= 3 , 0 , 0
     -10    .035       0       0    .035       0    11.1    .035       0
Levee=-1,0,11.47,-1,11.1,20,,
#XS Ineff= 2 , 0
       0       0   11.47    11.1       0   10.67
Permanent Ineff=
       F       F
Bank Sta=0,11.1
XS Rating Curve= 0
Exp/Cntr=.3,.1

Type RM Length L Ch R = 1 ,250.00  ,50,50,50
BEGIN DESCRIPTION:
5
END DESCRIPTION:
#Sta/Elev= 12
     -10   10.57       0   10.57     1.2    9.97     3.8    8.27     4.3    8.07
     6.3    8.07     6.9    8.27     8.1    8.77     9.6    9.37    10.5    9.37
    11.9   10.47    21.9   10.47
#Mann= 3 , 0 , 0
     -10    .035       0       0    .035       0    11.9    .035       0
#XS Ineff= 2 , 0
       0       0   10.57    11.9       0   10.47
Permanent Ineff=
       F       F
Bank Sta=0,11.9
XS Rating Curve= 0
Exp/Cntr=.3,.1

Type RM Length L Ch R = 1 ,200.00  ,50,50,50
BEGIN DESCRIPTION:
4
END DESCRIPTION:
#Sta/Elev= 22
   -18.4   14.71   -15.4   12.71   -12.4   10.71   -10.4   10.61    -7.4   10.11
    -5.2    8.31    -4.1    8.31    -3.8    8.61       0    8.61     1.4    7.81
       2    7.61       3    7.61     3.5    7.41       5    7.41     5.4    7.61
     6.6    7.61     8.3    9.01     9.4    9.01    10.6    9.81    11.8    9.81
    13.6    8.51    23.6    8.51
#Mann= 3 , 0 , 0
   -18.4    .035       0       0    .035       0    10.6    .035       0
#XS Ineff= 2 , 0
       0       0    8.61    10.6       0    9.81
Permanent Ineff=
       F       F
Bank Sta=0,10.6
XS Rating Curve= 0
Exp/Cntr=.3,.1

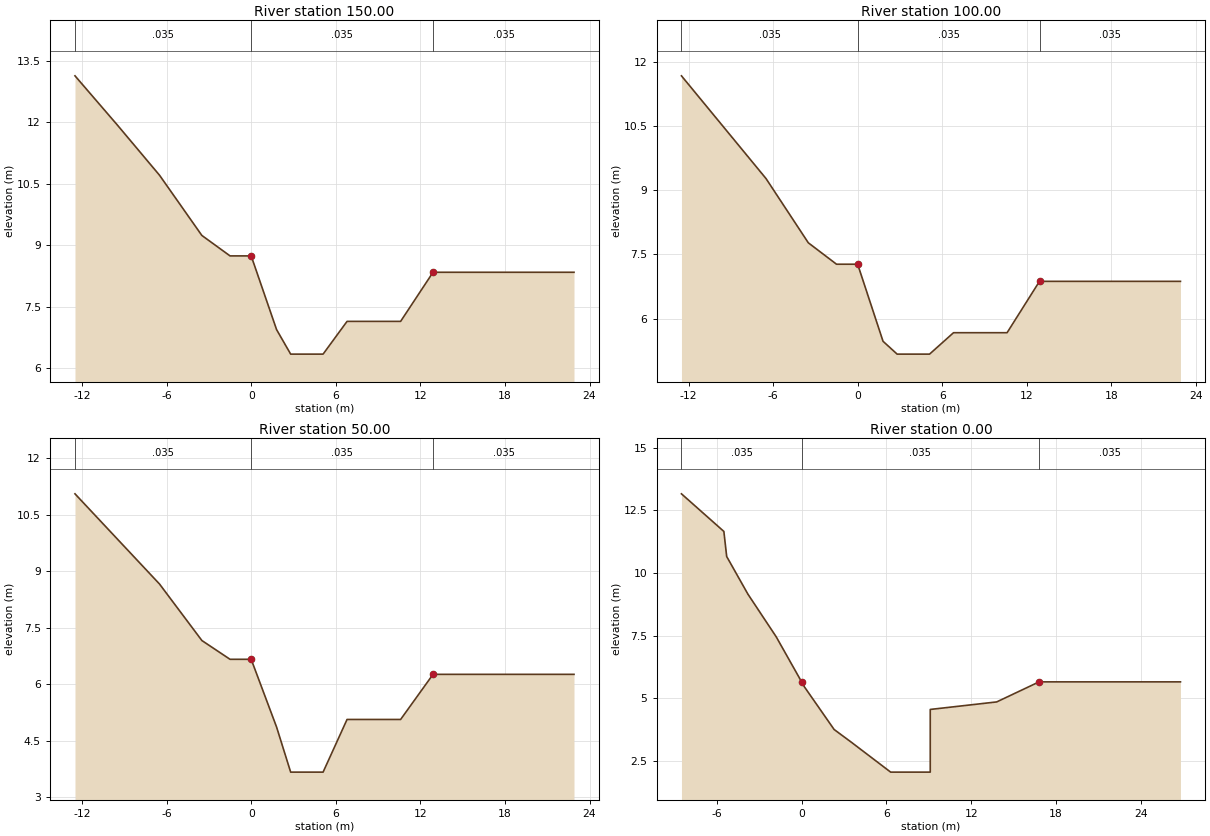
Type RM Length L Ch R = 1 ,150.00  ,50,50,50
BEGIN DESCRIPTION:
3
END DESCRIPTION:
#Sta/Elev= 13
   -12.5   13.14    -9.5   11.94    -6.5   10.71    -3.5    9.24    -1.5    8.74
       0    8.74     1.8    6.94     2.8    6.34     5.1    6.34     6.8    7.14
    10.6    7.14    12.9    8.34    22.9    8.34
#Mann= 3 , 0 , 0
   -12.5    .035       0       0    .035       0    12.9    .035       0
#XS Ineff= 2 , 0
               0    8.74    12.9            8.34
Permanent Ineff=
       F       F
Bank Sta=0,12.9
XS Rating Curve= 0
Exp/Cntr=.3,.1

Type RM Length L Ch R = 1 ,100.00  ,50,50,50
BEGIN DESCRIPTION:
2
END DESCRIPTION:
#Sta/Elev= 13
   -12.5   11.67    -9.5   10.47    -6.5    9.27    -3.5    7.77    -1.5    7.27
       0    7.27     1.8    5.47     2.8    5.17     5.1    5.17     6.8    5.67
    10.6    5.67    12.9    6.87    22.9    6.87
#Mann= 3 , 0 , 0
   -12.5    .035       0       0    .035       0    12.9    .035       0
#XS Ineff= 2 , 0
               0    7.27    12.9            6.87
Permanent Ineff=
       F       F
Bank Sta=0,12.9
XS Rating Curve= 0
Exp/Cntr=.3,.1

Type RM Length L Ch R = 1 ,50.00   ,50,50,50
BEGIN DESCRIPTION:
1
END DESCRIPTION:
#Sta/Elev= 13
   -12.5   11.06    -9.5    9.86    -6.5    8.66    -3.5    7.16    -1.5    6.66
       0    6.66     1.8    4.86     2.8    3.66     5.1    3.66     6.8    5.06
    10.6    5.06    12.9    6.26    22.9    6.26
#Mann= 3 , 0 , 0
   -12.5    .035       0       0    .035       0    12.9    .035       0
#XS Ineff= 2 , 0
               0    6.66    12.9            6.26
Permanent Ineff=
       F       F
Bank Sta=0,12.9
XS Rating Curve= 0
Exp/Cntr=.3,.1

Type RM Length L Ch R = 1 ,0.00    ,0,0,0
BEGIN DESCRIPTION:
0
END DESCRIPTION:
#Sta/Elev= 15
    -8.5   13.16    -5.5   11.66    -5.3   10.66    -3.8    9.16    -1.8    7.46
       0    5.66      .2    5.46     2.3    3.76     3.5    3.26     6.3    2.06
     9.1    2.06     9.1    4.56    13.8    4.86    16.8    5.66    26.8    5.66
#Mann= 3 , 0 , 0
    -8.5    .035       0       0    .035       0    16.8    .035       0
#XS Ineff= 2 , 0
               0    5.66    16.8            5.66
Permanent Ineff=
       F       F
Bank Sta=0,16.8
XS Rating Curve= 0
Exp/Cntr=.3,.1

Chan Stop Cuts=-1