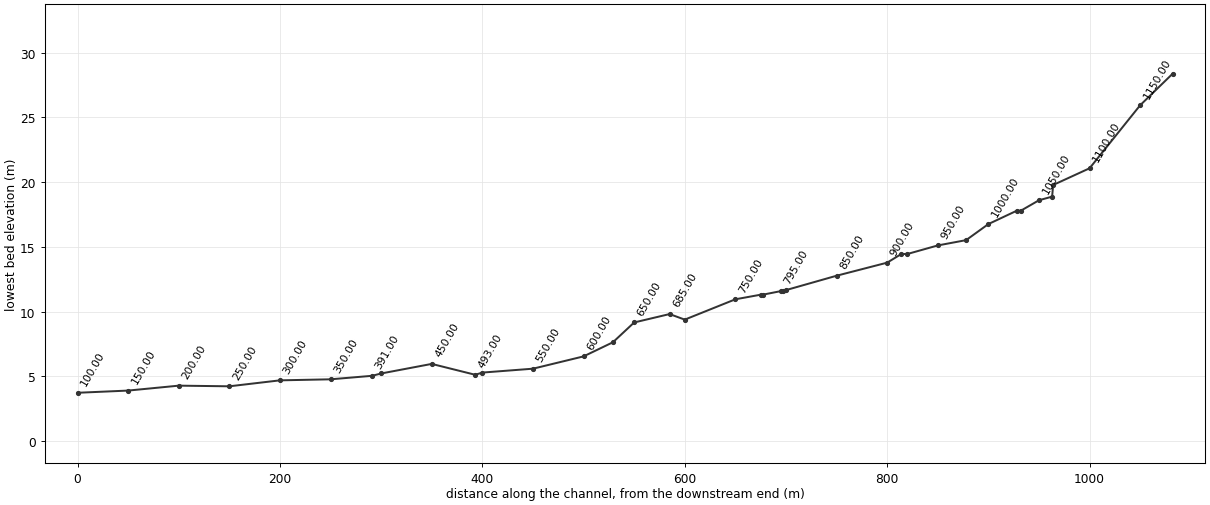
--- bnc.prj (project) ---

Proj Title=beuknam-ch
Current Plan=p01
Default Exp/Contr=.3,.1
SI Units
Geom File=g01
Flow File=f01
Plan File=p01
Y Axis Title=Elevation
X Axis Title(PF)=Main Channel Distance
X Axis Title(XS)=Station
BEGIN DESCRIPTION:
           BACK WATER COMPUTATION
      APPLICATION OF HEC-2 BY Samju Construction Engineering
      º®³²Ãµ(¿ËÃµÀ¾): 30,50,80,100,150³âºóµµ °³¼öÀü
END DESCRIPTION:
DSS Export Rating Curves= 0
DSS Export Rating Curve Sorted= 0
DSS Export Volume Flow Curves= 0
DXF OffsetX= 0
DXF OffsetY= 0
DXF ScaleX= 1
DXF ScaleY= 10

--- bnc.p01 (plan) ---

Plan Title=Imported Plan 01
Version=Version 3.0.1  Mar 2001
Short Identifier=Imported Pla
Geom File=g01
Flow File=f01
Subcritical Flow
K Sum by GR= 0
Std Step Tol= 0.003
Critical Tol= 0.003
Num of Std Step Trials= 20
Max Error Tol= 0.1
Flow Tol Ratio= 0.001
Split Flow NTrial= 30
Split Flow Tol= 0.02
Split Flow Ratio= 0.02
Log Output Level= 0
Friction Slope Method= 1
Unsteady Friction Slope Method= 2
Parabolic Critical Depth
Global Vel Dist= 0 , 0 , 0
Global Log Level= 0
CheckData=True
Encroach Param=-1 ,0,0, 0
Computation Interval=1HOUR
Output Interval=1HOUR
Run HTab= 0
Run UNet= 0
Run PostProcess= 0
UNET Theta= 1
UNET ZTol= 0.02
UNET ZSATol= 0.1
UNET MxIter= 20
UNET MaxInSteps= 20
UNET DtIC= 0
UNET DtMin= 0
UNET MaxCRTS= 20
UNET WFStab= 2
UNET SFStab= 1
UNET WFX= 1
UNET SFX= 1
UNET Convert EG Bridges=-1
UNET Use Existing IB Tables=-1
Instantaneous Interval=1HOUR
Write IC File= 0
Write Velocity= 0
Write Detailed= 0

--- bnc.f01 (steady flow) ---

Flow Title=Imported Flow 01
Version=Version 3.0.1  Mar 2001
Number of Profiles= 5
Profile Names=10yr,20yr,30yr,50yr,80yr
River Rch & RM=RIVER-1,Reach-1         ,23.032
    7.97    8.78    9.26    9.85    10.4
River Rch & RM=beuknam,beuknam         ,1182.00
    7.97    8.78    9.26    9.85    10.4
Boundary for River Rch & Prof#=beuknam,beuknam         , 1
Up Type= 0
Dn Type= 3
Dn Slope=.0243
Boundary for River Rch & Prof#=beuknam,beuknam         , 2
Up Type= 0
Dn Type= 3
Dn Slope=.0243
Boundary for River Rch & Prof#=beuknam,beuknam         , 3
Up Type= 0
Dn Type= 3
Dn Slope=.0243
Boundary for River Rch & Prof#=beuknam,beuknam         , 4
Up Type= 0
Dn Type= 3
Dn Slope=.0243
Boundary for River Rch & Prof#=beuknam,beuknam         , 5
Up Type= 0
Dn Type= 3
Dn Slope=.0243
DSS Import GetInterval= 0
DSS Import GetPeak= 0
DSS Import FillOption= 0

--- bnc.g01 (geometry) ---

Geom Title=Imported Geom 01
Version=Version 3.0.1  Mar 2001

River Reach=beuknam         ,beuknam
Reach XY= 2
              .5             .95              .5             .05

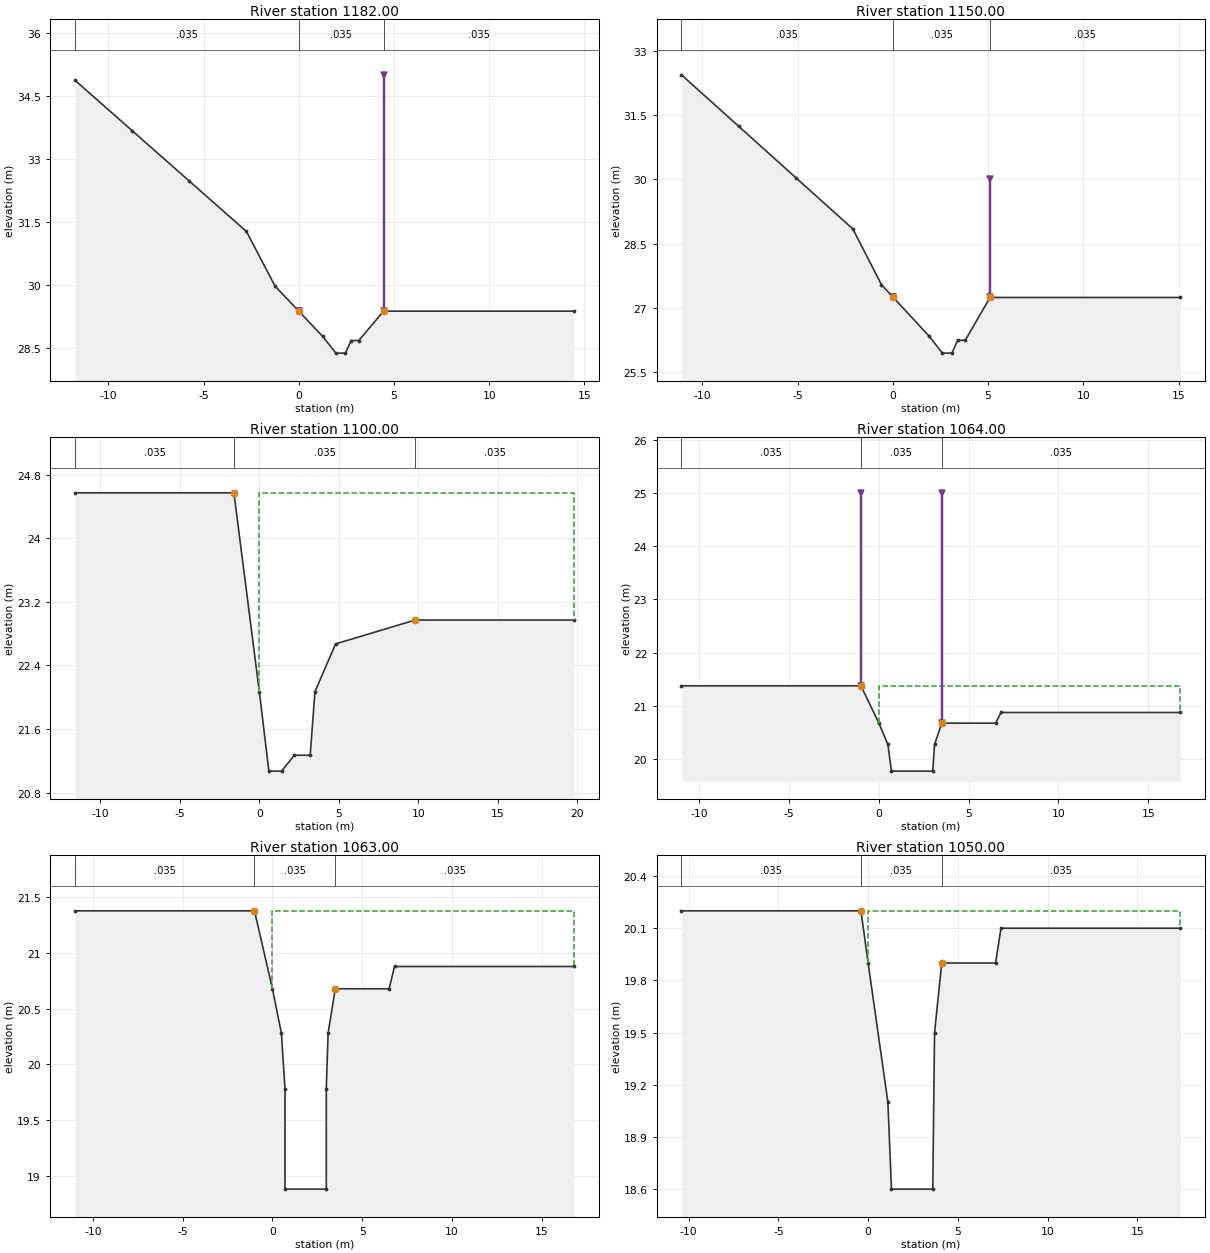
Type RM Length L Ch R = 1 ,1182.00 ,32,32,32
BEGIN DESCRIPTION:
23.032
END DESCRIPTION:
#Sta/Elev= 13
  -11.75   34.87   -8.75   33.67   -5.75   32.47   -2.75   31.27   -1.25   29.97
       0   29.37    1.25   28.77    1.95   28.37    2.45   28.37    2.75   28.67
    3.15   28.67    4.45   29.37   14.45   29.37
#Mann= 3 , 0 , 0
  -11.75    .035       0       0    .035       0    4.45    .035       0
Levee=-1,0,29.37,-1,4.45,35,,
#XS Ineff= 2 , 0
               0   29.37    4.45           29.37
Permanent Ineff=
       F       F
Bank Sta=0,4.45
XS Rating Curve= 0
Exp/Cntr=.3,.1

Type RM Length L Ch R = 1 ,1150.00 ,50,50,50
BEGIN DESCRIPTION:
23
END DESCRIPTION:
#Sta/Elev= 13
   -11.1   32.44    -8.1   31.24    -5.1   30.04    -2.1   28.84     -.6   27.54
       0   27.25     1.9   26.34     2.6   25.94     3.1   25.94     3.4   26.24
     3.8   26.24     5.1   27.24    15.1   27.24
#Mann= 3 , 0 , 0
   -11.1    .035       0       0    .035       0     5.1    .035       0
Levee=-1,0,27.25,-1,5.1,30,,
#XS Ineff= 2 , 0
               0   27.25     5.1           27.24
Permanent Ineff=
       F       F
Bank Sta=0,5.1
XS Rating Curve= 0
Exp/Cntr=.3,.1

Type RM Length L Ch R = 1 ,1100.00 ,36,36,36
BEGIN DESCRIPTION:
22
END DESCRIPTION:
#Sta/Elev= 11
   -11.6   24.57    -1.6   24.57       0   22.07      .6   21.07     1.4   21.07
     2.2   21.27     3.2   21.27     3.5   22.07     4.8   22.67     9.8   22.97
    19.8   22.97
#Mann= 3 , 0 , 0
   -11.6    .035       0    -1.6    .035       0     9.8    .035       0
#XS Ineff= 2 , 0
       0    -1.6   24.57     9.8       0   22.97
Permanent Ineff=
       F       F
Bank Sta=-1.6,9.8
XS Rating Curve= 0
Exp/Cntr=.3,.1

Type RM Length L Ch R = 1 ,1064.00 ,1,1,1
BEGIN DESCRIPTION:
21.014
END DESCRIPTION:
#Sta/Elev= 11
     -11   21.38      -1   21.38       0   20.68      .5   20.28      .7   19.78
       3   19.78     3.1   20.28     3.5   20.68     6.5   20.68     6.8   20.88
    16.8   20.88
#Mann= 3 , 0 , 0
     -11    .035       0      -1    .035       0     3.5    .035       0
Levee=-1,-1,25,-1,3.5,25,,
#XS Ineff= 2 , 0
       0      -1   21.38     3.5       0   20.68
Permanent Ineff=
       F       F
Bank Sta=-1,3.5
XS Rating Curve= 0
Exp/Cntr=.3,.1

Type RM Length L Ch R = 1 ,1063.00 ,13,13,13
BEGIN DESCRIPTION:
21.013
END DESCRIPTION:
#Sta/Elev= 13
     -11   21.38      -1   21.38       0   20.68      .5   20.28      .7   19.78
      .7   18.88       3   18.88       3   19.78     3.1   20.28     3.5   20.68
     6.5   20.68     6.8   20.88    16.8   20.88
#Mann= 3 , 0 , 0
     -11    .035       0      -1    .035       0     3.5    .035       0
#XS Ineff= 2 , 0
       0      -1   21.38     3.5       0   20.68
Permanent Ineff=
       F       F
Bank Sta=-1,3.5
XS Rating Curve= 0
Exp/Cntr=.3,.1

Type RM Length L Ch R = 1 ,1050.00 ,18,18,18
BEGIN DESCRIPTION:
21
END DESCRIPTION:
#Sta/Elev= 11
   -10.4    20.2     -.4    20.2       0    19.9     1.1    19.1     1.3    18.6
     3.6    18.6     3.7    19.5     4.1    19.9     7.1    19.9     7.4    20.1
    17.4    20.1
#Mann= 3 , 0 , 0
   -10.4    .035       0     -.4    .035       0     4.1    .035       0
#XS Ineff= 2 , 0
       0     -.4    20.2     4.1       0    19.9
Permanent Ineff=
       F       F
Bank Sta=-.4,4.1
XS Rating Curve= 0
Exp/Cntr=.3,.1

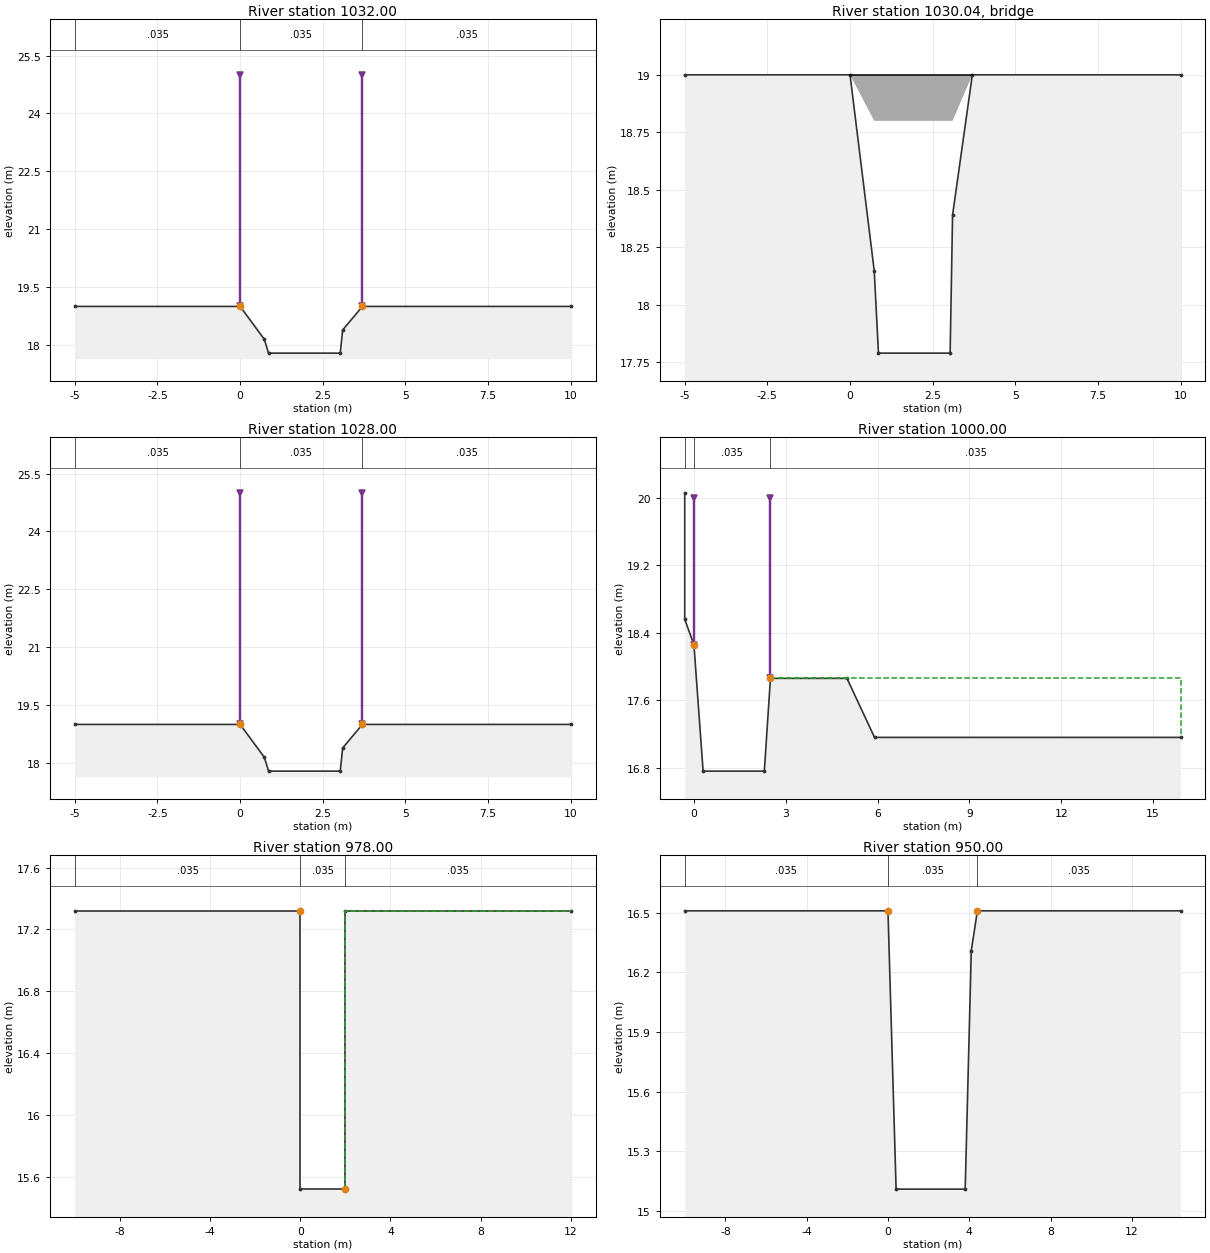
Type RM Length L Ch R = 1 ,1032.00 ,4,4,4
BEGIN DESCRIPTION:
20.032
END DESCRIPTION:
#Sta/Elev= 8
      -5      19       0      19    .732  18.148     .86   17.79   3.028   17.79
   3.102  18.391     3.7      19      10      19
#Mann= 3 , 0 , 0
      -5    .035       0       0    .035       0     3.7    .035       0
Levee=-1,0,25,-1,3.7,25,,
#XS Ineff= 2 , 0
       0       0      19     3.7       0      19
Permanent Ineff=
       F       F
Bank Sta=0,3.7
XS Rating Curve= 0
Exp/Cntr=.3,.1

Type RM Length L Ch R = 3 ,1030.04 ,,,
BEGIN DESCRIPTION:
20.030
END DESCRIPTION:
Bridge Culvert--1,0,-1,-1, 0
Deck Dist Width WeirC Skew NumUp NumDn MinLoCord MaxHiCord MaxSubmerge Is_Ogee
.01,3.9,1.44,0, 2, 2, , , .95, 0, 0,0,,
       0     3.7
      19      19
    18.8    18.8
       0     3.7
      19      19
    18.8    18.8
BR Coef=-1 , 1 , 0 ,, 0 ,,,.8,-1,1.2,0,
WSPro=,,,, 1 ,,,, 0 ,,,, 0 ,,,,-1 ,-1 ,-1 , 0 , 0 , 0 , 0 , 0
BC Design=,, 0 ,, 0 ,,,,,,

Type RM Length L Ch R = 1 ,1028.00 ,28,28,28
BEGIN DESCRIPTION:
20.028
END DESCRIPTION:
#Sta/Elev= 8
      -5      19       0      19    .732  18.148     .86   17.79   3.028   17.79
   3.102  18.391     3.7      19      10      19
#Mann= 3 , 0 , 0
      -5    .035       0       0    .035       0     3.7    .035       0
Levee=-1,0,25,-1,3.7,25,,
#XS Ineff= 2 , 0
       0       0      19     3.7       0      19
Permanent Ineff=
       F       F
Bank Sta=0,3.7
XS Rating Curve= 0
Exp/Cntr=.3,.1

Type RM Length L Ch R = 1 ,1000.00 ,22,22,22
BEGIN DESCRIPTION:
20
END DESCRIPTION:
#Sta/Elev= 9
     -.3   20.06     -.3   18.56       0   18.26      .3   16.76     2.3   16.76
     2.5   17.86       5   17.86     5.9   17.16    15.9   17.16
#Mann= 3 , 0 , 0
     -.3    .035       0       0    .035       0     2.5    .035       0
Levee=-1,0,20,-1,2.5,20,,
#XS Ineff= 2 , 0
               0   18.26     2.5           17.86
Permanent Ineff=
       F       F
Bank Sta=0,2.5
XS Rating Curve= 0
Exp/Cntr=.3,.1

Type RM Length L Ch R = 1 ,978.00  ,28,28,28
BEGIN DESCRIPTION:
19.028
END DESCRIPTION:
#Sta/Elev= 6
     -10   17.32       0   17.32       0   15.52       2   15.52       2   17.32
      12   17.32
#Mann= 3 , 0 , 0
     -10    .035       0       0    .035       0       2    .035       0
#XS Ineff= 2 , 0
               0   17.32       2           17.32
Permanent Ineff=
       F       F
Bank Sta=0,2
XS Rating Curve= 0
Exp/Cntr=.3,.1

Type RM Length L Ch R = 1 ,950.00  ,30,30,30
BEGIN DESCRIPTION:
19
END DESCRIPTION:
#Sta/Elev= 7
     -10   16.51       0   16.51      .4   15.11     3.8   15.11     4.1   16.31
     4.4   16.51    14.4   16.51
#Mann= 3 , 0 , 0
     -10    .035       0       0    .035       0     4.4    .035       0
#XS Ineff= 2 , 0
               0   16.51     4.4           16.51
Permanent Ineff=
       F       F
Bank Sta=0,4.4
XS Rating Curve= 0
Exp/Cntr=.3,.1

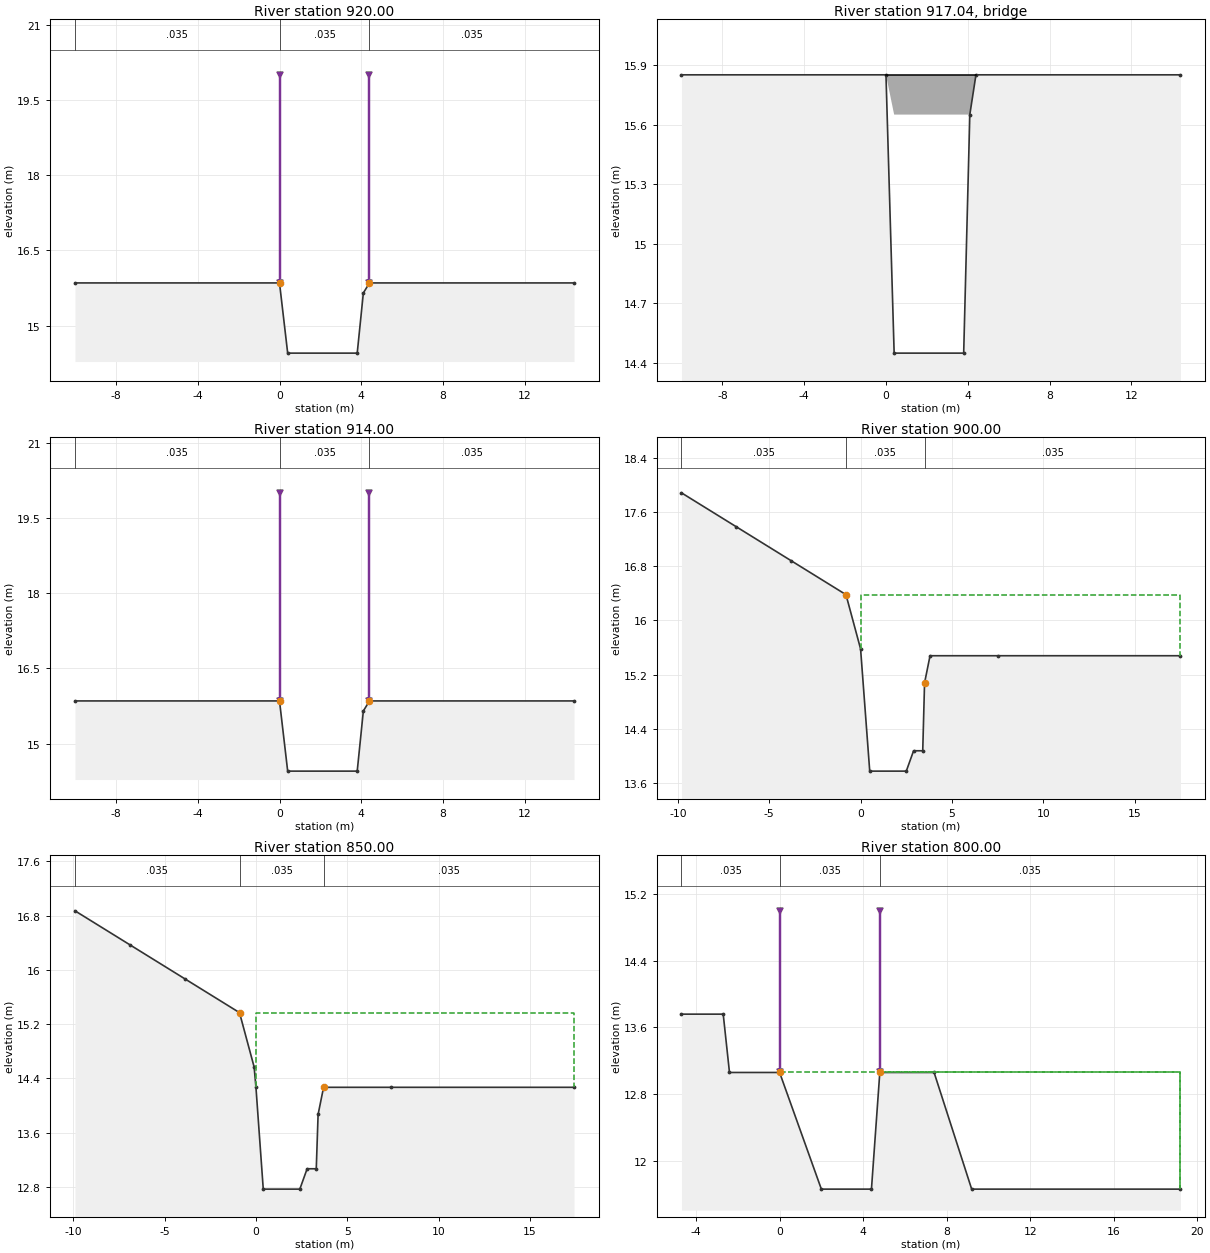
Type RM Length L Ch R = 1 ,920.00  ,6,6,6
BEGIN DESCRIPTION:
18.020
END DESCRIPTION:
#Sta/Elev= 7
     -10   15.85       0   15.85      .4   14.45     3.8   14.45     4.1   15.65
     4.4   15.85    14.4   15.85
#Mann= 3 , 0 , 0
     -10    .035       0       0    .035       0     4.4    .035       0
Levee=-1,0,20,-1,4.4,20,,
#XS Ineff= 2 , 0
       0       0   15.85     4.4       0   15.85
Permanent Ineff=
       F       F
Bank Sta=0,4.4
XS Rating Curve= 0
Exp/Cntr=.3,.1

Type RM Length L Ch R = 3 ,917.04  ,,,
BEGIN DESCRIPTION:
18.017
END DESCRIPTION:
Bridge Culvert--1,0,-1,-1, 0
Deck Dist Width WeirC Skew NumUp NumDn MinLoCord MaxHiCord MaxSubmerge Is_Ogee
.01,5.9,1.44,0, 2, 2, , , .95, 0, 0,0,,
       0     4.4
   15.85   15.85
   15.65   15.65
       0     4.4
   15.85   15.85
   15.65   15.65
BR Coef=-1 , 1 , 0 ,, 0 ,,,.8,-1,1.2,0,
WSPro=,,,, 1 ,,,, 0 ,,,, 0 ,,,,-1 ,-1 ,-1 , 0 , 0 , 0 , 0 , 0
BC Design=,, 0 ,, 0 ,,,,,,

Type RM Length L Ch R = 1 ,914.00  ,14,14,14
BEGIN DESCRIPTION:
18.014
END DESCRIPTION:
#Sta/Elev= 7
     -10   15.85       0   15.85      .4   14.45     3.8   14.45     4.1   15.65
     4.4   15.85    14.4   15.85
#Mann= 3 , 0 , 0
     -10    .035       0       0    .035       0     4.4    .035       0
Levee=-1,0,20,-1,4.4,20,,
#XS Ineff= 2 , 0
       0       0   15.85     4.4       0   15.85
Permanent Ineff=
       F       F
Bank Sta=0,4.4
XS Rating Curve= 0
Exp/Cntr=.3,.1

Type RM Length L Ch R = 1 ,900.00  ,50,50,50
BEGIN DESCRIPTION:
18
END DESCRIPTION:
#Sta/Elev= 13
    -9.8   17.88    -6.8   17.38    -3.8   16.88     -.8   16.38       0   15.58
      .5   13.78     2.5   13.78     2.9   14.08     3.4   14.08     3.5   15.08
     3.8   15.48     7.5   15.48    17.5   15.48
#Mann= 3 , 0 , 0
    -9.8    .035       0     -.8    .035       0     3.5    .035       0
#XS Ineff= 2 , 0
       0     -.8   16.38     3.5       0   15.08
Permanent Ineff=
       F       F
Bank Sta=-.8,3.5
XS Rating Curve= 0
Exp/Cntr=.3,.1

Type RM Length L Ch R = 1 ,850.00  ,50,50,50
BEGIN DESCRIPTION:
17
END DESCRIPTION:
#Sta/Elev= 14
    -9.9   16.87    -6.9   16.37    -3.9   15.87     -.9   15.37     -.1   14.57
       0   14.27      .4   12.77     2.4   12.77     2.8   13.07     3.3   13.07
     3.4   13.87     3.7   14.27     7.4   14.27    17.4   14.27
#Mann= 3 , 0 , 0
    -9.9    .035       0     -.9    .035       0     3.7    .035       0
#XS Ineff= 2 , 0
       0     -.9   15.37     3.7       0   14.27
Permanent Ineff=
       F       F
Bank Sta=-.9,3.7
XS Rating Curve= 0
Exp/Cntr=.3,.1

Type RM Length L Ch R = 1 ,800.00  ,3,3,3
BEGIN DESCRIPTION:
16
END DESCRIPTION:
#Sta/Elev= 10
    -4.7   13.76    -2.7   13.76    -2.4   13.06       0   13.06       2   11.66
     4.4   11.66     4.8   13.06     7.4   13.06     9.2   11.66    19.2   11.66
#Mann= 3 , 0 , 0
    -4.7    .035       0       0    .035       0     4.8    .035       0
Levee=-1,0,15,-1,4.8,15,,
#XS Ineff= 2 , 0
       0       0   13.06     4.8       0   13.06
Permanent Ineff=
       F       F
Bank Sta=0,4.8
XS Rating Curve= 0
Exp/Cntr=.3,.1

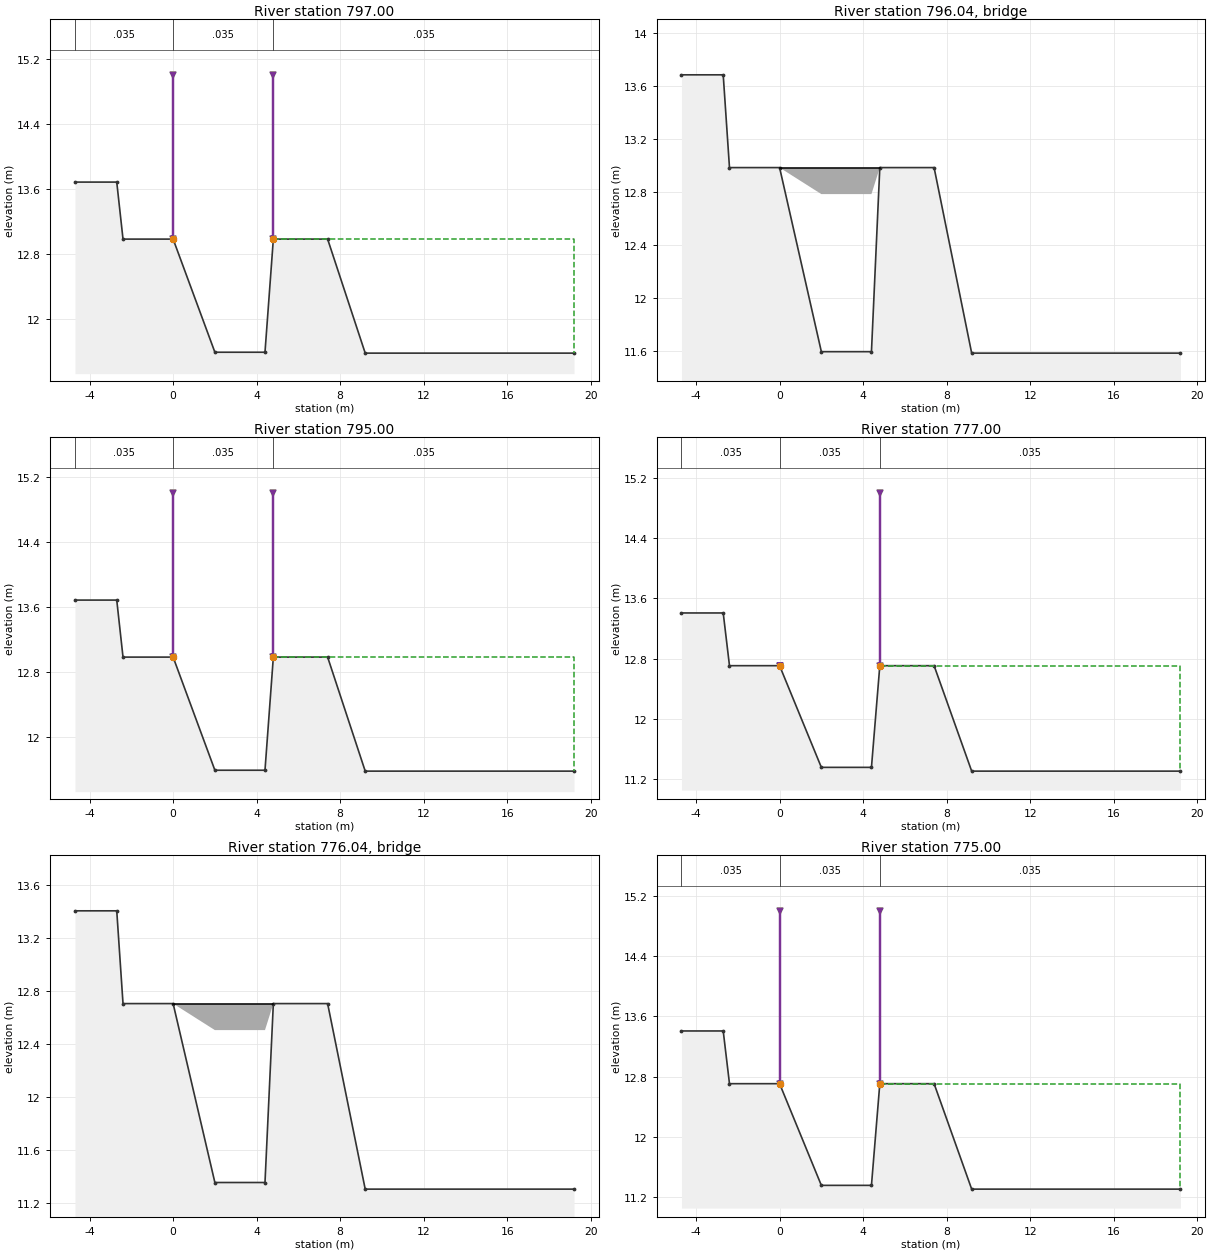
Type RM Length L Ch R = 1 ,797.00  ,2,2,2
BEGIN DESCRIPTION:
15.047
END DESCRIPTION:
#Sta/Elev= 10
    -4.7  13.683    -2.7  13.683    -2.4  12.983       0  12.983       2  11.594
     4.4  11.594     4.8  12.983     7.4  12.983     9.2  11.583    19.2  11.583
#Mann= 3 , 0 , 0
    -4.7    .035       0       0    .035       0     4.8    .035       0
Levee=-1,0,15,-1,4.8,15,,
#XS Ineff= 2 , 0
               012.98283     4.8        12.98283
Permanent Ineff=
       F       F
Bank Sta=0,4.8
XS Rating Curve= 0
Exp/Cntr=.3,.1

Type RM Length L Ch R = 3 ,796.04  ,,,
BEGIN DESCRIPTION:
15.046
END DESCRIPTION:
Bridge Culvert--1,0,-1,-1, 0
Deck Dist Width WeirC Skew NumUp NumDn MinLoCord MaxHiCord MaxSubmerge Is_Ogee
.01,1.9,1.44,0, 2, 2, , , .95, 0, 0,0,,
       0     4.8
  12.983  12.983
  12.783  12.783
       0     4.8
  12.983  12.983
  12.783  12.783
BR Coef=-1 , 1 , 0 ,, 0 ,,,.8,-1,1.2,0,
WSPro=,,,, 1 ,,,, 0 ,,,, 0 ,,,,-1 ,-1 ,-1 , 0 , 0 , 0 , 0 , 0
BC Design=,, 0 ,, 0 ,,,,,,

Type RM Length L Ch R = 1 ,795.00  ,18,18,18
BEGIN DESCRIPTION:
15.045
END DESCRIPTION:
#Sta/Elev= 10
    -4.7  13.683    -2.7  13.683    -2.4  12.983       0  12.983       2  11.594
     4.4  11.594     4.8  12.983     7.4  12.983     9.2  11.583    19.2  11.583
#Mann= 3 , 0 , 0
    -4.7    .035       0       0    .035       0     4.8    .035       0
Levee=-1,0,15,-1,4.8,15,,
#XS Ineff= 2 , 0
               012.98283     4.8        12.98283
Permanent Ineff=
       F       F
Bank Sta=0,4.8
XS Rating Curve= 0
Exp/Cntr=.3,.1

Type RM Length L Ch R = 1 ,777.00  ,2,2,2
BEGIN DESCRIPTION:
15.027
END DESCRIPTION:
#Sta/Elev= 10
    -4.7  13.405    -2.7  13.405    -2.4  12.705       0  12.705       2  11.355
     4.4  11.355     4.8  12.705     7.4  12.705     9.2  11.305    19.2  11.305
#Mann= 3 , 0 , 0
    -4.7    .035       0       0    .035       0     4.8    .035       0
Levee=-1,0,12.705,-1,4.8,15,,
#XS Ineff= 2 , 0
               0  12.705     4.8          12.705
Permanent Ineff=
       F       F
Bank Sta=0,4.8
XS Rating Curve= 0
Exp/Cntr=.3,.1

Type RM Length L Ch R = 3 ,776.04  ,,,
BEGIN DESCRIPTION:
15.026
END DESCRIPTION:
Bridge Culvert--1,0,-1,-1, 0
Deck Dist Width WeirC Skew NumUp NumDn MinLoCord MaxHiCord MaxSubmerge Is_Ogee
.01,1.9,1.44,0, 2, 2, , , .95, 0, 0,0,,
       0     4.8
  12.705  12.705
  12.505  12.505
       0     4.8
  12.705  12.705
  12.505  12.505
BR Coef=-1 , 1 , 0 ,, 0 ,,,.8,-1,1.2,0,
WSPro=,,,, 1 ,,,, 0 ,,,, 0 ,,,,-1 ,-1 ,-1 , 0 , 0 , 0 , 0 , 0
BC Design=,, 0 ,, 0 ,,,,,,

Type RM Length L Ch R = 1 ,775.00  ,25,25,25
BEGIN DESCRIPTION:
15.025
END DESCRIPTION:
#Sta/Elev= 10
    -4.7  13.405    -2.7  13.405    -2.4  12.705       0  12.705       2  11.355
     4.4  11.355     4.8  12.705     7.4  12.705     9.2  11.305    19.2  11.305
#Mann= 3 , 0 , 0
    -4.7    .035       0       0    .035       0     4.8    .035       0
Levee=-1,0,15,-1,4.8,15,,
#XS Ineff= 2 , 0
               0  12.705     4.8          12.705
Permanent Ineff=
       F       F
Bank Sta=0,4.8
XS Rating Curve= 0
Exp/Cntr=.3,.1

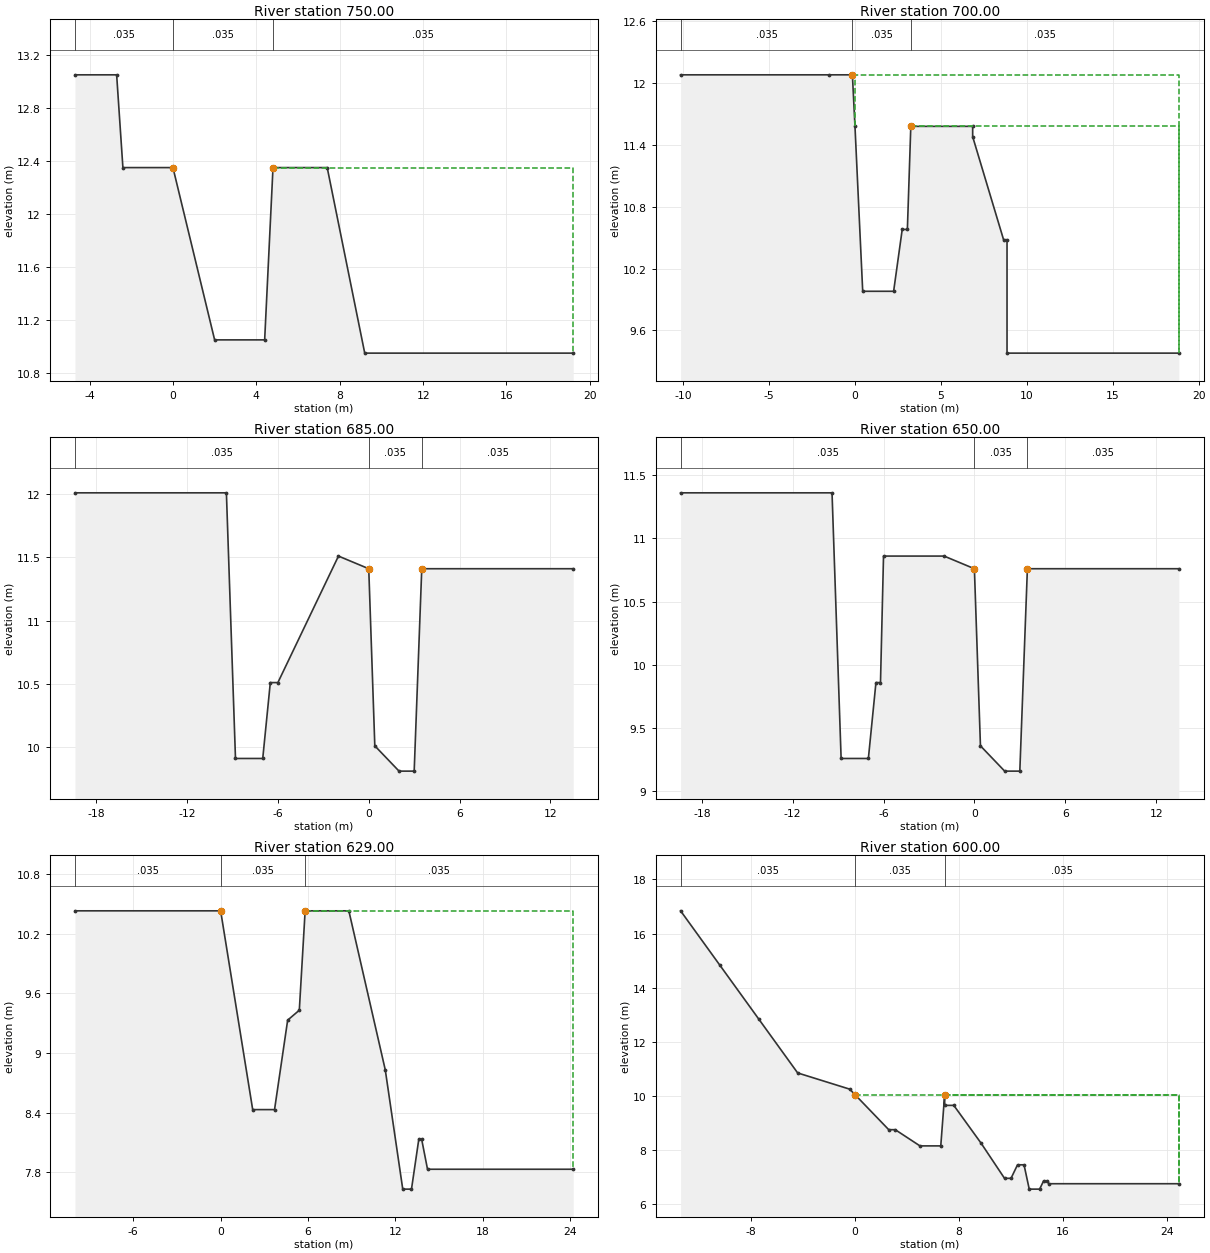
Type RM Length L Ch R = 1 ,750.00  ,50,50,50
BEGIN DESCRIPTION:
15
END DESCRIPTION:
#Sta/Elev= 10
    -4.7   13.05    -2.7   13.05    -2.4   12.35       0   12.35       2   11.05
     4.4   11.05     4.8   12.35     7.4   12.35     9.2   10.95    19.2   10.95
#Mann= 3 , 0 , 0
    -4.7    .035       0       0    .035       0     4.8    .035       0
#XS Ineff= 2 , 0
               0   12.35     4.8           12.35
Permanent Ineff=
       F       F
Bank Sta=0,4.8
XS Rating Curve= 0
Exp/Cntr=.3,.1

Type RM Length L Ch R = 1 ,700.00  ,15,15,15
BEGIN DESCRIPTION:
14
END DESCRIPTION:
#Sta/Elev= 15
  -10.15   12.08    -1.5   12.08    -.15   12.08       0   11.58     .45    9.98
    2.25    9.98    2.75   10.58    3.05   10.58    3.25   11.58    6.85   11.58
    6.85   11.48    8.65   10.48    8.85   10.48    8.85    9.38   18.85    9.38
#Mann= 3 , 0 , 0
  -10.15    .035       0    -.15    .035       0    3.25    .035       0
#XS Ineff= 2 , 0
       0    -.15   12.08    3.25       0   11.58
Permanent Ineff=
       F       F
Bank Sta=-.15,3.25
XS Rating Curve= 0
Exp/Cntr=.3,.1

Type RM Length L Ch R = 1 ,685.00  ,35,35,35
BEGIN DESCRIPTION:
13.035
END DESCRIPTION:
#Sta/Elev= 13
   -19.4   12.01    -9.4   12.01    -8.8    9.91      -7    9.91    -6.5   10.51
      -6   10.51      -2   11.51       0   11.41      .4   10.01       2    9.81
       3    9.81     3.5   11.41    13.5   11.41
#Mann= 3 , 0 , 0
   -19.4    .035       0       0    .035       0     3.5    .035       0
#XS Ineff= 2 , 0
               0   11.41     3.5           11.41
Permanent Ineff=
       F       F
Bank Sta=0,3.5
XS Rating Curve= 0
Exp/Cntr=.3,.1

Type RM Length L Ch R = 1 ,650.00  ,21,21,21
BEGIN DESCRIPTION:
13
END DESCRIPTION:
#Sta/Elev= 14
   -19.4   11.36    -9.4   11.36    -8.8    9.26      -7    9.26    -6.5    9.86
    -6.2    9.86      -6   10.86      -2   10.86       0   10.76      .4    9.36
       2    9.16       3    9.16     3.5   10.76    13.5   10.76
#Mann= 3 , 0 , 0
   -19.4    .035       0       0    .035       0     3.5    .035       0
#XS Ineff= 2 , 0
               0   10.76     3.5           10.76
Permanent Ineff=
       F       F
Bank Sta=0,3.5
XS Rating Curve= 0
Exp/Cntr=.3,.1

Type RM Length L Ch R = 1 ,629.00  ,29,29,29
BEGIN DESCRIPTION:
12.029
END DESCRIPTION:
#Sta/Elev= 15
     -10   10.43       0   10.43     2.2    8.43     3.7    8.43     4.6    9.33
     5.4    9.43     5.8   10.43     8.8   10.43    11.3    8.83    12.5    7.63
    13.1    7.63    13.6    8.13    13.8    8.13    14.2    7.83    24.2    7.83
#Mann= 3 , 0 , 0
     -10    .035       0       0    .035       0     5.8    .035       0
#XS Ineff= 2 , 0
               0   10.43     5.8           10.43
Permanent Ineff=
       F       F
Bank Sta=0,5.8
XS Rating Curve= 0
Exp/Cntr=.3,.1

Type RM Length L Ch R = 1 ,600.00  ,50,50,50
BEGIN DESCRIPTION:
12
END DESCRIPTION:
#Sta/Elev= 24
   -13.4   16.84   -10.4   14.84    -7.4   12.84    -4.4   10.84     -.4   10.24
       0   10.04     2.6    8.74     3.1    8.74       5    8.14     6.6    8.14
     6.9   10.04     6.9    9.64     7.6    9.64     9.7    8.24    11.5    6.94
      12    6.94    12.5    7.44      13    7.44    13.4    6.54    14.2    6.54
    14.5    6.84    14.8    6.84    14.9    6.74    24.9    6.74
#Mann= 3 , 0 , 0
   -13.4    .035       0       0    .035       0     6.9    .035       0
#XS Ineff= 2 , 0
       0       0   10.04     6.9       0   10.04
Permanent Ineff=
       F       F
Bank Sta=0,6.9
XS Rating Curve= 0
Exp/Cntr=.3,.1

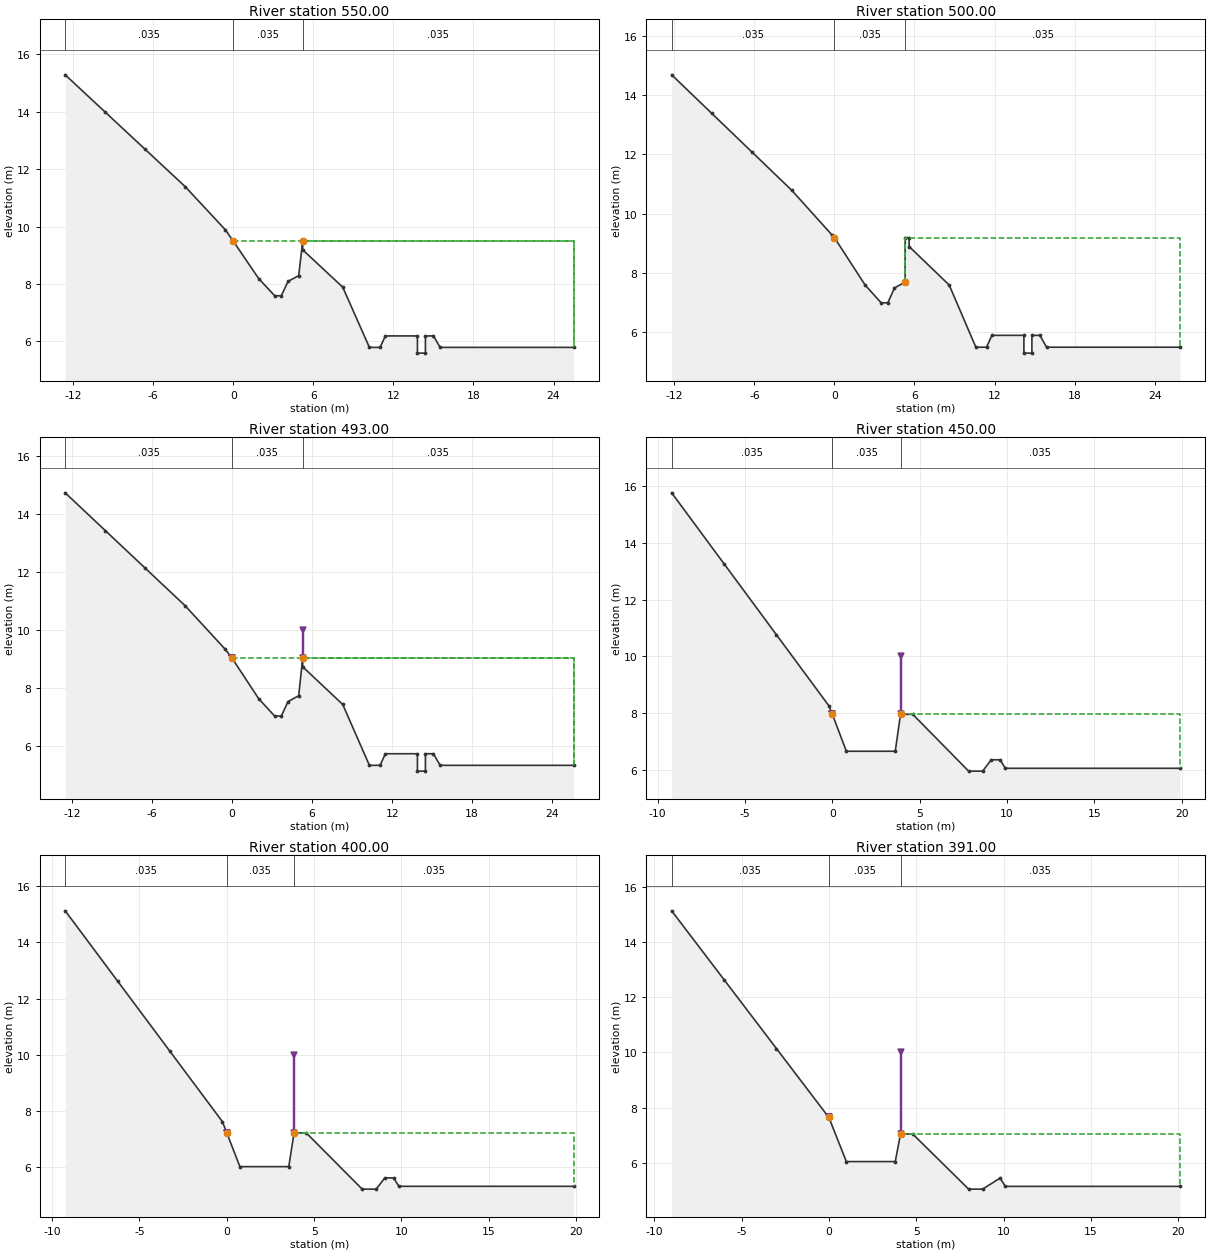
Type RM Length L Ch R = 1 ,550.00  ,50,50,50
BEGIN DESCRIPTION:
11
END DESCRIPTION:
#Sta/Elev= 24
   -12.6   15.29    -9.6   13.99    -6.6   12.69    -3.6   11.39     -.6    9.89
       0    9.49     1.9    8.19     3.1    7.59     3.6    7.59     4.1    8.09
     4.9    8.29     5.2    9.49     5.2    9.19     8.2    7.89    10.2    5.79
      11    5.79    11.4    6.19    13.8    6.19    13.8    5.59    14.4    5.59
    14.4    6.19      15    6.19    15.5    5.79    25.5    5.79
#Mann= 3 , 0 , 0
   -12.6    .035       0       0    .035       0     5.2    .035       0
#XS Ineff= 2 , 0
       0       0    9.49     5.2       0    9.49
Permanent Ineff=
       F       F
Bank Sta=0,5.2
XS Rating Curve= 0
Exp/Cntr=.3,.1

Type RM Length L Ch R = 1 ,500.00  ,7,7,7
BEGIN DESCRIPTION:
10
END DESCRIPTION:
#Sta/Elev= 25
   -12.2   14.69    -9.2   13.39    -6.2   12.09    -3.2   10.79     -.2    9.29
       0    9.19     2.3    7.59     3.5    6.99       4    6.99     4.5    7.49
     5.3    7.69     5.3    9.19     5.6    9.19     5.6    8.89     8.6    7.59
    10.6    5.49    11.4    5.49    11.8    5.89    14.2    5.89    14.2    5.29
    14.8    5.29    14.8    5.89    15.4    5.89    15.9    5.49    25.9    5.49
#Mann= 3 , 0 , 0
   -12.2    .035       0       0    .035       0     5.3    .035       0
#XS Ineff= 2 , 0
               0    9.19     5.3            9.19
Permanent Ineff=
       F       F
Bank Sta=0,5.3
XS Rating Curve= 0
Exp/Cntr=.3,.1

Type RM Length L Ch R = 1 ,493.00  ,43,43,43
BEGIN DESCRIPTION:
9.043
END DESCRIPTION:
#Sta/Elev= 24
   -12.5   14.72    -9.5   13.42    -6.5   12.12    -3.5   10.82     -.5    9.32
       0    9.02       2    7.62     3.2    7.02     3.7    7.02     4.2    7.52
       5    7.72     5.3    9.02     5.3    8.72     8.3    7.42    10.3    5.32
    11.1    5.32    11.5    5.72    13.9    5.72    13.9    5.12    14.5    5.12
    14.5    5.72    15.1    5.72    15.6    5.32    25.6    5.32
#Mann= 3 , 0 , 0
   -12.5    .035       0       0    .035       0     5.3    .035       0
Levee=-1,0,9.02,-1,5.3,10,,
#XS Ineff= 2 , 0
       0       0    9.02     5.3       0    9.02
Permanent Ineff=
       F       F
Bank Sta=0,5.3
XS Rating Curve= 0
Exp/Cntr=.3,.1

Type RM Length L Ch R = 1 ,450.00  ,50,50,50
BEGIN DESCRIPTION:
9
END DESCRIPTION:
#Sta/Elev= 15
    -9.2   15.76    -6.2   13.26    -3.2   10.76     -.2    8.26       0    7.96
      .8    6.66     3.6    6.66     3.9    7.96     4.6    7.96     7.8    5.96
     8.6    5.96     9.1    6.36     9.6    6.36     9.9    6.06    19.9    6.06
#Mann= 3 , 0 , 0
    -9.2    .035       0       0    .035       0     3.9    .035       0
Levee=-1,0,7.96,-1,3.9,10,,
#XS Ineff= 2 , 0
               0    7.96     3.9            7.96
Permanent Ineff=
       F       F
Bank Sta=0,3.9
XS Rating Curve= 0
Exp/Cntr=.3,.1

Type RM Length L Ch R = 1 ,400.00  ,9,9,9
BEGIN DESCRIPTION:
8
END DESCRIPTION:
#Sta/Elev= 15
   -9.25   15.12   -6.25   12.62   -3.25   10.12    -.25    7.62       0    7.22
     .75    6.02    3.55    6.02    3.85    7.22    4.55    7.22    7.75    5.22
    8.55    5.22    9.05    5.62    9.55    5.62    9.85    5.32   19.85    5.32
#Mann= 3 , 0 , 0
   -9.25    .035       0       0    .035       0    3.85    .035       0
Levee=-1,0,7.22,-1,3.85,10,,
#XS Ineff= 2 , 0
               0    7.22    3.85            7.22
Permanent Ineff=
       F       F
Bank Sta=0,3.85
XS Rating Curve= 0
Exp/Cntr=.3,.1

Type RM Length L Ch R = 1 ,391.00  ,41,41,41
BEGIN DESCRIPTION:
7.041
END DESCRIPTION:
#Sta/Elev= 13
      -9   15.14      -6   12.64      -3   10.14       0    7.64       1    6.04
     3.8    6.04     4.1    7.04     4.8    7.04       8    5.04     8.8    5.04
     9.8    5.44    10.1    5.14    20.1    5.14
#Mann= 3 , 0 , 0
      -9    .035       0       0    .035       0     4.1    .035       0
Levee=-1,0,7.64,-1,4.1,10,,
#XS Ineff= 2 , 0
               0    7.64     4.1            7.04
Permanent Ineff=
       F       F
Bank Sta=0,4.1
XS Rating Curve= 0
Exp/Cntr=.3,.1

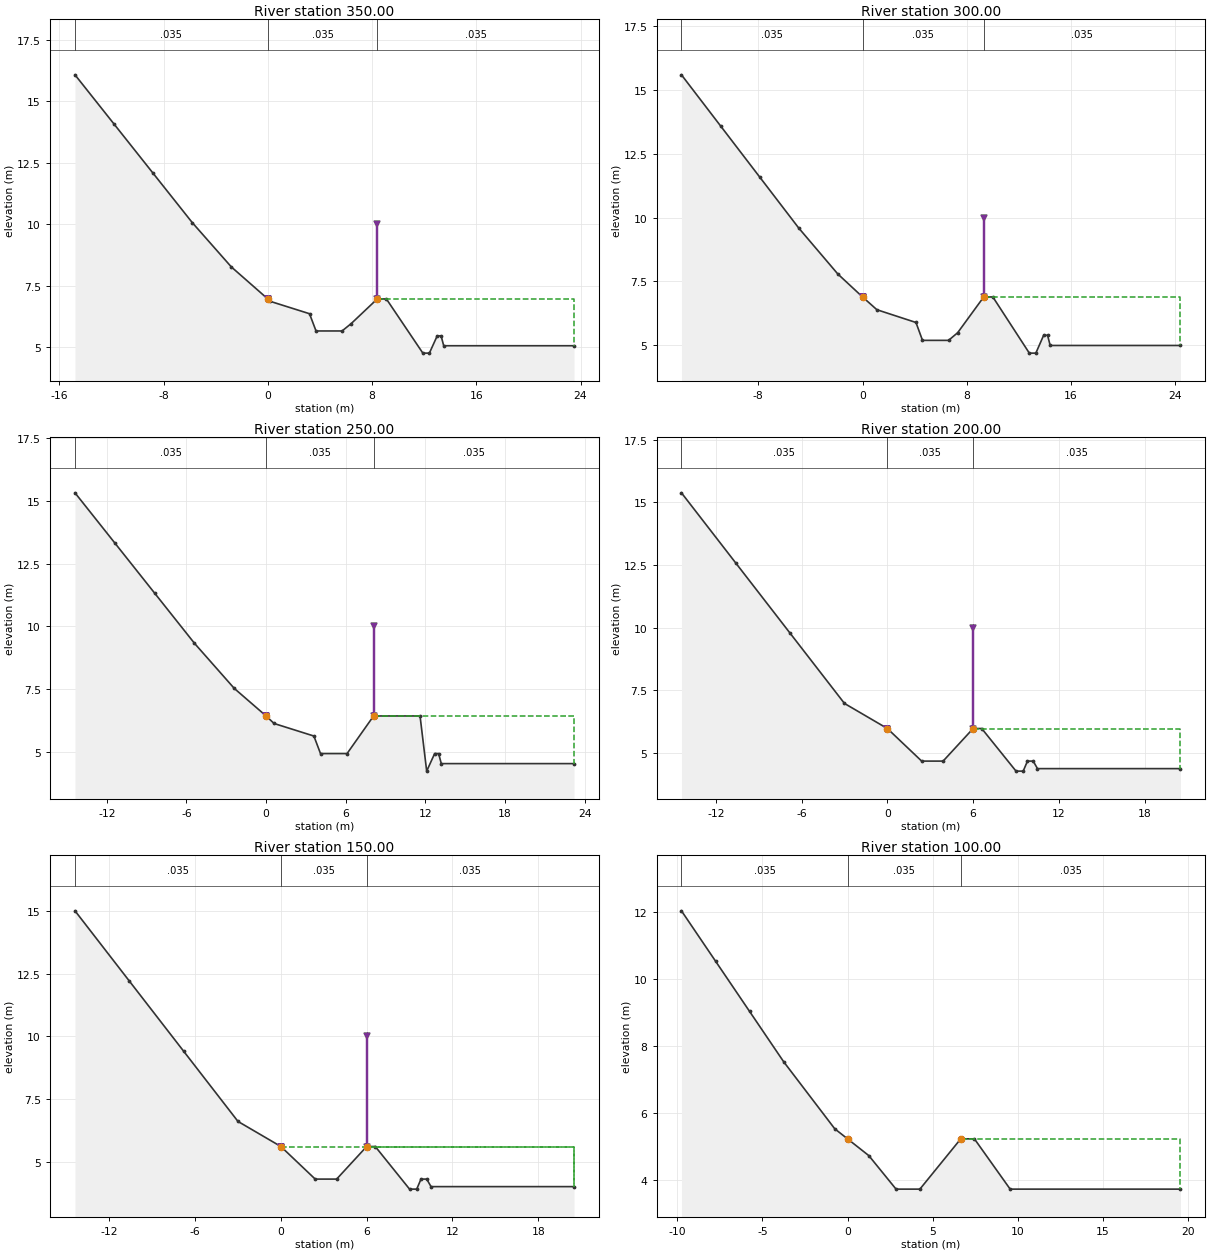
Type RM Length L Ch R = 1 ,350.00  ,50,50,50
BEGIN DESCRIPTION:
7
END DESCRIPTION:
#Sta/Elev= 19
   -14.8   16.07   -11.8   14.07    -8.8   12.07    -5.8   10.07    -2.8    8.27
       0    6.97      .2    6.87     3.2    6.37     3.7    5.67     5.7    5.67
     6.4    5.97     8.4    6.97     9.1    6.97    11.9    4.77    12.4    4.77
      13    5.47    13.3    5.47    13.5    5.07    23.5    5.07
#Mann= 3 , 0 , 0
   -14.8    .035       0       0    .035       0     8.4    .035       0
Levee=-1,0,6.97,-1,8.4,10,,
#XS Ineff= 2 , 0
               0    6.97     8.4            6.97
Permanent Ineff=
       F       F
Bank Sta=0,8.4
XS Rating Curve= 0
Exp/Cntr=.3,.1

Type RM Length L Ch R = 1 ,300.00  ,50,50,50
BEGIN DESCRIPTION:
6
END DESCRIPTION:
#Sta/Elev= 19
   -13.9   15.59   -10.9   13.59    -7.9   11.59    -4.9    9.59    -1.9    7.79
       0    6.89     1.1    6.39     4.1    5.89     4.6    5.19     6.6    5.19
     7.3    5.49     9.3    6.89      10    6.89    12.8    4.69    13.3    4.69
    13.9    5.39    14.2    5.39    14.4    4.99    24.4    4.99
#Mann= 3 , 0 , 0
   -13.9    .035       0       0    .035       0     9.3    .035       0
Levee=-1,0,6.89,-1,9.3,10,,
#XS Ineff= 2 , 0
               0    6.89     9.3            6.89
Permanent Ineff=
       F       F
Bank Sta=0,9.3
XS Rating Curve= 0
Exp/Cntr=.3,.1

Type RM Length L Ch R = 1 ,250.00  ,50,50,50
BEGIN DESCRIPTION:
5
END DESCRIPTION:
#Sta/Elev= 17
   -14.4   15.33   -11.4   13.33    -8.4   11.33    -5.4    9.33    -2.4    7.53
       0    6.43      .6    6.13     3.6    5.63     4.1    4.93     6.1    4.93
     8.1    6.43    11.6    6.43    12.1    4.23    12.7    4.93      13    4.93
    13.2    4.53    23.2    4.53
#Mann= 3 , 0 , 0
   -14.4    .035       0       0    .035       0     8.1    .035       0
Levee=-1,0,6.43,-1,8.1,10,,
#XS Ineff= 2 , 0
               0    6.43     8.1            6.43
Permanent Ineff=
       F       F
Bank Sta=0,8.1
XS Rating Curve= 0
Exp/Cntr=.3,.1

Type RM Length L Ch R = 1 ,200.00  ,50,50,50
BEGIN DESCRIPTION:
4
END DESCRIPTION:
#Sta/Elev= 15
   -14.4   15.38   -10.6   12.58    -6.8    9.78      -3    6.98       0    5.98
     2.4    4.68     3.9    4.68       6    5.98     6.6    5.98       9    4.28
     9.5    4.28     9.8    4.68    10.2    4.68    10.5    4.38    20.5    4.38
#Mann= 3 , 0 , 0
   -14.4    .035       0       0    .035       0       6    .035       0
Levee=-1,0,5.98,-1,6,10,,
#XS Ineff= 2 , 0
               0    5.98       6            5.98
Permanent Ineff=
       F       F
Bank Sta=0,6
XS Rating Curve= 0
Exp/Cntr=.3,.1

Type RM Length L Ch R = 1 ,150.00  ,50,50,50
BEGIN DESCRIPTION:
3
END DESCRIPTION:
#Sta/Elev= 15
   -14.4      15   -10.6    12.2    -6.8     9.4      -3     6.6       0     5.6
     2.4     4.3     3.9     4.3       6     5.6     6.6     5.6       9     3.9
     9.5     3.9     9.8     4.3    10.2     4.3    10.5       4    20.5       4
#Mann= 3 , 0 , 0
   -14.4    .035       0       0    .035       0       6    .035       0
Levee=-1,0,5.6,-1,6,10,,
#XS Ineff= 2 , 0
       0       0     5.6       6       0     5.6
Permanent Ineff=
       F       F
Bank Sta=0,6
XS Rating Curve= 0
Exp/Cntr=.3,.1

Type RM Length L Ch R = 1 ,100.00  ,50,50,50
BEGIN DESCRIPTION:
2
END DESCRIPTION:
#Sta/Elev= 13
   -9.75   12.03   -7.75   10.53   -5.75    9.03   -3.75    7.53    -.75    5.53
       0    5.23    1.25    4.73    2.85    3.73    4.25    3.73    6.65    5.23
    7.45    5.23    9.55    3.73   19.55    3.73
#Mann= 3 , 0 , 0
   -9.75    .035       0       0    .035       0    6.65    .035       0
#XS Ineff= 2 , 0
               0    5.23    6.65            5.23
Permanent Ineff=
       F       F
Bank Sta=0,6.65
XS Rating Curve= 0
Exp/Cntr=.3,.1