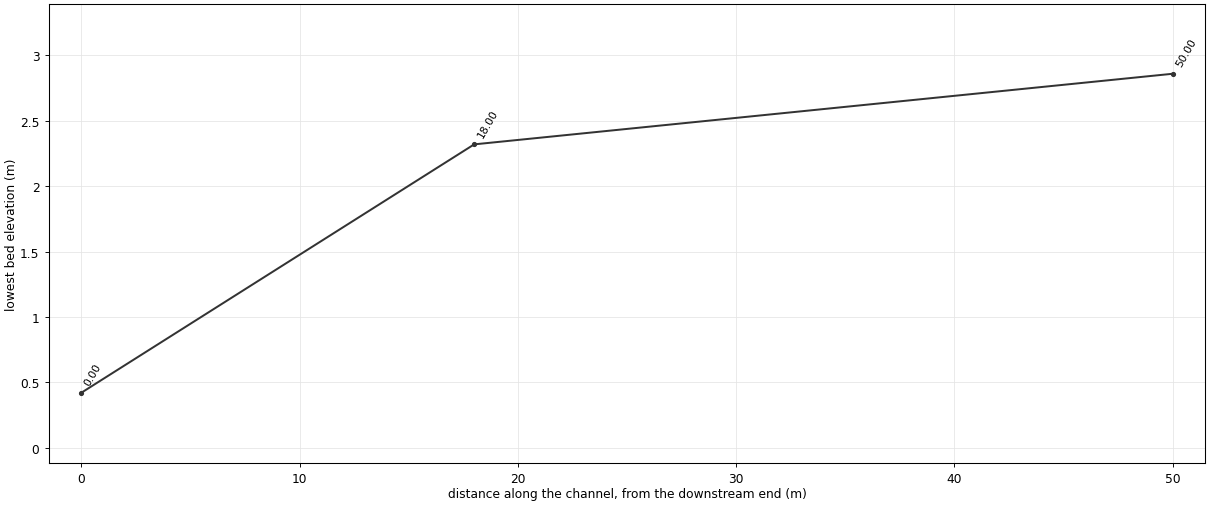
HEC-RAS study bnc.prj: beuknam-ch

--- bnc.g01 (geometry) --- (continued)

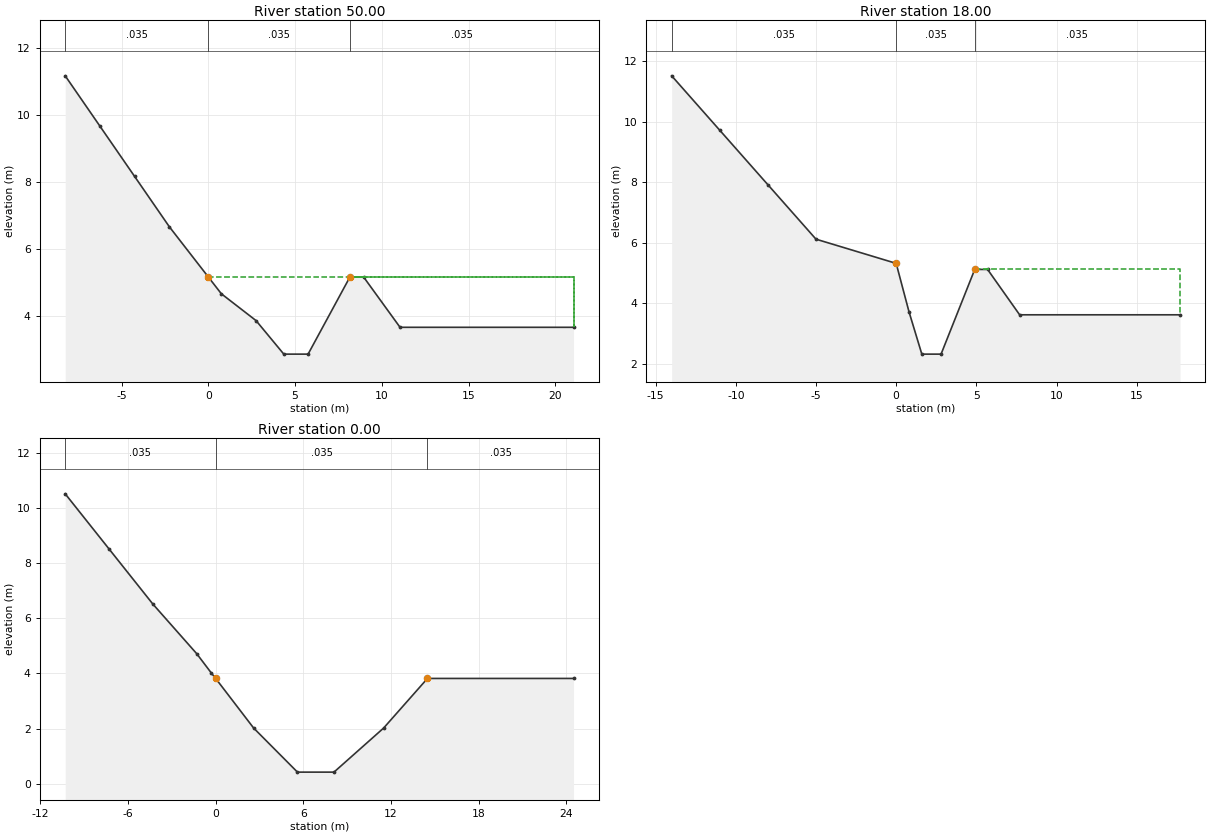
Type RM Length L Ch R = 1 ,50.00   ,32,32,32
BEGIN DESCRIPTION:
1
END DESCRIPTION:
#Sta/Elev= 13
   -8.25   11.16   -6.25    9.66   -4.25    8.16   -2.25    6.66       0    5.16
     .75    4.66    2.75    3.86    4.35    2.86    5.75    2.86    8.16    5.16
    8.95    5.16   11.05    3.66   21.05    3.66
#Mann= 3 , 0 , 0
   -8.25    .035       0       0    .035       0    8.16    .035       0
#XS Ineff= 2 , 0
       0       0    5.16    8.16       0    5.16
Permanent Ineff=
       F       F
Bank Sta=0,8.16
XS Rating Curve= 0
Exp/Cntr=.3,.1

Type RM Length L Ch R = 1 ,18.00   ,18,18,18
BEGIN DESCRIPTION:
0.018
END DESCRIPTION:
#Sta/Elev= 12
     -14   11.52     -11    9.72      -8    7.92      -5    6.12       0    5.32
      .8    3.72     1.6    2.32     2.8    2.32     4.9    5.12     5.7    5.12
     7.7    3.62    17.7    3.62
#Mann= 3 , 0 , 0
     -14    .035       0       0    .035       0     4.9    .035       0
#XS Ineff= 2 , 0
               0    5.32     4.9            5.12
Permanent Ineff=
       F       F
Bank Sta=0,4.9
XS Rating Curve= 0
Exp/Cntr=.3,.1

Type RM Length L Ch R = 1 ,0.00    ,0,0,0
BEGIN DESCRIPTION:
0
END DESCRIPTION:
#Sta/Elev= 12
   -10.3   10.52    -7.3    8.52    -4.3    6.52    -1.3    4.72     -.3    4.02
       0    3.82     2.6    2.02     5.6     .42     8.1     .42    11.5    2.02
    14.5    3.82    24.5    3.82
#Mann= 3 , 0 , 0
   -10.3    .035       0       0    .035       0    14.5    .035       0
#XS Ineff= 2 , 0
       0       0    3.82    14.5       0    3.82
Permanent Ineff=
       F       F
Bank Sta=0,14.5
XS Rating Curve= 0
Exp/Cntr=.3,.1

Chan Stop Cuts=-1