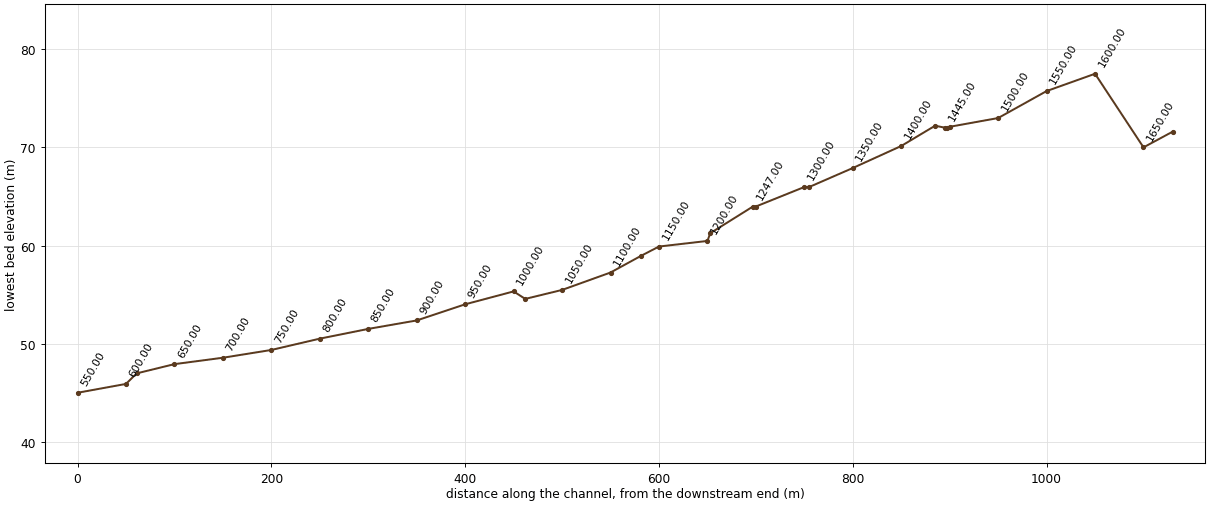
--- dmc.prj (project) ---

Proj Title=doomyung-ch
Current Plan=p01
Default Exp/Contr=.3,.1
SI Units
Geom File=g01
Flow File=f01
Plan File=p01
Y Axis Title=Elevation
X Axis Title(PF)=Main Channel Distance
X Axis Title(XS)=Station
BEGIN DESCRIPTION:
           BACK WATER COMPUTATION
      APPLICATION OF HEC-2 BY Samju Construction Engineering
      µÎ¸íÃµ(¿ËÃµÀ¾): 30,50,80,100,150³âºóµµ °³¼öÀü
END DESCRIPTION:
DSS File=dss
DSS Export Rating Curves= 0
DSS Export Rating Curve Sorted= 0
DSS Export Volume Flow Curves= 0
DXF OffsetX= 0
DXF OffsetY= 0
DXF ScaleX= 1
DXF ScaleY= 10

--- dmc.p01 (plan) ---

Plan Title=Imported Plan 01
Version=Version 3.0.1  Mar 2001
Short Identifier=Imported Pla
Geom File=g01
Flow File=f01
Subcritical Flow
K Sum by GR= 0
Std Step Tol= 0.003
Critical Tol= 0.003
Num of Std Step Trials= 20
Max Error Tol= 0.1
Flow Tol Ratio= 0.001
Split Flow NTrial= 30
Split Flow Tol= 0.02
Split Flow Ratio= 0.02
Log Output Level= 0
Friction Slope Method= 1
Unsteady Friction Slope Method= 2
Parabolic Critical Depth
Global Vel Dist= 0 , 0 , 0
Global Log Level= 0
CheckData=True
Encroach Param=-1 ,0,0, 0
Computation Interval=1HOUR
Output Interval=1HOUR
Run HTab= 0
Run UNet= 0
Run PostProcess= 0
UNET Theta= 1
UNET ZTol= 0.02
UNET ZSATol= 0.1
UNET MxIter= 20
UNET MaxInSteps= 20
UNET DtIC= 0
UNET DtMin= 0
UNET MaxCRTS= 20
UNET WFStab= 2
UNET SFStab= 1
UNET WFX= 1
UNET SFX= 1
UNET Convert EG Bridges=-1
UNET Use Existing IB Tables=-1
Instantaneous Interval=1HOUR
DSS File=dss
Write IC File= 0
Write Velocity= 0
Write Detailed= 0

--- dmc.f01 (steady flow) ---

Flow Title=Imported Flow 01
Version=Version 3.0.1  Mar 2001
Number of Profiles= 5
Profile Names=10yr,20yr,30yr,50yr,80yr
River Rch & RM=RIVER-1,Reach-1         ,33.03
   16.99   18.71   19.71   20.98   22.14
River Rch & RM=RIVER-1,Reach-1         ,22
    31.9   35.15   37.05   39.45   41.65
River Rch & RM=doomyung,doomyung        ,1680.00
   16.99   18.71   19.71   20.98   22.14
River Rch & RM=doomyung,doomyung        ,1100.00
    31.9   35.15   37.05   39.45   41.65
Boundary for River Rch & Prof#=doomyung,doomyung        , 1
Up Type= 0
Dn Type= 3
Dn Slope=.0268
Boundary for River Rch & Prof#=doomyung,doomyung        , 2
Up Type= 0
Dn Type= 3
Dn Slope=.0268
Boundary for River Rch & Prof#=doomyung,doomyung        , 3
Up Type= 0
Dn Type= 3
Dn Slope=.0268
Boundary for River Rch & Prof#=doomyung,doomyung        , 4
Up Type= 0
Dn Type= 3
Dn Slope=.0268
Boundary for River Rch & Prof#=doomyung,doomyung        , 5
Up Type= 0
Dn Type= 3
Dn Slope=.0268
DSS Import GetInterval= 0
DSS Import GetPeak= 0
DSS Import FillOption= 0

--- dmc.g01 (geometry) ---

Geom Title=Imported Geom 01
Version=Version 3.0.1  Mar 2001

River Reach=doomyung        ,doomyung
Reach XY= 2
              .5             .95              .5             .05

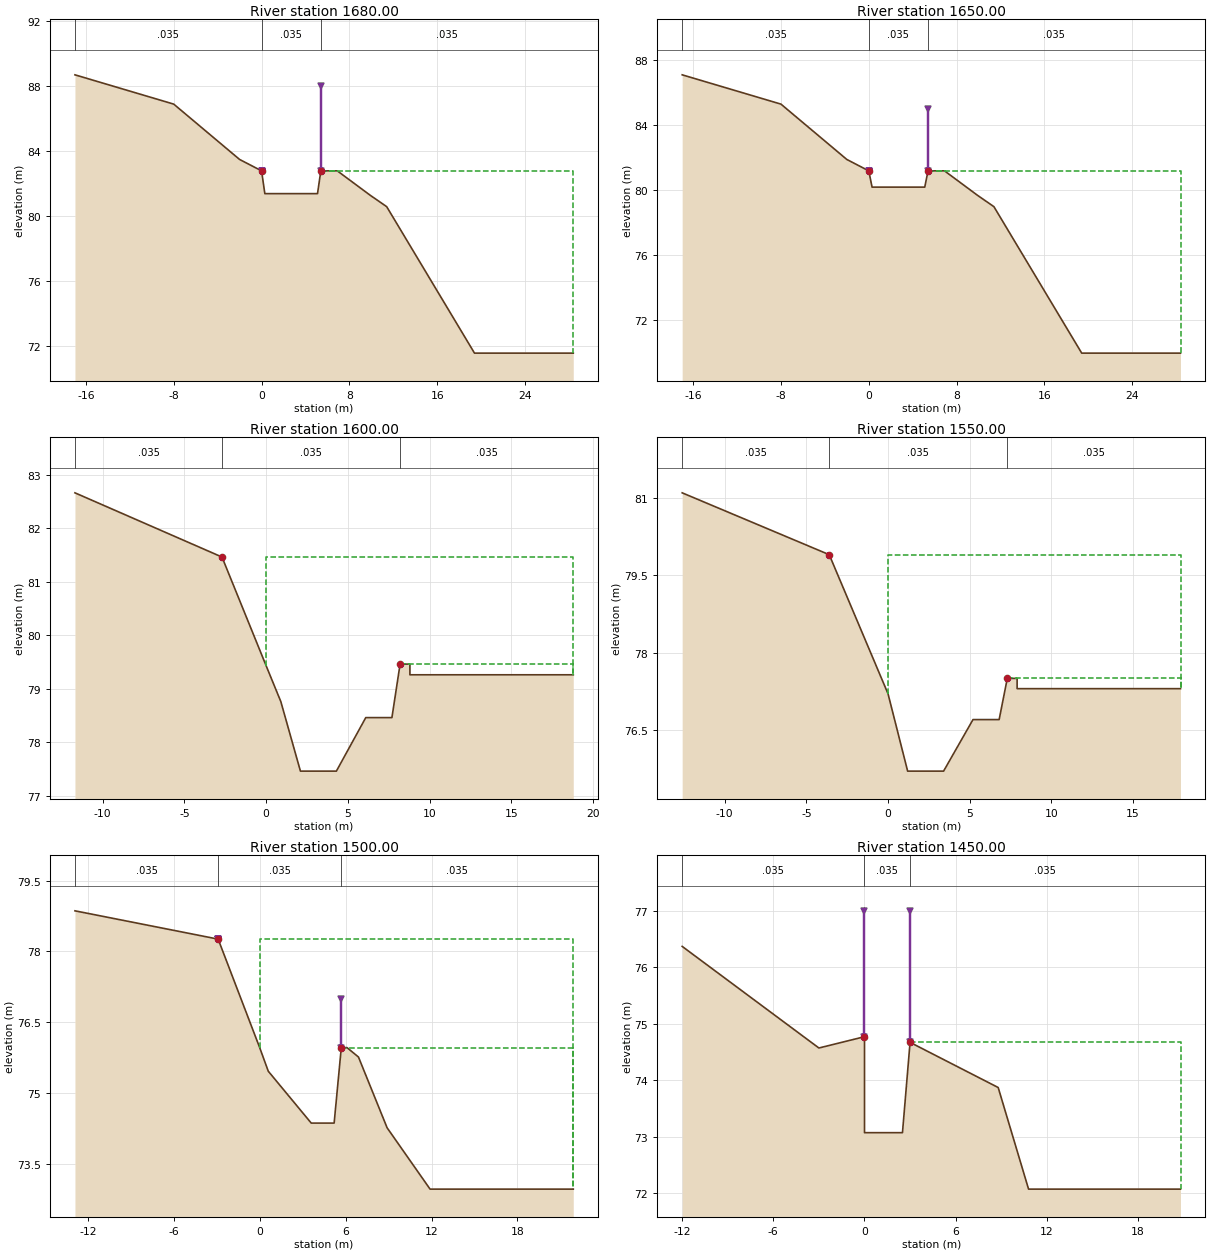
Type RM Length L Ch R = 1 ,1680.00 ,30,30,30
BEGIN DESCRIPTION:
33.03
END DESCRIPTION:
#Sta/Elev= 15
     -17   88.67     -14   88.07     -11   87.47      -8   86.87      -5   85.17
      -2   83.47       0   82.77      .3   81.37     5.1   81.37     5.4   82.77
     6.9   82.77     9.9   81.27    11.4   80.57    19.4   71.57    28.4   71.57
#Mann= 3 , 0 , 0
     -17    .035       0       0    .035       0     5.4    .035       0
Levee=-1,0,82.77,-1,5.4,88,,
#XS Ineff= 2 , 0
               0   82.77     5.4           82.77
Permanent Ineff=
       F       F
Bank Sta=0,5.4
XS Rating Curve= 0
Sediment Elevation=-12
Exp/Cntr=.3,.1

Type RM Length L Ch R = 1 ,1650.00 ,50,50,50
BEGIN DESCRIPTION:
33
END DESCRIPTION:
#Sta/Elev= 15
     -17   87.08     -14   86.48     -11   85.88      -8   85.28      -5   83.58
      -2   81.88       0   81.18      .3   80.18     5.1   80.18     5.4   81.18
     6.9   81.18     9.9   79.68    11.4   78.98    19.4   69.98    28.4   69.98
#Mann= 3 , 0 , 0
     -17    .035       0       0    .035       0     5.4    .035       0
Levee=-1,0,81.18,-1,5.4,85,,
#XS Ineff= 2 , 0
               0   81.18     5.4           81.18
Permanent Ineff=
       F       F
Bank Sta=0,5.4
XS Rating Curve= 0
Sediment Elevation=-12
Exp/Cntr=.3,.1

Type RM Length L Ch R = 1 ,1600.00 ,50,50,50
BEGIN DESCRIPTION:
32
END DESCRIPTION:
#Sta/Elev= 14
   -11.7   82.66    -8.7   82.26    -5.7   81.86    -2.7   81.46       0   79.43
      .9   78.76     2.1   77.46     4.3   77.46     6.1   78.46     7.7   78.46
     8.2   79.46     8.8   79.46     8.8   79.26    18.8   79.26
#Mann= 3 , 0 , 0
   -11.7    .035       0    -2.7    .035       0     8.2    .035       0
#XS Ineff= 2 , 0
       0    -2.7   81.46     8.2       0   79.46
Permanent Ineff=
       F       F
Bank Sta=-2.7,8.2
XS Rating Curve= 0
Sediment Elevation=-12
Exp/Cntr=.3,.1

Type RM Length L Ch R = 1 ,1550.00 ,50,50,50
BEGIN DESCRIPTION:
31
END DESCRIPTION:
#Sta/Elev= 13
   -12.6    81.1    -9.6    80.7    -6.6    80.3    -3.6    79.9       0    77.2
     1.2    75.7     3.4    75.7     5.2    76.7     6.8    76.7     7.3    77.5
     7.9    77.5     7.9    77.3    17.9    77.3
#Mann= 3 , 0 , 0
   -12.6    .035       0    -3.6    .035       0     7.3    .035       0
#XS Ineff= 2 , 0
       0    -3.6    79.9     7.3       0    77.5
Permanent Ineff=
       F       F
Bank Sta=-3.6,7.3
XS Rating Curve= 0
Sediment Elevation=-12
Exp/Cntr=.3,.1

Type RM Length L Ch R = 1 ,1500.00 ,50,50,50
BEGIN DESCRIPTION:
30
END DESCRIPTION:
#Sta/Elev= 13
   -12.9   78.86    -7.9   78.56    -2.9   78.26       0   75.96      .6   75.46
     3.6   74.36     5.2   74.36     5.7   75.96     6.1   75.96     6.9   75.76
     8.9   74.26    11.9   72.96    21.9   72.96
#Mann= 3 , 0 , 0
   -12.9    .035       0    -2.9    .035       0     5.7    .035       0
Levee=-1,-2.9,78.26,-1,5.7,77,,
#XS Ineff= 2 , 0
       0    -2.9   78.26     5.7       0   75.96
Permanent Ineff=
       F       F
Bank Sta=-2.9,5.7
XS Rating Curve= 0
Sediment Elevation=-12
Exp/Cntr=.3,.1

Type RM Length L Ch R = 1 ,1450.00 ,3,3,3
BEGIN DESCRIPTION:
29
END DESCRIPTION:
#Sta/Elev= 11
     -12   76.37      -9   75.77      -6   75.17      -3   74.57       0   74.77
       0   73.07     2.5   73.07       3   74.67     8.8   73.87    10.8   72.07
    20.8   72.07
#Mann= 3 , 0 , 0
     -12    .035       0       0    .035       0       3    .035       0
Levee=-1,0,77,-1,3,77,,
#XS Ineff= 2 , 0
               0   74.77       3           74.67
Permanent Ineff=
       F       F
Bank Sta=0,3
XS Rating Curve= 0
Sediment Elevation=-12
Exp/Cntr=.3,.1

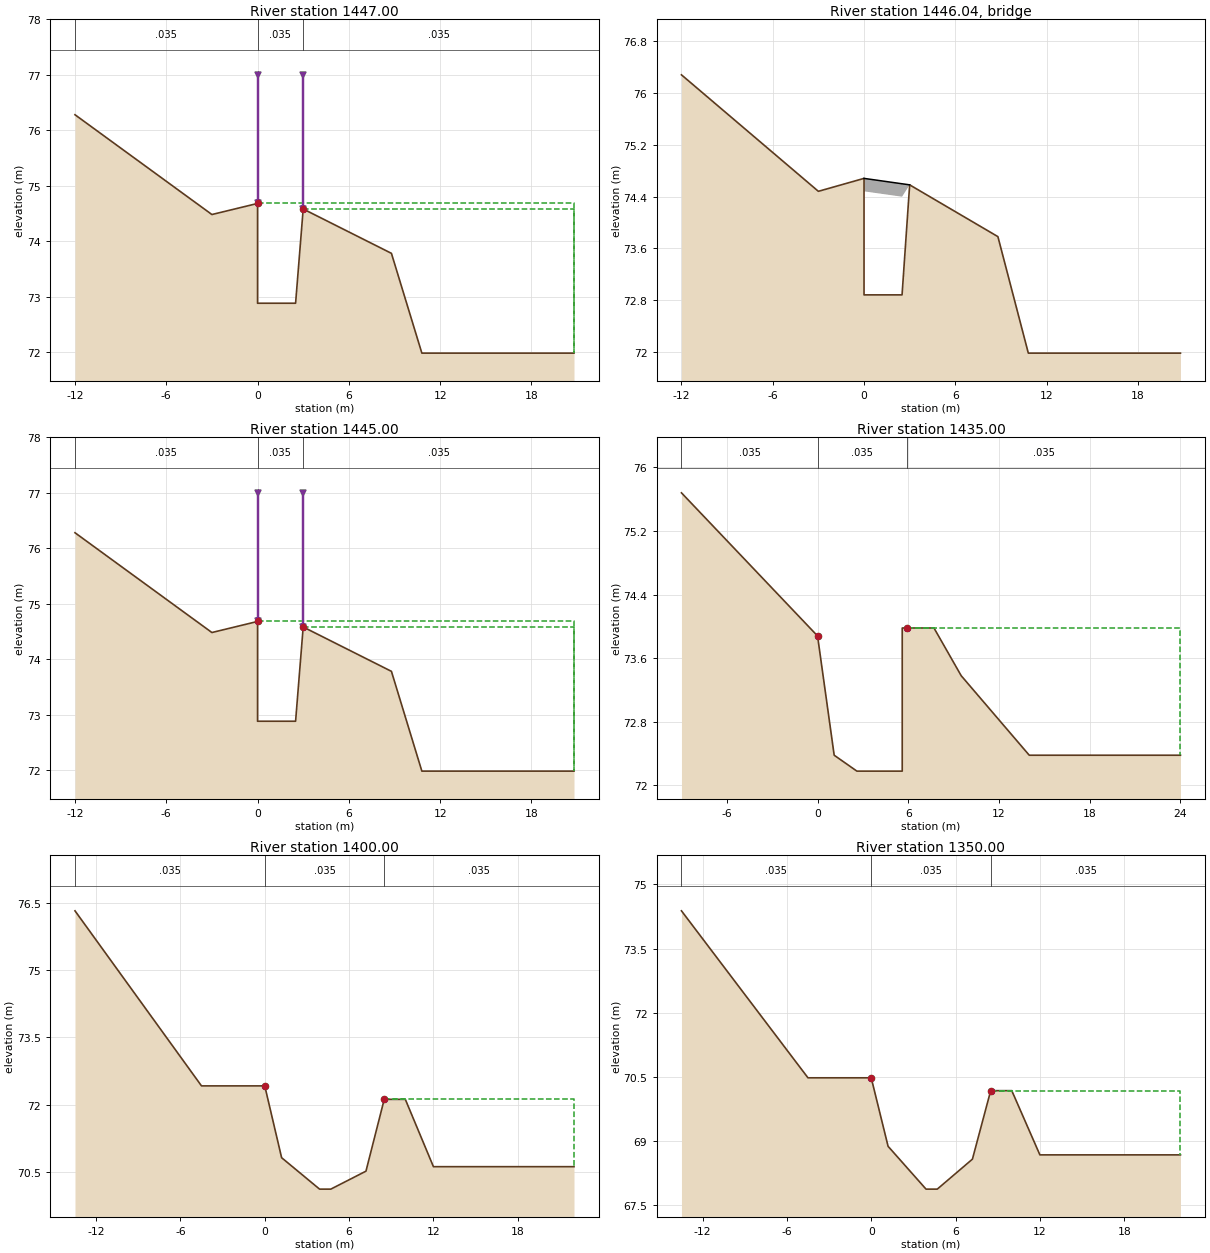
Type RM Length L Ch R = 1 ,1447.00 ,2,2,2
BEGIN DESCRIPTION:
28.047
END DESCRIPTION:
#Sta/Elev= 11
     -12   76.28      -9   75.68      -6   75.08      -3   74.48       0   74.68
       0   72.88     2.5   72.88       3   74.58     8.8   73.78    10.8   71.98
    20.8   71.98
#Mann= 3 , 0 , 0
     -12    .035       0       0    .035       0       3    .035       0
Levee=-1,0,77,-1,3,77,,
#XS Ineff= 2 , 0
       0       0   74.68       3       0   74.58
Permanent Ineff=
       F       F
Bank Sta=0,3
XS Rating Curve= 0
Sediment Elevation=-12
Exp/Cntr=.3,.1

Type RM Length L Ch R = 3 ,1446.04 ,,,
BEGIN DESCRIPTION:
28.046
END DESCRIPTION:
Bridge Culvert--1,0,-1,-1, 0
Deck Dist Width WeirC Skew NumUp NumDn MinLoCord MaxHiCord MaxSubmerge Is_Ogee
.01,1.9,1.44,0, 2, 2, , , .95, 0, 0,0,,
       0       3
   74.68   74.58
   74.48   74.38
       0       3
   74.68   74.58
   74.48   74.38
BR Coef=-1 , 1 , 0 ,, 0 ,,,.8,-1,1.2,0,
WSPro=,,,, 1 ,,,, 0 ,,,, 0 ,,,,-1 ,-1 ,-1 , 0 , 0 , 0 , 0 , 0
BC Design=,, 0 ,, 0 ,,,,,,

Type RM Length L Ch R = 1 ,1445.00 ,10,10,10
BEGIN DESCRIPTION:
28.045
END DESCRIPTION:
#Sta/Elev= 11
     -12   76.28      -9   75.68      -6   75.08      -3   74.48       0   74.68
       0   72.88     2.5   72.88       3   74.58     8.8   73.78    10.8   71.98
    20.8   71.98
#Mann= 3 , 0 , 0
     -12    .035       0       0    .035       0       3    .035       0
Levee=-1,0,77,-1,3,77,,
#XS Ineff= 2 , 0
       0       0   74.68       3       0   74.58
Permanent Ineff=
       F       F
Bank Sta=0,3
XS Rating Curve= 0
Sediment Elevation=-12
Exp/Cntr=.3,.1

Type RM Length L Ch R = 1 ,1435.00 ,35,35,35
BEGIN DESCRIPTION:
28.035
END DESCRIPTION:
#Sta/Elev= 13
      -9   75.68      -6   75.08      -3   74.48       0   73.88     1.1   72.38
     2.6   72.18     5.6   72.18     5.6   73.98     5.9   73.98     7.7   73.98
     9.5   73.38      14   72.38      24   72.38
#Mann= 3 , 0 , 0
      -9    .035       0       0    .035       0     5.9    .035       0
#XS Ineff= 2 , 0
               0   73.88     5.9           73.98
Permanent Ineff=
       F       F
Bank Sta=0,5.9
XS Rating Curve= 0
Exp/Cntr=.3,.1

Type RM Length L Ch R = 1 ,1400.00 ,50,50,50
BEGIN DESCRIPTION:
28
END DESCRIPTION:
#Sta/Elev= 13
   -13.5   76.32   -10.5   75.02    -7.5   73.72    -4.5   72.42       0   72.42
     1.2   70.82     3.9   70.12     4.7   70.12     7.2   70.52     8.5   72.12
      10   72.12      12   70.62      22   70.62
#Mann= 3 , 0 , 0
   -13.5    .035       0       0    .035       0     8.5    .035       0
#XS Ineff= 2 , 0
               0   72.42     8.5           72.12
Permanent Ineff=
       F       F
Bank Sta=0,8.5
XS Rating Curve= 0
Exp/Cntr=.3,.1

Type RM Length L Ch R = 1 ,1350.00 ,45,45,45
BEGIN DESCRIPTION:
27
END DESCRIPTION:
#Sta/Elev= 13
   -13.5   74.38   -10.5   73.08    -7.5   71.78    -4.5   70.48       0   70.48
     1.2   68.88     3.9   67.88     4.7   67.88     7.2   68.58     8.5   70.18
      10   70.18      12   68.68      22   68.68
#Mann= 3 , 0 , 0
   -13.5    .035       0       0    .035       0     8.5    .035       0
#XS Ineff= 2 , 0
               0   70.48     8.5           70.18
Permanent Ineff=
       F       F
Bank Sta=0,8.5
XS Rating Curve= 0
Exp/Cntr=.3,.1

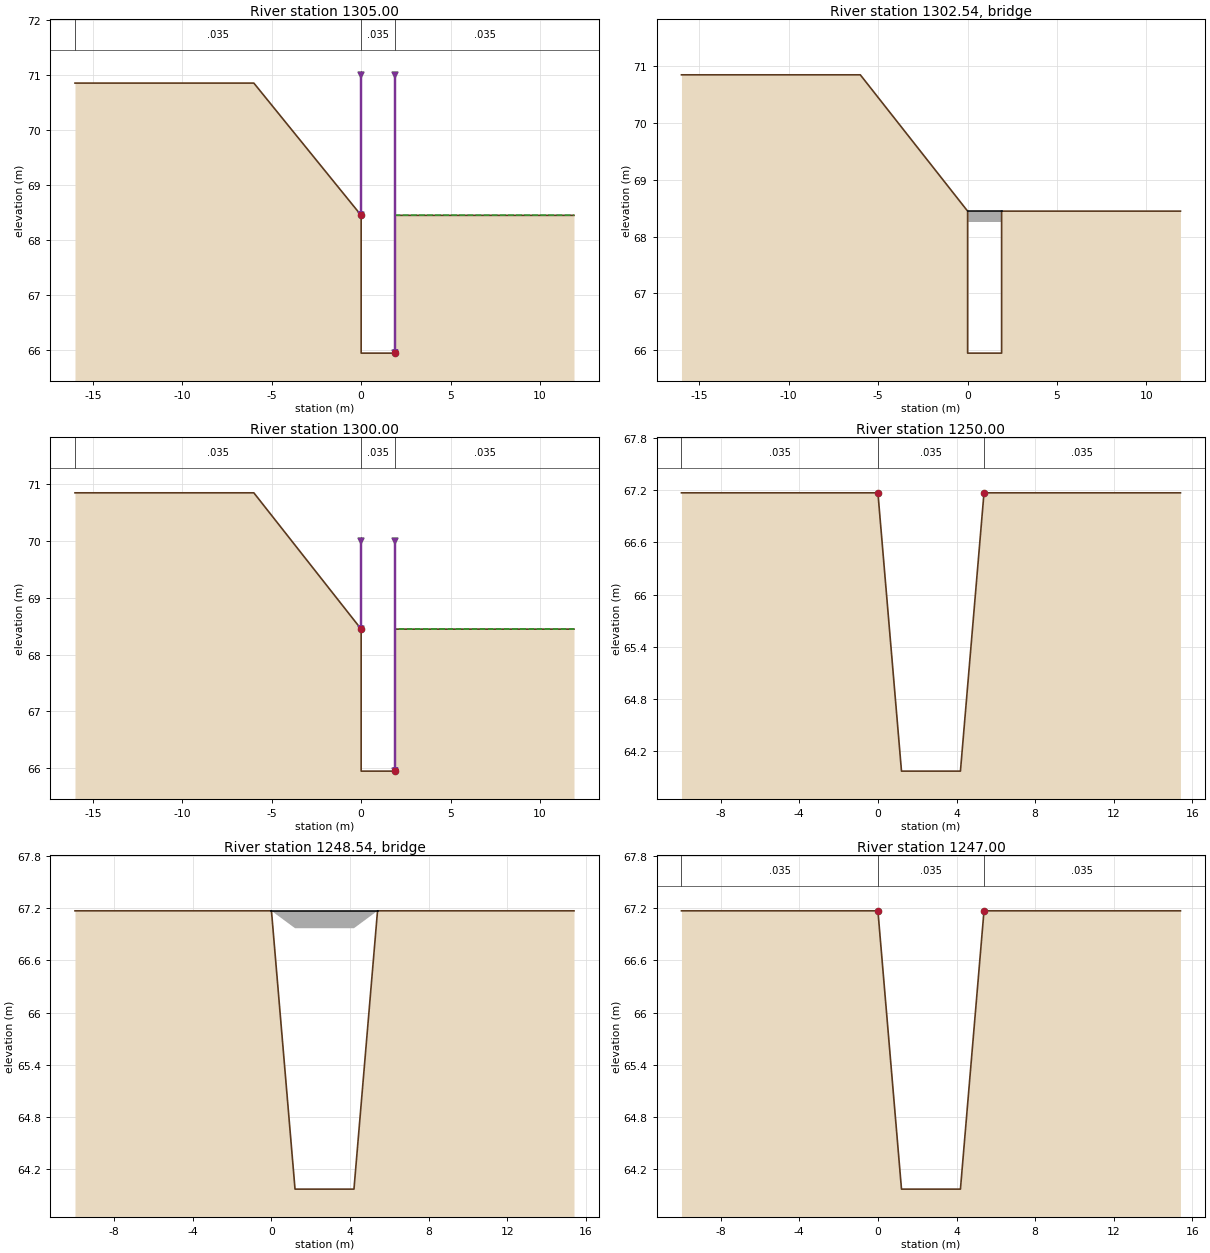
Type RM Length L Ch R = 1 ,1305.00 ,5,5,5
BEGIN DESCRIPTION:
26.005
END DESCRIPTION:
#Sta/Elev= 8
     -16   70.85      -6   70.85      -3   69.65       0   68.45       0   65.95
     1.9   65.95     1.9   68.45    11.9   68.45
#Mann= 3 , 0 , 0
     -16    .035       0       0    .035       0     1.9    .035       0
Levee=-1,0,71,-1,1.9,71,,
#XS Ineff= 2 , 0
               0   68.45     1.9           68.45
Permanent Ineff=
       F       F
Bank Sta=0,1.9
XS Rating Curve= 0
Exp/Cntr=.3,.1

Type RM Length L Ch R = 3 ,1302.54 ,,,
BEGIN DESCRIPTION:
26.0035
END DESCRIPTION:
Bridge Culvert--1,0,-1,-1, 0
Deck Dist Width WeirC Skew NumUp NumDn MinLoCord MaxHiCord MaxSubmerge Is_Ogee
.01,4.9,1.44,0, 2, 2, , , .95, 0, 0,0,,
       0     1.9
   68.45   68.45
   68.25   68.25
       0     1.9
   68.45   68.45
   68.25   68.25
BR Coef=-1 , 1 , 0 ,, 0 ,,,.8,-1,1.2,0,
WSPro=,,,, 1 ,,,, 0 ,,,, 0 ,,,,-1 ,-1 ,-1 , 0 , 0 , 0 , 0 , 0
BC Design=,, 0 ,, 0 ,,,,,,

Type RM Length L Ch R = 1 ,1300.00 ,50,50,50
BEGIN DESCRIPTION:
26
END DESCRIPTION:
#Sta/Elev= 8
     -16   70.85      -6   70.85      -3   69.65       0   68.45       0   65.95
     1.9   65.95     1.9   68.45    11.9   68.45
#Mann= 3 , 0 , 0
     -16    .035       0       0    .035       0     1.9    .035       0
Levee=-1,0,70,-1,1.9,70,,
#XS Ineff= 2 , 0
               0   68.45     1.9           68.45
Permanent Ineff=
       F       F
Bank Sta=0,1.9
XS Rating Curve= 0
Exp/Cntr=.3,.1

Type RM Length L Ch R = 1 ,1250.00 ,3,3,3
BEGIN DESCRIPTION:
25
END DESCRIPTION:
#Sta/Elev= 6
     -10   67.17       0   67.17     1.2   63.97     4.2   63.97     5.4   67.17
    15.4   67.17
#Mann= 3 , 0 , 0
     -10    .035       0       0    .035       0     5.4    .035       0
#XS Ineff= 2 , 0
               0   67.17     5.4           67.17
Permanent Ineff=
       F       F
Bank Sta=0,5.4
XS Rating Curve= 0
Exp/Cntr=.3,.1

Type RM Length L Ch R = 3 ,1248.54 ,,,
BEGIN DESCRIPTION:
24.0485
END DESCRIPTION:
Bridge Culvert--1,0,-1,-1, 0
Deck Dist Width WeirC Skew NumUp NumDn MinLoCord MaxHiCord MaxSubmerge Is_Ogee
.01,2.9,1.44,0, 2, 2, , , .95, 0, 0,0,,
       0     5.4
   67.17   67.17
   66.97   66.97
       0     5.4
   67.17   67.17
   66.97   66.97
BR Coef=-1 , 1 , 0 ,, 0 ,,,.8,-1,1.2,0,
WSPro=,,,, 1 ,,,, 0 ,,,, 0 ,,,,-1 ,-1 ,-1 , 0 , 0 , 0 , 0 , 0
BC Design=,, 0 ,, 0 ,,,,,,

Type RM Length L Ch R = 1 ,1247.00 ,44,44,44
BEGIN DESCRIPTION:
24.047
END DESCRIPTION:
#Sta/Elev= 6
     -10   67.17       0   67.17     1.2   63.97     4.2   63.97     5.4   67.17
    15.4   67.17
#Mann= 3 , 0 , 0
     -10    .035       0       0    .035       0     5.4    .035       0
#XS Ineff= 2 , 0
               0   67.17     5.4           67.17
Permanent Ineff=
       F       F
Bank Sta=0,5.4
XS Rating Curve= 0
Exp/Cntr=.3,.1

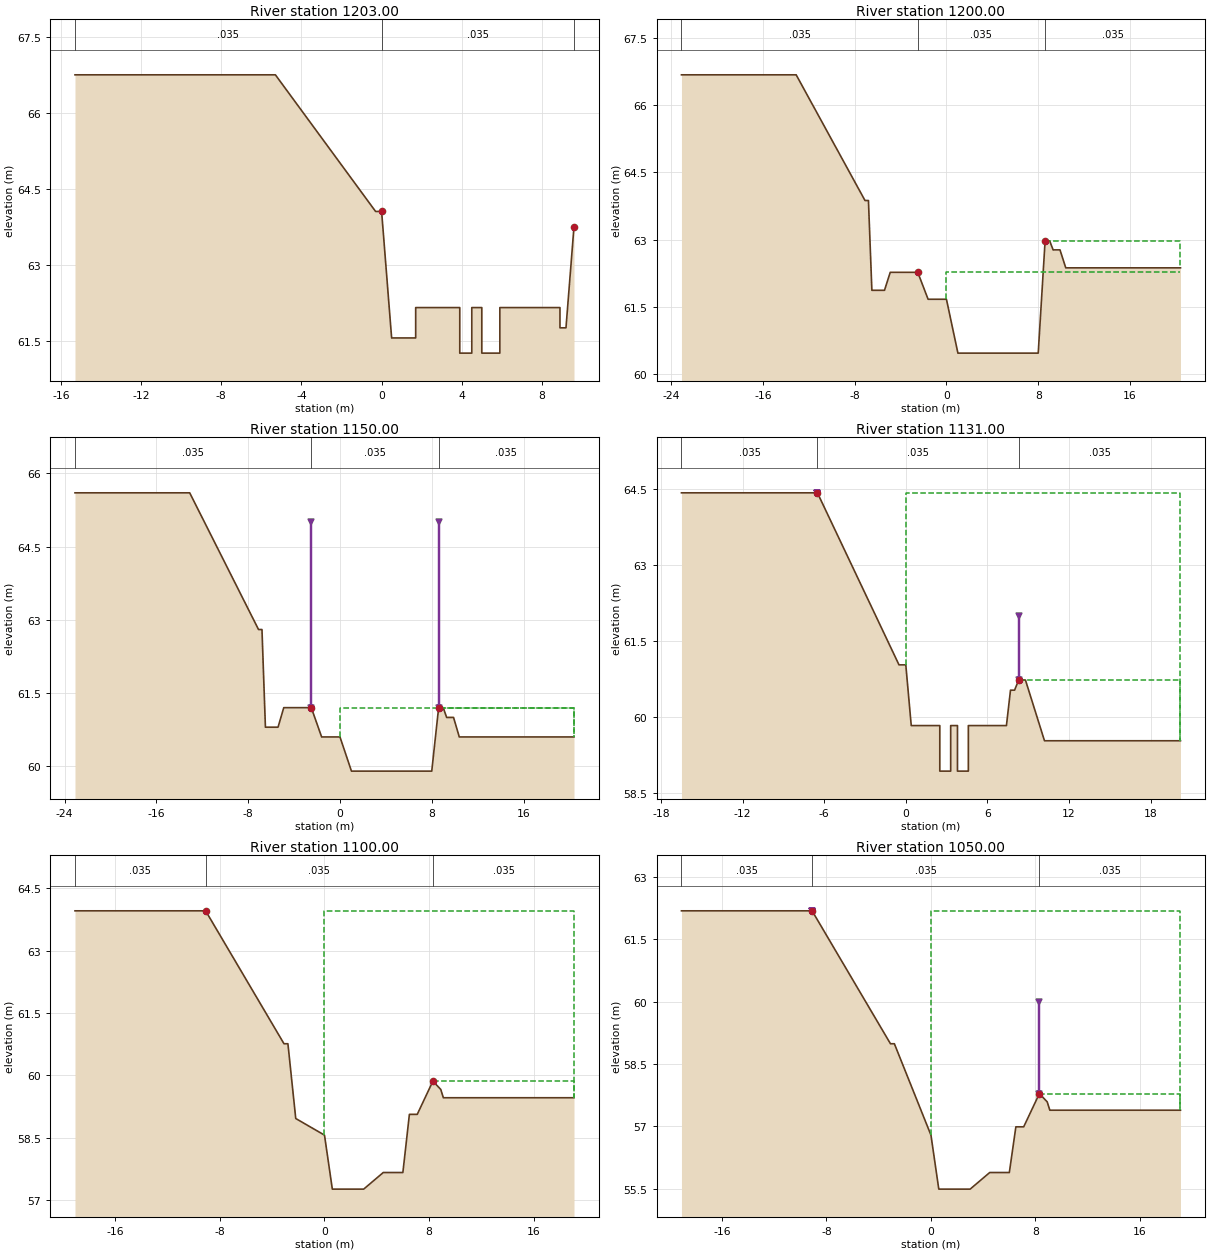
Type RM Length L Ch R = 1 ,1203.00 ,3,3,3
BEGIN DESCRIPTION:
24.003
END DESCRIPTION:
#Sta/Elev= 19
   -15.3   66.76    -5.3   66.76     -.3   64.06       0   64.06      .5   61.56
     1.7   61.56     1.7   62.16     3.9   62.16     3.9   61.26     4.5   61.26
     4.5   62.16       5   62.16       5   61.26     5.9   61.26     5.9   62.16
     8.9   62.16     8.9   61.76     9.2   61.76     9.6   63.76
#Mann= 3 , 0 , 0
   -15.3    .035       0       0    .035       0     9.6    .035       0
#XS Ineff= 2 , 0
               0   64.06     9.6           63.76
Permanent Ineff=
       F       F
Bank Sta=0,9.6
XS Rating Curve= 0
Exp/Cntr=.3,.1

Type RM Length L Ch R = 1 ,1200.00 ,50,50,50
BEGIN DESCRIPTION:
24
END DESCRIPTION:
#Sta/Elev= 19
   -23.1   66.67   -13.1   66.67   -10.1   65.27    -7.1   63.87    -6.8   63.87
    -6.5   61.87    -5.4   61.87    -4.9   62.27    -2.5   62.27    -1.6   61.67
       0   61.67       1   60.47       8   60.47     8.6   62.97       9   62.97
     9.3   62.77     9.9   62.77    10.4   62.37    20.4   62.37
#Mann= 3 , 0 , 0
   -23.1    .035       0    -2.5    .035       0     8.6    .035       0
#XS Ineff= 2 , 0
       0    -2.5   62.27     8.6       0   62.97
Permanent Ineff=
       F       F
Bank Sta=-2.5,8.6
XS Rating Curve= 0
Exp/Cntr=.3,.1

Type RM Length L Ch R = 1 ,1150.00 ,19,19,19
BEGIN DESCRIPTION:
23
END DESCRIPTION:
#Sta/Elev= 19
   -23.1    65.6   -13.1    65.6   -10.1    64.2    -7.1    62.8    -6.8    62.8
    -6.5    60.8    -5.4    60.8    -4.9    61.2    -2.5    61.2    -1.6    60.6
       0    60.6       1    59.9       8    59.9     8.6    61.2       9    61.2
     9.3      61     9.9      61    10.4    60.6    20.4    60.6
#Mann= 3 , 0 , 0
   -23.1    .035       0    -2.5    .035       0     8.6    .035       0
Levee=-1,-2.5,65,-1,8.6,65,,
#XS Ineff= 2 , 0
       0    -2.5    61.2     8.6       0    61.2
Permanent Ineff=
       F       F
Bank Sta=-2.5,8.6
XS Rating Curve= 0
Exp/Cntr=.3,.1

Type RM Length L Ch R = 1 ,1131.00 ,31,31,31
BEGIN DESCRIPTION:
22.031
END DESCRIPTION:
#Sta/Elev= 21
   -16.5   64.43    -6.5   64.43    -3.5   62.73     -.5   61.03       0   61.03
      .4   59.83     2.5   59.83     2.5   58.93     3.3   58.93     3.3   59.83
     3.8   59.83     3.8   58.93     4.6   58.93     4.6   59.83     7.4   59.83
     7.7   60.53       8   60.53     8.3   60.73     8.8   60.73    10.2   59.53
    20.2   59.53
#Mann= 3 , 0 , 0
   -16.5    .035       0    -6.5    .035       0     8.3    .035       0
Levee=-1,-6.5,64.43,-1,8.3,62,,
#XS Ineff= 2 , 0
       0    -6.5   64.43     8.3       0   60.73
Permanent Ineff=
       F       F
Bank Sta=-6.5,8.3
XS Rating Curve= 0
Exp/Cntr=.3,.1

Type RM Length L Ch R = 1 ,1100.00 ,50,50,50
BEGIN DESCRIPTION:
22
END DESCRIPTION:
#Sta/Elev= 17
   -19.1   63.96    -9.1   63.96    -6.1   62.36    -3.1   60.76    -2.8   60.76
    -2.2   58.96       0   58.56      .6   57.26       3   57.26     4.5   57.66
       6   57.66     6.5   59.06     7.1   59.06     8.3   59.86     8.9   59.66
     9.1   59.46    19.1   59.46
#Mann= 3 , 0 , 0
   -19.1    .035       0    -9.1    .035       0     8.3    .035       0
#XS Ineff= 2 , 0
       0    -9.1   63.96     8.3       0   59.86
Permanent Ineff=
       F       F
Bank Sta=-9.1,8.3
XS Rating Curve= 0
Exp/Cntr=.3,.1

Type RM Length L Ch R = 1 ,1050.00 ,38,38,38
BEGIN DESCRIPTION:
21
END DESCRIPTION:
#Sta/Elev= 16
   -19.1   62.19    -9.1   62.19    -6.1   60.59    -3.1   58.99    -2.8   58.99
       0   56.79      .6   55.49       3   55.49     4.5   55.89       6   55.89
     6.5   56.99     7.1   56.99     8.3   57.79     8.9   57.59     9.1   57.39
    19.1   57.39
#Mann= 3 , 0 , 0
   -19.1    .035       0    -9.1    .035       0     8.3    .035       0
Levee=-1,-9.1,62.19,-1,8.3,60,,
#XS Ineff= 2 , 0
       0    -9.1   62.19     8.3       0   57.79
Permanent Ineff=
       F       F
Bank Sta=-9.1,8.3
XS Rating Curve= 0
Exp/Cntr=.3,.1

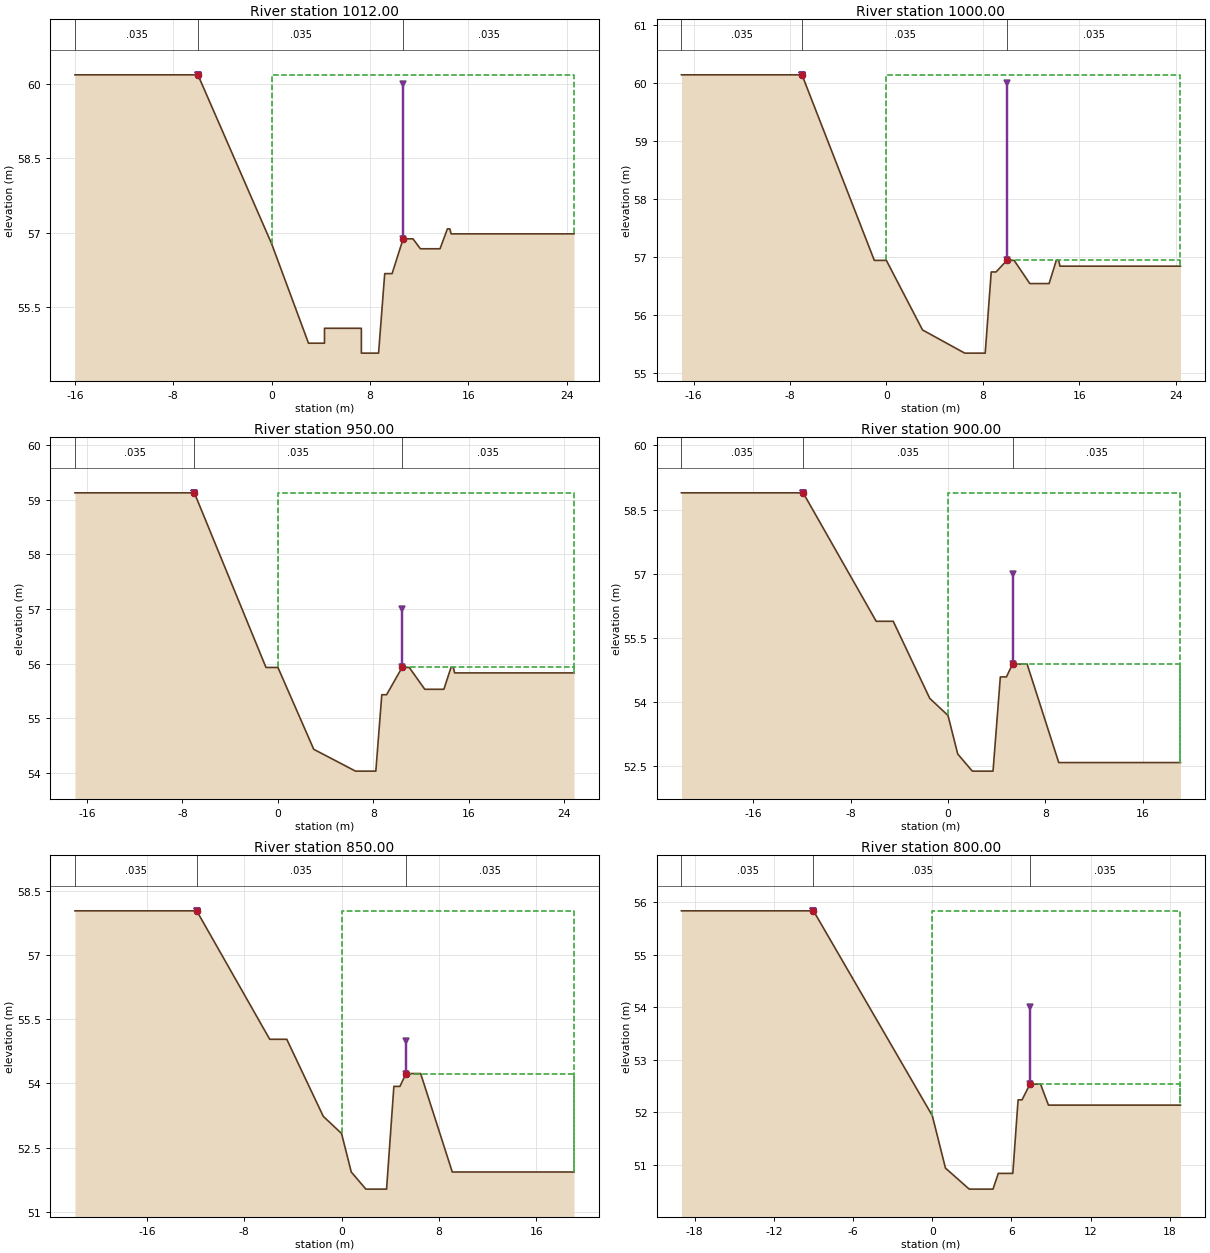
Type RM Length L Ch R = 1 ,1012.00 ,12,12,12
BEGIN DESCRIPTION:
20.012
END DESCRIPTION:
#Sta/Elev= 20
     -16   60.18      -6   60.18      -3   58.48       0   56.78       3   54.78
     4.3   54.78     4.3   55.08     7.3   55.08     7.3   54.58     8.7   54.58
     9.2   56.18     9.8   56.18    10.7   56.88    11.5   56.88    12.1   56.68
    13.7   56.68    14.3   57.08    14.5   57.08    14.6   56.98    24.6   56.98
#Mann= 3 , 0 , 0
     -16    .035       0      -6    .035       0    10.7    .035       0
Levee=-1,-6,60.18,-1,10.7,60,,
#XS Ineff= 2 , 0
       0      -6   60.18    10.7       0   56.88
Permanent Ineff=
       F       F
Bank Sta=-6,10.7
XS Rating Curve= 0
Exp/Cntr=.3,.1

Type RM Length L Ch R = 1 ,1000.00 ,50,50,50
BEGIN DESCRIPTION:
20
END DESCRIPTION:
#Sta/Elev= 18
     -17   60.14      -7   60.14      -4   58.54      -1   56.94       0   56.94
       3   55.74     6.5   55.34     8.2   55.34     8.7   56.74     9.1   56.74
      10   56.94    10.6   56.94    11.9   56.54    13.5   56.54    14.1   56.94
    14.3   56.94    14.4   56.84    24.4   56.84
#Mann= 3 , 0 , 0
     -17    .035       0      -7    .035       0      10    .035       0
Levee=-1,-7,60.14,-1,10,60,,
#XS Ineff= 2 , 0
       0      -7   60.14      10       0   56.94
Permanent Ineff=
       F       F
Bank Sta=-7,10
XS Rating Curve= 0
Exp/Cntr=.3,.1

Type RM Length L Ch R = 1 ,950.00  ,50,50,50
BEGIN DESCRIPTION:
19
END DESCRIPTION:
#Sta/Elev= 18
     -17   59.13      -7   59.13      -4   57.53      -1   55.93       0   55.93
       3   54.43     6.5   54.03     8.2   54.03     8.7   55.43     9.1   55.43
    10.4   55.93      11   55.93    12.3   55.53    13.9   55.53    14.5   55.93
    14.7   55.93    14.8   55.83    24.8   55.83
#Mann= 3 , 0 , 0
     -17    .035       0      -7    .035       0    10.4    .035       0
Levee=-1,-7,59.13,-1,10.4,57,,
#XS Ineff= 2 , 0
       0      -7   59.13    10.4       0   55.93
Permanent Ineff=
       F       F
Bank Sta=-7,10.4
XS Rating Curve= 0
Exp/Cntr=.3,.1

Type RM Length L Ch R = 1 ,900.00  ,50,50,50
BEGIN DESCRIPTION:
18
END DESCRIPTION:
#Sta/Elev= 16
   -21.9   58.89   -11.9   58.89    -8.9   57.39    -5.9   55.89    -4.5   55.89
    -1.5   54.09       0   53.69      .8   52.79       2   52.39     3.7   52.39
     4.3   54.59     4.8   54.59     5.3   54.89     6.5   54.89     9.1   52.59
    19.1   52.59
#Mann= 3 , 0 , 0
   -21.9    .035       0   -11.9    .035       0     5.3    .035       0
Levee=-1,-11.9,58.89,-1,5.3,57,,
#XS Ineff= 2 , 0
       0   -11.9   58.89     5.3       0   54.89
Permanent Ineff=
       F       F
Bank Sta=-11.9,5.3
XS Rating Curve= 0
Exp/Cntr=.3,.1

Type RM Length L Ch R = 1 ,850.00  ,50,50,50
BEGIN DESCRIPTION:
17
END DESCRIPTION:
#Sta/Elev= 16
   -21.9   58.03   -11.9   58.03    -8.9   56.53    -5.9   55.03    -4.5   55.03
    -1.5   53.23       0   52.83      .8   51.93       2   51.53     3.7   51.53
     4.3   53.93     4.8   53.93     5.3   54.23     6.5   54.23     9.1   51.93
    19.1   51.93
#Mann= 3 , 0 , 0
   -21.9    .035       0   -11.9    .035       0     5.3    .035       0
Levee=-1,-11.9,58.03,-1,5.3,55,,
#XS Ineff= 2 , 0
       0   -11.9   58.03     5.3       0   54.23
Permanent Ineff=
       F       F
Bank Sta=-11.9,5.3
XS Rating Curve= 0
Exp/Cntr=.3,.1

Type RM Length L Ch R = 1 ,800.00  ,50,50,50
BEGIN DESCRIPTION:
16
END DESCRIPTION:
#Sta/Elev= 16
     -19   55.84      -9   55.84      -6   54.54      -3   53.24       0   51.94
       1   50.94     2.8   50.54     4.6   50.54       5   50.84     6.1   50.84
     6.5   52.24     6.8   52.24     7.4   52.54     8.2   52.54     8.8   52.14
    18.8   52.14
#Mann= 3 , 0 , 0
     -19    .035       0      -9    .035       0     7.4    .035       0
Levee=-1,-9,55.84,-1,7.4,54,,
#XS Ineff= 2 , 0
       0      -9   55.84     7.4       0   52.54
Permanent Ineff=
       F       F
Bank Sta=-9,7.4
XS Rating Curve= 0
Exp/Cntr=.3,.1

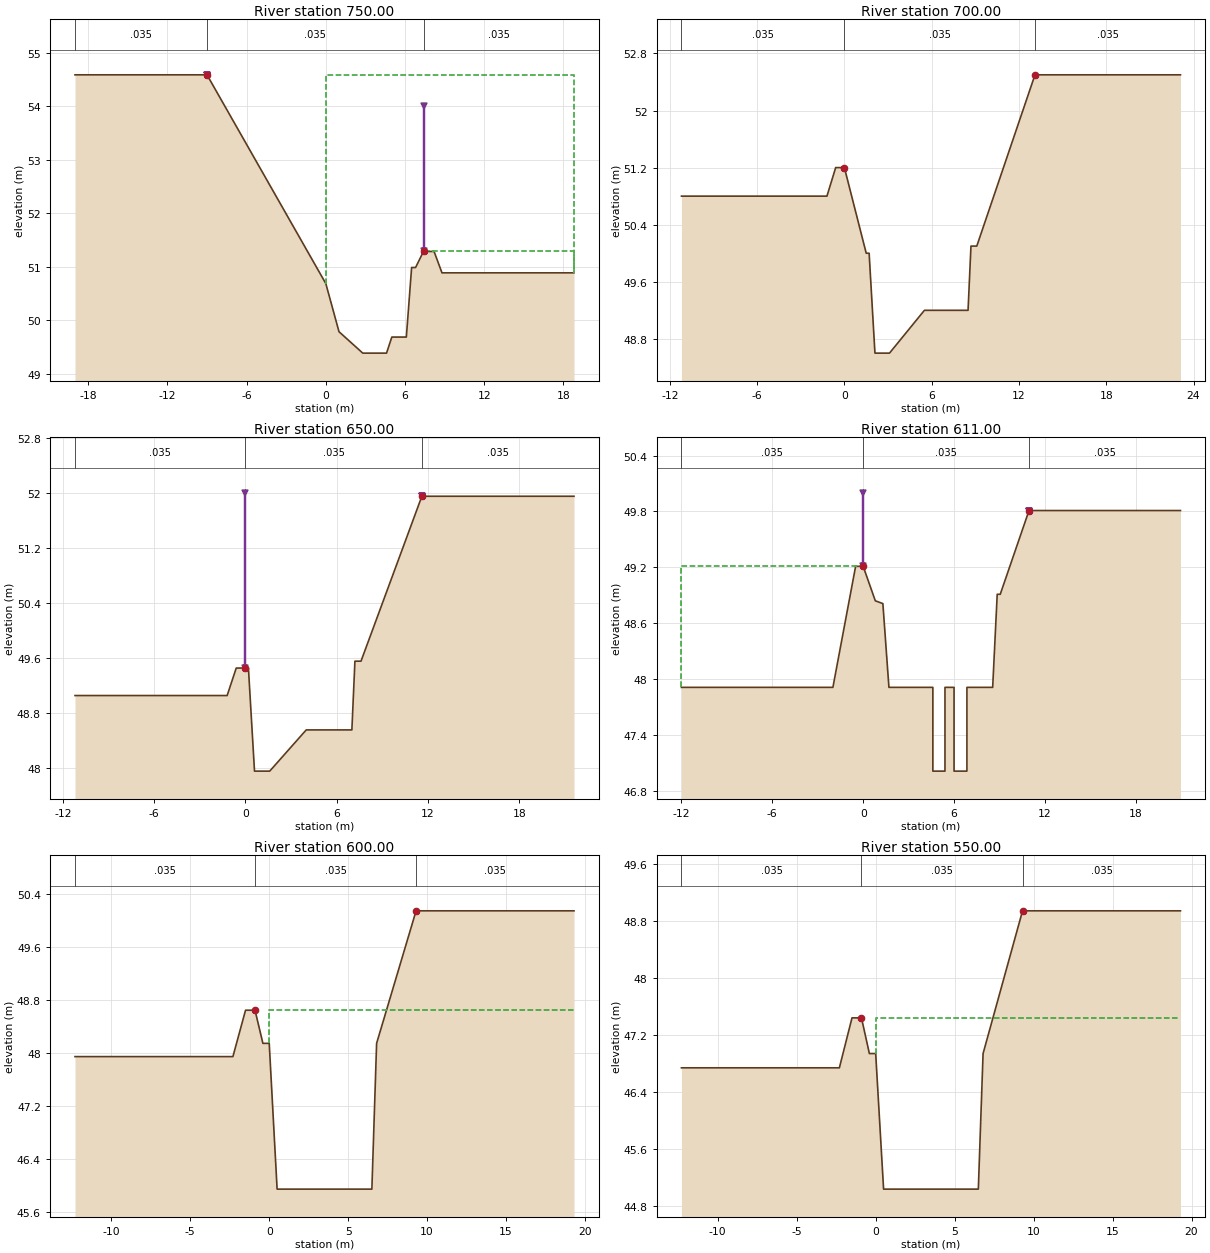
Type RM Length L Ch R = 1 ,750.00  ,50,50,50
BEGIN DESCRIPTION:
15
END DESCRIPTION:
#Sta/Elev= 16
     -19   54.59      -9   54.59      -6   53.29      -3   51.99       0   50.69
       1   49.79     2.8   49.39     4.6   49.39       5   49.69     6.1   49.69
     6.5   50.99     6.8   50.99     7.4   51.29     8.2   51.29     8.8   50.89
    18.8   50.89
#Mann= 3 , 0 , 0
     -19    .035       0      -9    .035       0     7.4    .035       0
Levee=-1,-9,54.59,-1,7.4,54,,
#XS Ineff= 2 , 0
       0      -9   54.59     7.4       0   51.29
Permanent Ineff=
       F       F
Bank Sta=-9,7.4
XS Rating Curve= 0
Exp/Cntr=.3,.1

Type RM Length L Ch R = 1 ,700.00  ,50,50,50
BEGIN DESCRIPTION:
14
END DESCRIPTION:
#Sta/Elev= 14
   -11.2    50.8    -1.2    50.8     -.6    51.2       0    51.2     1.5      50
     1.7      50     2.1    48.6     3.1    48.6     5.5    49.2     8.5    49.2
     8.7    50.1     9.1    50.1    13.1    52.5    23.1    52.5
#Mann= 3 , 0 , 0
   -11.2    .035       0       0    .035       0    13.1    .035       0
#XS Ineff= 2 , 0
       0       0    51.2    13.1       0    52.5
Permanent Ineff=
       F       F
Bank Sta=0,13.1
XS Rating Curve= 0
Exp/Cntr=.3,.1

Type RM Length L Ch R = 1 ,650.00  ,39,39,39
BEGIN DESCRIPTION:
13
END DESCRIPTION:
#Sta/Elev= 13
   -11.2   49.05    -1.2   49.05     -.6   49.45       0   49.45      .2   49.45
      .6   47.95     1.6   47.95       4   48.55       7   48.55     7.2   49.55
     7.6   49.55    11.6   51.95    21.6   51.95
#Mann= 3 , 0 , 0
   -11.2    .035       0       0    .035       0    11.6    .035       0
Levee=-1,0,52,-1,11.6,51.95,,
#XS Ineff= 2 , 0
       0       0   49.45    11.6       0   51.95
Permanent Ineff=
       F       F
Bank Sta=0,11.6
XS Rating Curve= 0
Exp/Cntr=.3,.1

Type RM Length L Ch R = 1 ,611.00  ,11,11,11
BEGIN DESCRIPTION:
12.011
END DESCRIPTION:
#Sta/Elev= 20
     -12   47.91      -2   47.91     -.5   49.21       0   49.21      .8   48.84
     1.3   48.81     1.7   47.91     4.6   47.91     4.6   47.01     5.4   47.01
     5.4   47.91       6   47.91       6   47.01    6.85   47.01    6.85   47.91
    8.55   47.91    8.85   48.91    9.05   48.91   10.95   49.81   20.95   49.81
#Mann= 3 , 0 , 0
     -12    .035       0       0    .035       0   10.95    .035       0
Levee=-1,0,50,-1,10.95,49.81,,
#XS Ineff= 2 , 0
               0   49.21   10.95           49.81
Permanent Ineff=
       F       F
Bank Sta=0,10.95
XS Rating Curve= 0
Exp/Cntr=.3,.1

Type RM Length L Ch R = 1 ,600.00  ,50,50,50
BEGIN DESCRIPTION:
12
END DESCRIPTION:
#Sta/Elev= 11
   -12.3   47.94    -2.3   47.94    -1.5   48.64     -.9   48.64     -.4   48.14
       0   48.14      .5   45.94     6.5   45.94     6.8   48.14     9.3   50.14
    19.3   50.14
#Mann= 3 , 0 , 0
   -12.3    .035       0     -.9    .035       0     9.3    .035       0
#XS Ineff= 2 , 0
       0     -.9   48.64     9.3       0   50.14
Permanent Ineff=
       F       F
Bank Sta=-.9,9.3
XS Rating Curve= 0
Exp/Cntr=.3,.1

Type RM Length L Ch R = 1 ,550.00  ,42,42,42
BEGIN DESCRIPTION:
11
END DESCRIPTION:
#Sta/Elev= 11
   -12.3   46.74    -2.3   46.74    -1.5   47.44     -.9   47.44     -.4   46.94
       0   46.94      .5   45.04     6.5   45.04     6.8   46.94     9.3   48.94
    19.3   48.94
#Mann= 3 , 0 , 0
   -12.3    .035       0     -.9    .035       0     9.3    .035       0
#XS Ineff= 2 , 0
       0     -.9   47.44     9.3       0   48.94
Permanent Ineff=
       F       F
Bank Sta=-.9,9.3
XS Rating Curve= 0
Exp/Cntr=.3,.1