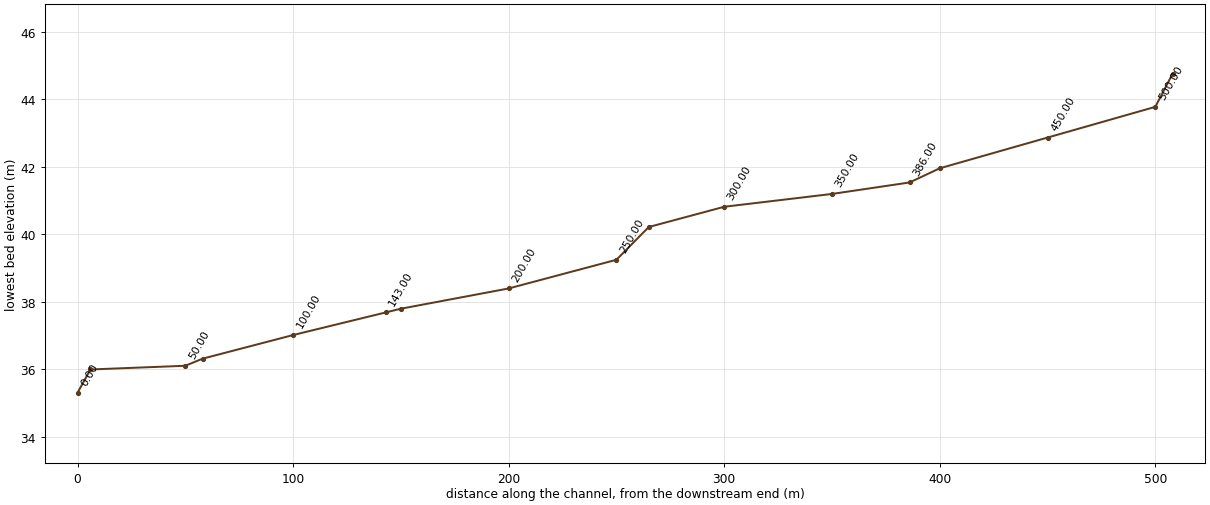
HEC-RAS study dmc.prj: doomyung-ch

--- dmc.g01 (geometry) --- (continued)

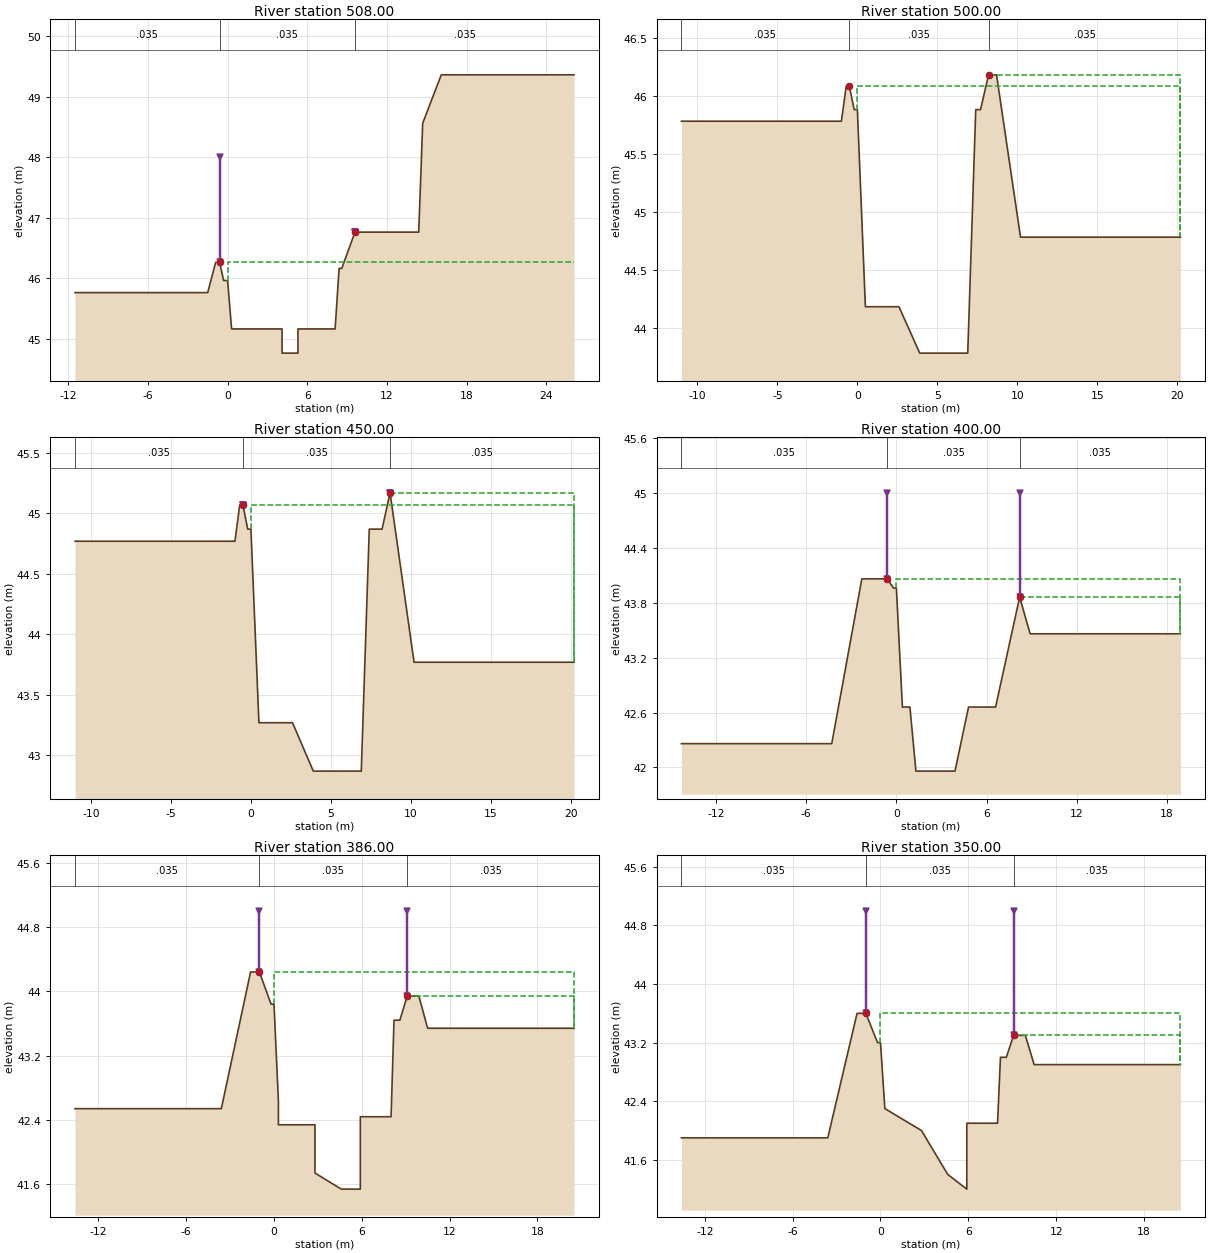
Type RM Length L Ch R = 1 ,508.00  ,8,8,8
BEGIN DESCRIPTION:
10.008
END DESCRIPTION:
#Sta/Elev= 19
   -11.5   45.76    -1.5   45.76     -.9   46.26     -.6   46.26     -.3   45.96
       0   45.96      .3   45.16     4.1   45.16     4.1   44.76     5.3   44.76
     5.3   45.16     8.1   45.16     8.4   46.16     8.6   46.16     9.6   46.76
    14.4   46.76    14.7   48.56    16.1   49.36    26.1   49.36
#Mann= 3 , 0 , 0
   -11.5    .035       0     -.6    .035       0     9.6    .035       0
Levee=-1,-.6,48,-1,9.6,46.76,,
#XS Ineff= 2 , 0
       0     -.6   46.26     9.6       0   46.76
Permanent Ineff=
       F       F
Bank Sta=-.6,9.6
XS Rating Curve= 0
Exp/Cntr=.3,.1

Type RM Length L Ch R = 1 ,500.00  ,50,50,50
BEGIN DESCRIPTION:
10
END DESCRIPTION:
#Sta/Elev= 16
     -11   45.78      -1   45.78     -.7   46.08     -.5   46.08     -.2   45.88
       0   45.88      .5   44.18     2.6   44.18     3.9   43.78     6.9   43.78
     7.4   45.88     7.7   45.88     8.2   46.18     8.7   46.18    10.2   44.78
    20.2   44.78
#Mann= 3 , 0 , 0
     -11    .035       0     -.5    .035       0     8.2    .035       0
#XS Ineff= 2 , 0
       0     -.5   46.08     8.2       0   46.18
Permanent Ineff=
       F       F
Bank Sta=-.5,8.2
XS Rating Curve= 0
Exp/Cntr=.3,.1

Type RM Length L Ch R = 1 ,450.00  ,50,50,50
BEGIN DESCRIPTION:
9
END DESCRIPTION:
#Sta/Elev= 15
     -11   44.77      -1   44.77     -.7   45.07     -.5   45.07     -.2   44.87
       0   44.87      .5   43.27     2.6   43.27     3.9   42.87     6.9   42.87
     7.4   44.87     8.2   44.87     8.7   45.17    10.2   43.77    20.2   43.77
#Mann= 3 , 0 , 0
     -11    .035       0     -.5    .035       0     8.7    .035       0
Levee=-1,-.5,45.07,-1,8.7,45.17,,
#XS Ineff= 2 , 0
       0     -.5   45.07     8.7       0   45.17
Permanent Ineff=
       F       F
Bank Sta=-.5,8.7
XS Rating Curve= 0
Exp/Cntr=.3,.1

Type RM Length L Ch R = 1 ,400.00  ,14,14,14
BEGIN DESCRIPTION:
8
END DESCRIPTION:
#Sta/Elev= 15
   -14.3   42.26    -4.3   42.26    -2.3   44.06     -.6   44.06     -.2   43.96
       0   43.96      .4   42.66      .9   42.66     1.3   41.96     3.9   41.96
     4.8   42.66     6.6   42.66     8.2   43.86     8.9   43.46    18.9   43.46
#Mann= 3 , 0 , 0
   -14.3    .035       0     -.6    .035       0     8.2    .035       0
Levee=-1,-.6,45,-1,8.2,45,,
#XS Ineff= 2 , 0
       0     -.6   44.06     8.2       0   43.86
Permanent Ineff=
       F       F
Bank Sta=-.6,8.2
XS Rating Curve= 0
Exp/Cntr=.3,.1

Type RM Length L Ch R = 1 ,386.00  ,36,36,36
BEGIN DESCRIPTION:
7.036
END DESCRIPTION:
#Sta/Elev= 20
   -13.6   42.54    -3.6   42.54    -1.6   44.24      -1   44.24     -.2   43.84
       0   43.84      .3   42.64      .3   42.34     2.8   42.34     2.8   41.74
     4.6   41.54     5.9   41.54     5.9   42.44       8   42.44     8.2   43.64
     8.6   43.64     9.1   43.94     9.9   43.94    10.5   43.54    20.5   43.54
#Mann= 3 , 0 , 0
   -13.6    .035       0      -1    .035       0     9.1    .035       0
Levee=-1,-1,45,-1,9.1,45,,
#XS Ineff= 2 , 0
       0      -1   44.24     9.1       0   43.94
Permanent Ineff=
       F       F
Bank Sta=-1,9.1
XS Rating Curve= 0
Exp/Cntr=.3,.1

Type RM Length L Ch R = 1 ,350.00  ,50,50,50
BEGIN DESCRIPTION:
7
END DESCRIPTION:
#Sta/Elev= 18
   -13.6    41.9    -3.6    41.9    -1.6    43.6      -1    43.6     -.2    43.2
       0    43.2      .3    42.3     2.8      42     4.6    41.4     5.9    41.2
     5.9    42.1       8    42.1     8.2      43     8.6      43     9.1    43.3
     9.9    43.3    10.5    42.9    20.5    42.9
#Mann= 3 , 0 , 0
   -13.6    .035       0      -1    .035       0     9.1    .035       0
Levee=-1,-1,45,-1,9.1,45,,
#XS Ineff= 2 , 0
       0      -1    43.6     9.1       0    43.3
Permanent Ineff=
       F       F
Bank Sta=-1,9.1
XS Rating Curve= 0
Exp/Cntr=.3,.1

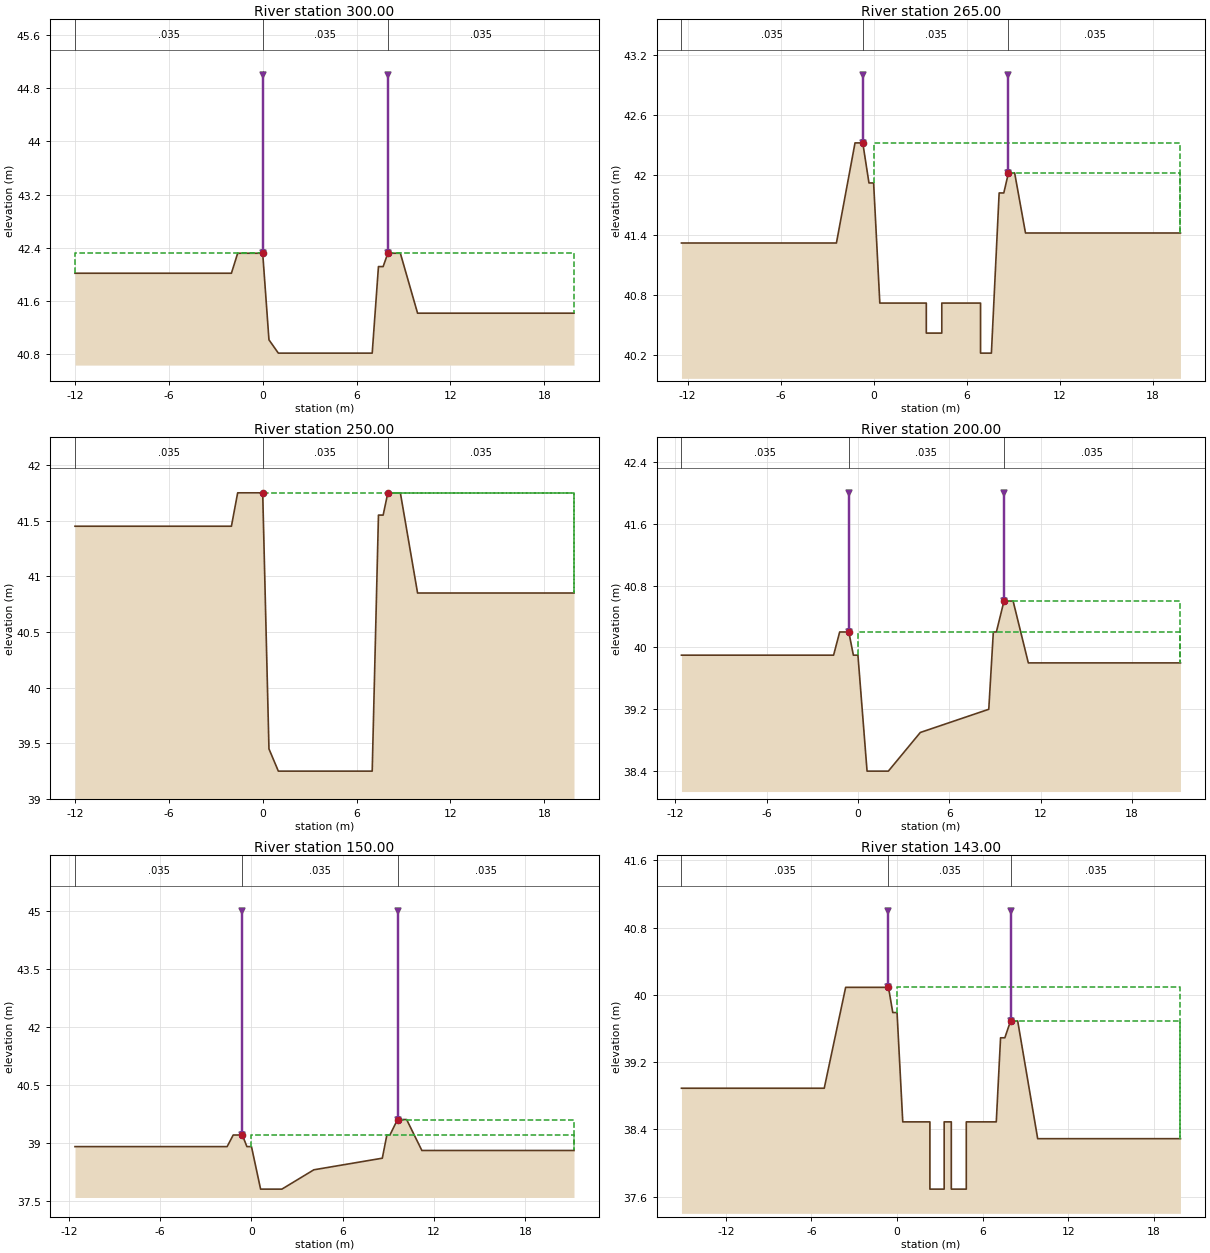
Type RM Length L Ch R = 1 ,300.00  ,35,35,35
BEGIN DESCRIPTION:
6
END DESCRIPTION:
#Sta/Elev= 13
     -12   42.02      -2   42.02    -1.6   42.32       0   42.32      .4   41.02
       1   40.82       7   40.82     7.4   42.12     7.7   42.12       8   42.32
     8.8   42.32     9.9   41.42    19.9   41.42
#Mann= 3 , 0 , 0
     -12    .035       0       0    .035       0       8    .035       0
Levee=-1,0,45,-1,8,45,,
#XS Ineff= 2 , 0
               0   42.32       8           42.32
Permanent Ineff=
       F       F
Bank Sta=0,8
XS Rating Curve= 0
Exp/Cntr=.3,.1

Type RM Length L Ch R = 1 ,265.00  ,15,15,15
BEGIN DESCRIPTION:
5.015
END DESCRIPTION:
#Sta/Elev= 20
   -12.4   41.32    -2.4   41.32    -1.2   42.32     -.7   42.32     -.3   41.92
       0   41.92      .4   40.72     3.4   40.72     3.4   40.42     4.4   40.42
     4.4   40.72     6.9   40.72     6.9   40.22     7.6   40.22     8.1   41.82
     8.4   41.82     8.7   42.02     9.1   42.02     9.8   41.42    19.8   41.42
#Mann= 3 , 0 , 0
   -12.4    .035       0     -.7    .035       0     8.7    .035       0
Levee=-1,-.7,43,-1,8.7,43,,
#XS Ineff= 2 , 0
       0     -.7   42.32     8.7       0   42.02
Permanent Ineff=
       F       F
Bank Sta=-.7,8.7
XS Rating Curve= 0
Exp/Cntr=.3,.1

Type RM Length L Ch R = 1 ,250.00  ,50,50,50
BEGIN DESCRIPTION:
5
END DESCRIPTION:
#Sta/Elev= 13
     -12   41.45      -2   41.45    -1.6   41.75       0   41.75      .4   39.45
       1   39.25       7   39.25     7.4   41.55     7.7   41.55       8   41.75
     8.8   41.75     9.9   40.85    19.9   40.85
#Mann= 3 , 0 , 0
     -12    .035       0       0    .035       0       8    .035       0
#XS Ineff= 2 , 0
       0       0   41.75       8       0   41.75
Permanent Ineff=
       F       F
Bank Sta=0,8
XS Rating Curve= 0
Exp/Cntr=.3,.1

Type RM Length L Ch R = 1 ,200.00  ,50,50,50
BEGIN DESCRIPTION:
4
END DESCRIPTION:
#Sta/Elev= 16
   -11.6    39.9    -1.6    39.9    -1.2    40.2     -.6    40.2     -.3    39.9
       0    39.9      .6    38.4       2    38.4     4.1    38.9     8.6    39.2
     8.9    40.2     9.1    40.2     9.6    40.6    10.2    40.6    11.2    39.8
    21.2    39.8
#Mann= 3 , 0 , 0
   -11.6    .035       0     -.6    .035       0     9.6    .035       0
Levee=-1,-.6,42,-1,9.6,42,,
#XS Ineff= 2 , 0
       0     -.6    40.2     9.6       0    40.6
Permanent Ineff=
       F       F
Bank Sta=-.6,9.6
XS Rating Curve= 0
Exp/Cntr=.3,.1

Type RM Length L Ch R = 1 ,150.00  ,7,7,7
BEGIN DESCRIPTION:
3
END DESCRIPTION:
#Sta/Elev= 16
   -11.6    38.9    -1.6    38.9    -1.2    39.2     -.6    39.2     -.3    38.9
       0    38.9      .6    37.8       2    37.8     4.1    38.3     8.6    38.6
     8.9    39.2     9.1    39.2     9.6    39.6    10.2    39.6    11.2    38.8
    21.2    38.8
#Mann= 3 , 0 , 0
   -11.6    .035       0     -.6    .035       0     9.6    .035       0
Levee=-1,-.6,45,-1,9.6,45,,
#XS Ineff= 2 , 0
       0     -.6    39.2     9.6       0    39.6
Permanent Ineff=
       F       F
Bank Sta=-.6,9.6
XS Rating Curve= 0
Exp/Cntr=.3,.1

Type RM Length L Ch R = 1 ,143.00  ,43,43,43
BEGIN DESCRIPTION:
2.043
END DESCRIPTION:
#Sta/Elev= 22
   -15.1   38.89    -5.1   38.89    -3.6   40.09     -.6   40.09     -.3   39.79
       0   39.79      .4   38.49     2.3   38.49     2.3   37.69     3.3   37.69
     3.3   38.49     3.8   38.49     3.8   37.69    4.85   37.69    4.85   38.49
    6.95   38.49    7.25   39.49    7.55   39.49    7.95   39.69    8.45   39.69
    9.85   38.29   19.85   38.29
#Mann= 3 , 0 , 0
   -15.1    .035       0     -.6    .035       0    7.95    .035       0
Levee=-1,-.6,41,-1,7.95,41,,
#XS Ineff= 2 , 0
       0     -.6   40.09    7.95       0   39.69
Permanent Ineff=
       F       F
Bank Sta=-.6,7.95
XS Rating Curve= 0
Exp/Cntr=.3,.1

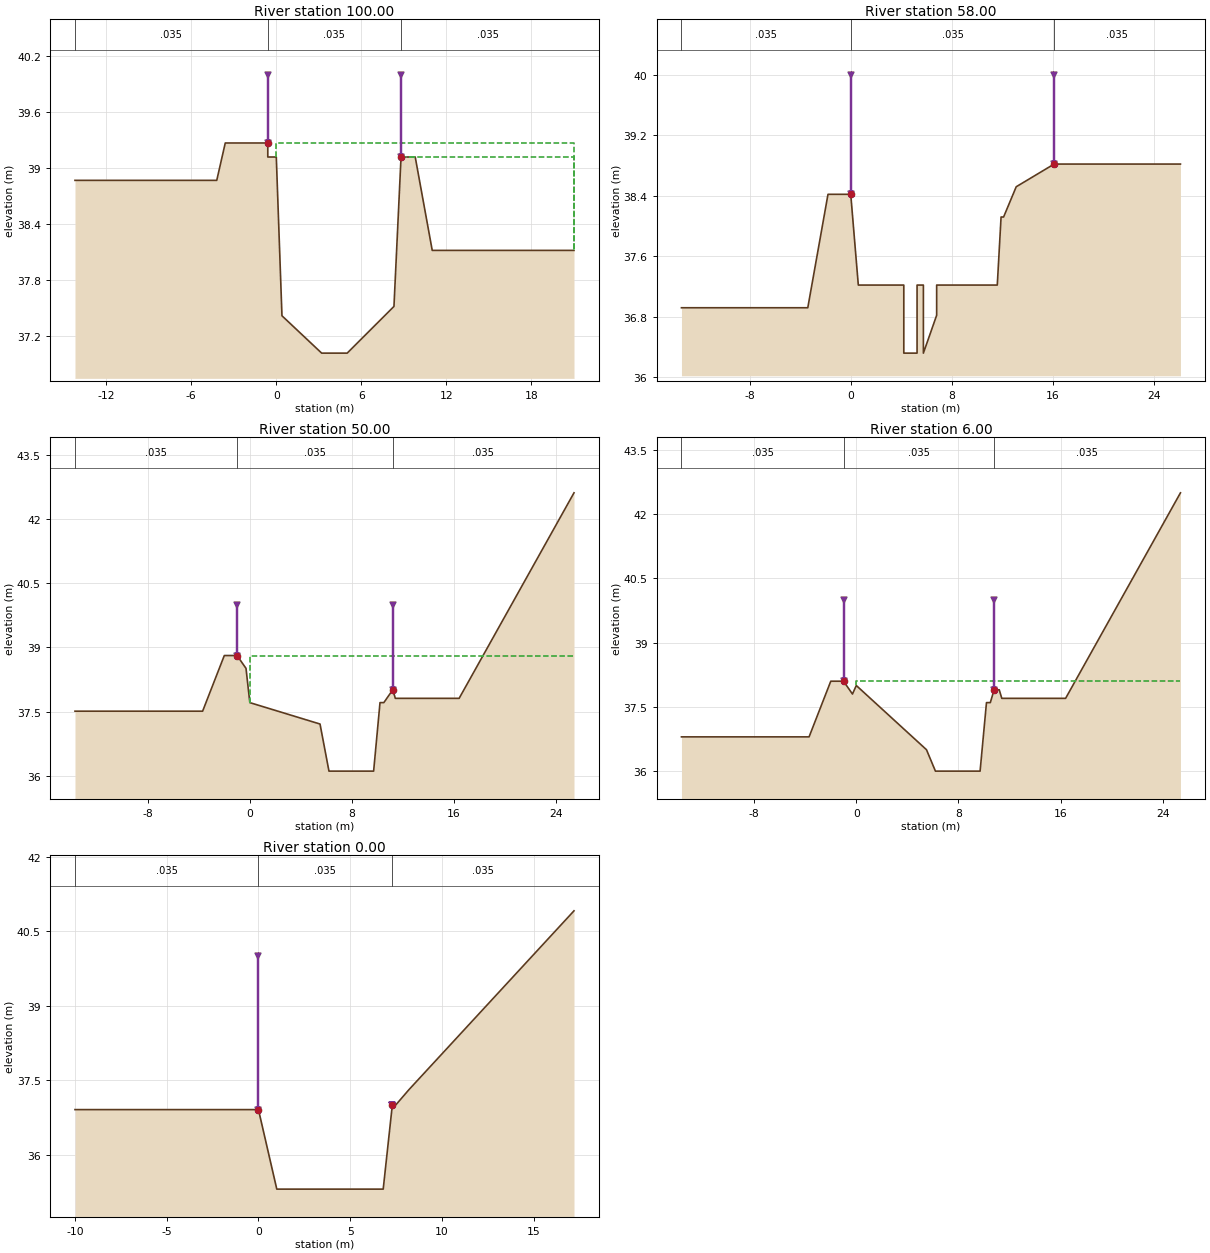
Type RM Length L Ch R = 1 ,100.00  ,42,42,42
BEGIN DESCRIPTION:
2
END DESCRIPTION:
#Sta/Elev= 14
   -14.2   38.87    -4.2   38.87    -3.6   39.27     -.6   39.27     -.6   39.12
       0   39.12      .4   37.42     3.2   37.02       5   37.02     8.3   37.52
     8.8   39.12     9.8   39.12      11   38.12      21   38.12
#Mann= 3 , 0 , 0
   -14.2    .035       0     -.6    .035       0     8.8    .035       0
Levee=-1,-.6,40,-1,8.8,40,,
#XS Ineff= 2 , 0
       0     -.6   39.27     8.8       0   39.12
Permanent Ineff=
       F       F
Bank Sta=-.6,8.8
XS Rating Curve= 0
Exp/Cntr=.3,.1

Type RM Length L Ch R = 1 ,58.00   ,8,8,8
BEGIN DESCRIPTION:
1.008
END DESCRIPTION:
#Sta/Elev= 19
   -13.4   36.92    -3.4   36.92    -1.8   38.42       0   38.42      .6   37.22
     4.2   37.22     4.2   36.32    5.25   36.32    5.25   37.22    5.75   37.22
    5.75   36.32     6.8   36.82     6.8   37.22    11.6   37.22    11.9   38.12
    12.1   38.12    13.1   38.52    16.1   38.82    26.1   38.82
#Mann= 3 , 0 , 0
   -13.4    .035       0       0    .035       0    16.1    .035       0
Levee=-1,0,40,-1,16.1,40,,
#XS Ineff= 2 , 0
       0       0   38.42    16.1       0   38.82
Permanent Ineff=
       F       F
Bank Sta=0,16.1
XS Rating Curve= 0
Exp/Cntr=.3,.1

Type RM Length L Ch R = 1 ,50.00   ,44,44,44
BEGIN DESCRIPTION:
1
END DESCRIPTION:
#Sta/Elev= 17
   -13.7   37.51    -3.7   37.51      -2   38.81      -1   38.81     -.3   38.51
       0   37.71     5.5   37.21     6.2   36.11     9.7   36.11    10.2   37.71
    10.5   37.71    11.2   38.01    11.4   37.81    16.4   37.81    19.4   39.41
    22.4   41.01    25.4   42.61
#Mann= 3 , 0 , 0
   -13.7    .035       0      -1    .035       0    11.2    .035       0
Levee=-1,-1,40,-1,11.2,40,,
#XS Ineff= 2 , 0
       0      -1   38.81    11.2       0   38.01
Permanent Ineff=
       F       F
Bank Sta=-1,11.2
XS Rating Curve= 0
Exp/Cntr=.3,.1

Type RM Length L Ch R = 1 ,6.00    ,6,6,6
BEGIN DESCRIPTION:
0.006
END DESCRIPTION:
#Sta/Elev= 18
   -13.7    36.8    -3.7    36.8      -2    38.1      -1    38.1     -.3    37.8
       0      38     5.5    36.5     6.2      36     9.7      36    10.2    37.6
    10.5    37.6    10.8    37.9    11.2    37.9    11.4    37.7    16.4    37.7
    19.4    39.3    22.4    40.9    25.4    42.5
#Mann= 3 , 0 , 0
   -13.7    .035       0      -1    .035       0    10.8    .035       0
Levee=-1,-1,40,-1,10.8,40,,
#XS Ineff= 2 , 0
       0      -1    38.1    10.8       0    37.9
Permanent Ineff=
       F       F
Bank Sta=-1,10.8
XS Rating Curve= 0
Exp/Cntr=.3,.1

Type RM Length L Ch R = 1 ,0.00    ,0,0,0
BEGIN DESCRIPTION:
0
END DESCRIPTION:
#Sta/Elev= 10
     -10   36.91       0   36.91       1   35.31     6.8   35.31     7.3   37.01
     7.5   37.01     8.2   37.31    11.2   38.51    14.2   39.71    17.2   40.91
#Mann= 3 , 0 , 0
     -10    .035       0       0    .035       0     7.3    .035       0
Levee=-1,0,40,-1,7.3,37.01,,
#XS Ineff= 2 , 0
               0   36.91     7.3           37.01
Permanent Ineff=
       F       F
Bank Sta=0,7.3
XS Rating Curve= 0
Exp/Cntr=.3,.1

Chan Stop Cuts=-1