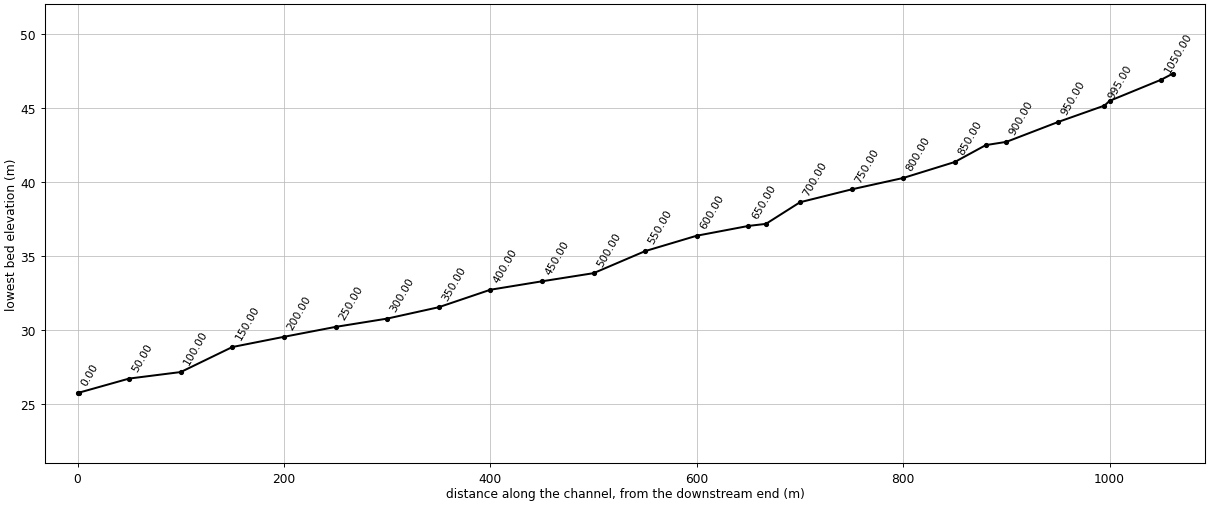
--- ywc.prj (project) ---

Proj Title=yongwa-ch
Current Plan=p01
Default Exp/Contr=.3,.1
SI Units
Geom File=g01
Flow File=f01
Plan File=p01
Y Axis Title=Elevation
X Axis Title(PF)=Main Channel Distance
X Axis Title(XS)=Station
BEGIN DESCRIPTION:
           BACK WATER COMPUTATION
      APPLICATION OF HEC-2 BY Samju Construction Engineering
      ¿ë¿ÍÃµ(¿ËÃµÀ¾): 30,50,80,100,150³âºóµµ °³¼öÀü
END DESCRIPTION:
DSS Export Rating Curves= 0
DSS Export Rating Curve Sorted= 0
DSS Export Volume Flow Curves= 0
DXF OffsetX= 0
DXF OffsetY= 0
DXF ScaleX= 1
DXF ScaleY= 10

--- ywc.p01 (plan) ---

Plan Title=Imported Plan 01
Version=Version 3.0.1  Mar 2001
Short Identifier=Imported Pla
Geom File=g01
Flow File=f01
Subcritical Flow
K Sum by GR= 0
Std Step Tol= 0.003
Critical Tol= 0.003
Num of Std Step Trials= 20
Max Error Tol= 0.1
Flow Tol Ratio= 0.001
Split Flow NTrial= 30
Split Flow Tol= 0.02
Split Flow Ratio= 0.02
Log Output Level= 0
Friction Slope Method= 1
Unsteady Friction Slope Method= 2
Parabolic Critical Depth
Global Vel Dist= 0 , 0 , 0
Global Log Level= 0
CheckData=True
Encroach Param=-1 ,0,0, 0
Computation Interval=1HOUR
Output Interval=1HOUR
Run HTab= 0
Run UNet= 0
Run PostProcess= 0
UNET Theta= 1
UNET ZTol= 0.02
UNET ZSATol= 0.1
UNET MxIter= 20
UNET MaxInSteps= 20
UNET DtIC= 0
UNET DtMin= 0
UNET MaxCRTS= 20
UNET WFStab= 2
UNET SFStab= 1
UNET WFX= 1
UNET SFX= 1
UNET Convert EG Bridges=-1
UNET Use Existing IB Tables=-1
Instantaneous Interval=1HOUR
Write IC File= 0
Write Velocity= 0
Write Detailed= 0

--- ywc.f01 (steady flow) ---

Flow Title=Imported Flow 01
Version=Version 3.0.1  Mar 2001
Number of Profiles= 5
Profile Names=10YR,20YR,30YR,50YR,80YR
River Rch & RM=RIVER-1,Reach-1         ,21.011
   14.68   16.18   17.05   18.15   19.16
River Rch & RM=youngwa,youngwa         ,1061.00
   14.68   16.18   17.05   18.15   19.16
Boundary for River Rch & Prof#=youngwa,youngwa         , 1
Up Type= 0
Dn Type= 3
Dn Slope=.0205
Boundary for River Rch & Prof#=youngwa,youngwa         , 2
Up Type= 0
Dn Type= 3
Dn Slope=.0205
Boundary for River Rch & Prof#=youngwa,youngwa         , 3
Up Type= 0
Dn Type= 3
Dn Slope=.0205
Boundary for River Rch & Prof#=youngwa,youngwa         , 4
Up Type= 0
Dn Type= 3
Dn Slope=.0205
Boundary for River Rch & Prof#=youngwa,youngwa         , 5
Up Type= 0
Dn Type= 3
Dn Slope=.0205
DSS Import GetInterval= 0
DSS Import GetPeak= 0
DSS Import FillOption= 0

--- ywc.g01 (geometry) ---

Geom Title=Imported Geom 01
Version=Version 3.0.1  Mar 2001

River Reach=youngwa         ,youngwa
Reach XY= 2
              .5             .95              .5             .05

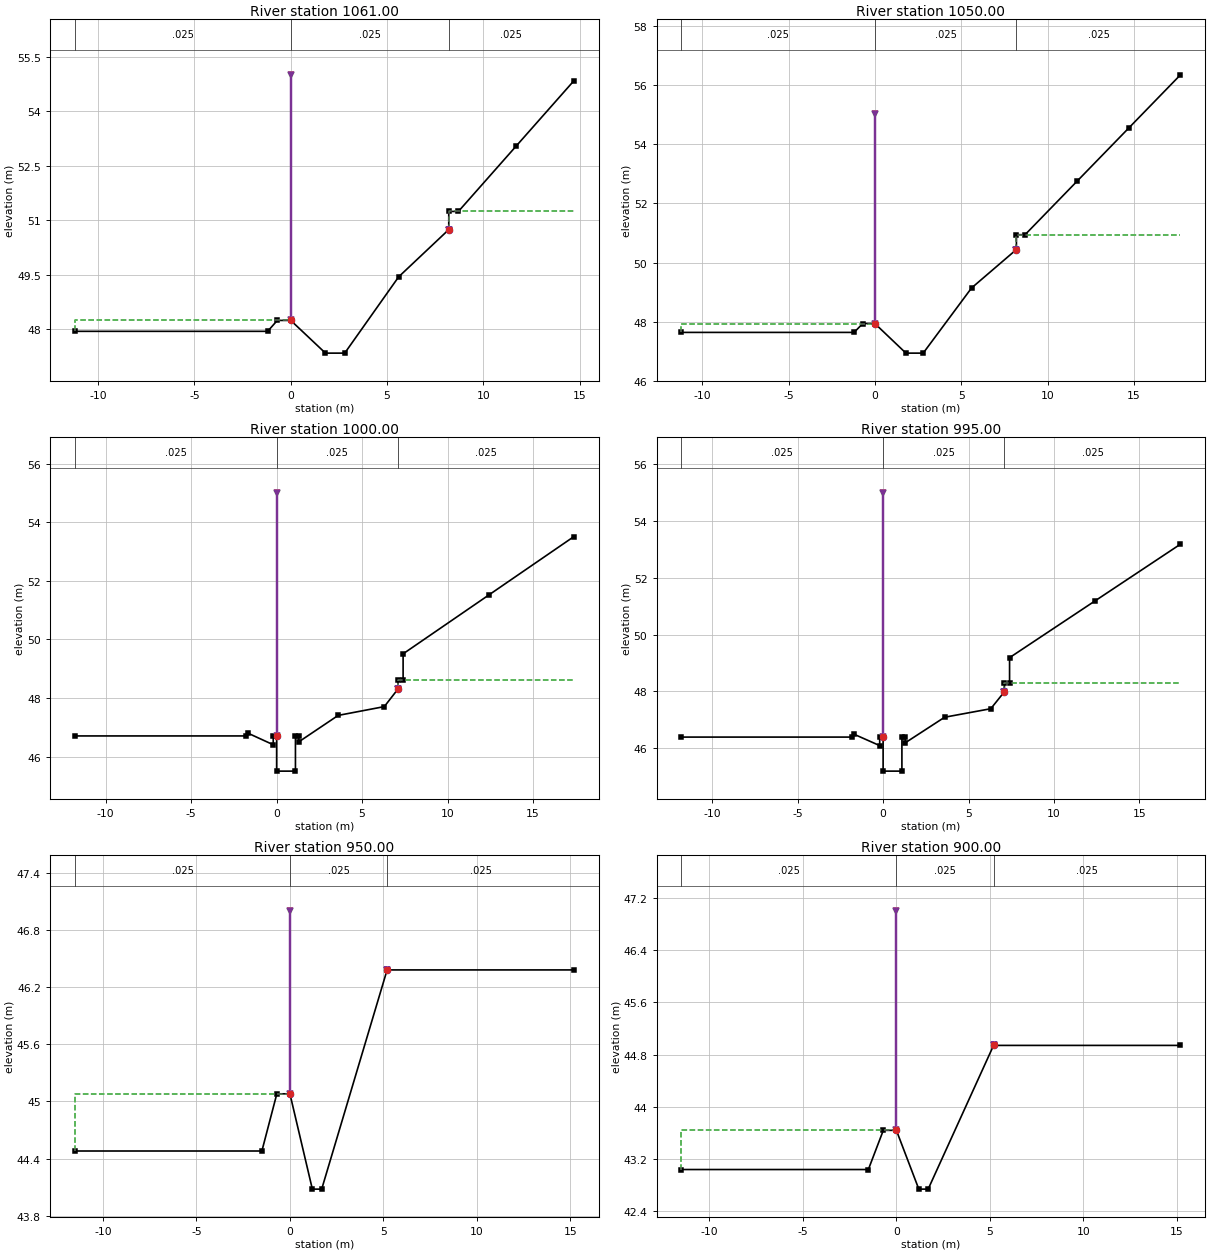
Type RM Length L Ch R = 1 ,1061.00 ,11,11,11
BEGIN DESCRIPTION:
21.011
END DESCRIPTION:
#Sta/Elev= 12
   -11.2   47.94    -1.2   47.94     -.7   48.24       0   48.24     1.8   47.34
     2.8   47.34     5.6   49.44     8.2   50.74     8.2   51.24     8.7   51.24
    11.7   53.04    14.7   54.84
#Mann= 3 , 0 , 0
   -11.2    .025       0       0    .025       0     8.2    .025       0
Levee=-1,0,55,-1,8.2,50.74,,
#XS Ineff= 2 , 0
               0   48.24     8.2           51.24
Permanent Ineff=
       F       F
Bank Sta=0,8.2
XS Rating Curve= 0
Exp/Cntr=.3,.1

Type RM Length L Ch R = 1 ,1050.00 ,50,50,50
BEGIN DESCRIPTION:
21
END DESCRIPTION:
#Sta/Elev= 13
   -11.2   47.64    -1.2   47.64     -.7   47.94       0   47.94     1.8   46.94
     2.8   46.94     5.6   49.14     8.2   50.44     8.2   50.94     8.7   50.94
    11.7   52.74    14.7   54.54    17.7   56.34
#Mann= 3 , 0 , 0
   -11.2    .025       0       0    .025       0     8.2    .025       0
Levee=-1,0,55,-1,8.2,50.44,,
#XS Ineff= 2 , 0
               0   47.94     8.2           50.94
Permanent Ineff=
       F       F
Bank Sta=0,8.2
XS Rating Curve= 0
Exp/Cntr=.3,.1

Type RM Length L Ch R = 1 ,1000.00 ,5,5,5
BEGIN DESCRIPTION:
20
END DESCRIPTION:
#Sta/Elev= 19
   -11.8   46.71    -1.8   46.71    -1.7   46.81     -.2   46.41     -.2   46.71
       0   46.71       0   45.51     1.1   45.51     1.1   46.71     1.3   46.71
     1.3   46.51     3.6   47.41     6.3   47.71     7.1   48.31     7.1   48.61
     7.4   48.61     7.4   49.51    12.4   51.51    17.4   53.51
#Mann= 3 , 0 , 0
   -11.8    .025       0       0    .025       0     7.1    .025       0
Levee=-1,0,55,-1,7.1,48.31,,
#XS Ineff= 2 , 0
               0   46.71     7.1           48.61
Permanent Ineff=
       F       F
Bank Sta=0,7.1
XS Rating Curve= 0
Exp/Cntr=.3,.1

Type RM Length L Ch R = 1 ,995.00  ,45,45,45
BEGIN DESCRIPTION:
19.045
END DESCRIPTION:
#Sta/Elev= 19
   -11.8   46.39    -1.8   46.39    -1.7   46.49     -.2   46.09     -.2   46.39
       0   46.39       0   45.19     1.1   45.19     1.1   46.39     1.3   46.39
     1.3   46.19     3.6   47.09     6.3   47.39     7.1   47.99     7.1   48.29
     7.4   48.29     7.4   49.19    12.4   51.19    17.4   53.19
#Mann= 3 , 0 , 0
   -11.8    .025       0       0    .025       0     7.1    .025       0
Levee=-1,0,55,-1,7.1,47.99,,
#XS Ineff= 2 , 0
               0   46.39     7.1           48.29
Permanent Ineff=
       F       F
Bank Sta=0,7.1
XS Rating Curve= 0
Exp/Cntr=.3,.1

Type RM Length L Ch R = 1 ,950.00  ,50,50,50
BEGIN DESCRIPTION:
19
END DESCRIPTION:
#Sta/Elev= 8
   -11.5   44.48    -1.5   44.48     -.7   45.08       0   45.08     1.2   44.08
     1.7   44.08     5.2   46.38    15.2   46.38
#Mann= 3 , 0 , 0
   -11.5    .025       0       0    .025       0     5.2    .025       0
Levee=-1,0,47,-1,5.2,46.38,,
#XS Ineff= 2 , 0
               0   45.08     5.2           46.38
Permanent Ineff=
       F       F
Bank Sta=0,5.2
XS Rating Curve= 0
Exp/Cntr=.3,.1

Type RM Length L Ch R = 1 ,900.00  ,20,20,20
BEGIN DESCRIPTION:
18
END DESCRIPTION:
#Sta/Elev= 8
   -11.5   43.04    -1.5   43.04     -.7   43.64       0   43.64     1.2   42.74
     1.7   42.74     5.2   44.94    15.2   44.94
#Mann= 3 , 0 , 0
   -11.5    .025       0       0    .025       0     5.2    .025       0
Levee=-1,0,47,-1,5.2,44.94,,
#XS Ineff= 2 , 0
               0   43.64     5.2           44.94
Permanent Ineff=
       F       F
Bank Sta=0,5.2
XS Rating Curve= 0
Exp/Cntr=.3,.1

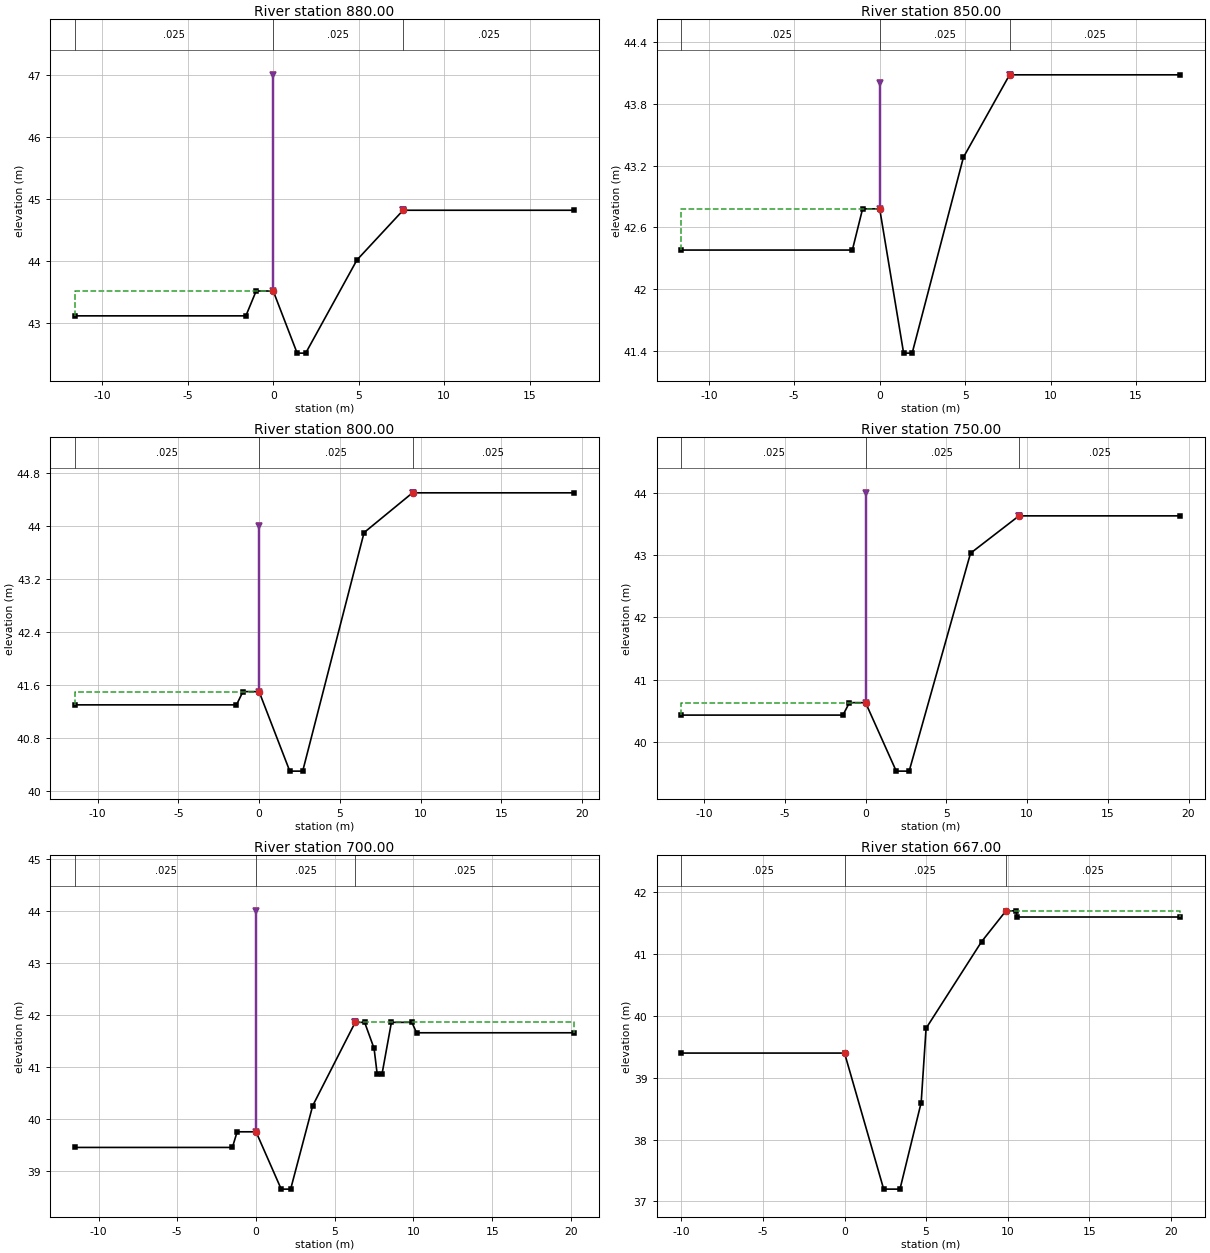
Type RM Length L Ch R = 1 ,880.00  ,30,30,30
BEGIN DESCRIPTION:
17.03
END DESCRIPTION:
#Sta/Elev= 9
   -11.6   43.12    -1.6   43.12      -1   43.52       0   43.52     1.4   42.52
     1.9   42.52     4.9   44.02     7.6   44.82    17.6   44.82
#Mann= 3 , 0 , 0
   -11.6    .025       0       0    .025       0     7.6    .025       0
Levee=-1,0,47,-1,7.6,44.82,,
#XS Ineff= 2 , 0
               0   43.52     7.6           44.82
Permanent Ineff=
       F       F
Bank Sta=0,7.6
XS Rating Curve= 0
Exp/Cntr=.3,.1

Type RM Length L Ch R = 1 ,850.00  ,50,50,50
BEGIN DESCRIPTION:
17
END DESCRIPTION:
#Sta/Elev= 9
   -11.6   42.38    -1.6   42.38      -1   42.78       0   42.78     1.4   41.38
     1.9   41.38     4.9   43.28     7.6   44.08    17.6   44.08
#Mann= 3 , 0 , 0
   -11.6    .025       0       0    .025       0     7.6    .025       0
Levee=-1,0,44,-1,7.6,44.08,,
#XS Ineff= 2 , 0
               0   42.78     7.6           44.08
Permanent Ineff=
       F       F
Bank Sta=0,7.6
XS Rating Curve= 0
Exp/Cntr=.3,.1

Type RM Length L Ch R = 1 ,800.00  ,50,50,50
BEGIN DESCRIPTION:
16
END DESCRIPTION:
#Sta/Elev= 9
   -11.4    41.3    -1.4    41.3      -1    41.5       0    41.5     1.9    40.3
     2.7    40.3     6.5    43.9     9.5    44.5    19.5    44.5
#Mann= 3 , 0 , 0
   -11.4    .025       0       0    .025       0     9.5    .025       0
Levee=-1,0,44,-1,9.5,44.5,,
#XS Ineff= 2 , 0
               0    41.5     9.5            44.5
Permanent Ineff=
       F       F
Bank Sta=0,9.5
XS Rating Curve= 0
Exp/Cntr=.3,.1

Type RM Length L Ch R = 1 ,750.00  ,50,50,50
BEGIN DESCRIPTION:
15
END DESCRIPTION:
#Sta/Elev= 9
   -11.4   40.43    -1.4   40.43      -1   40.63       0   40.63     1.9   39.53
     2.7   39.53     6.5   43.03     9.5   43.63    19.5   43.63
#Mann= 3 , 0 , 0
   -11.4    .025       0       0    .025       0     9.5    .025       0
Levee=-1,0,44,-1,9.5,43.63,,
#XS Ineff= 2 , 0
               0   40.63     9.5           43.63
Permanent Ineff=
       F       F
Bank Sta=0,9.5
XS Rating Curve= 0
Exp/Cntr=.3,.1

Type RM Length L Ch R = 1 ,700.00  ,33,33,33
BEGIN DESCRIPTION:
14
END DESCRIPTION:
#Sta/Elev= 16
   -11.5   39.46    -1.5   39.46    -1.2   39.76       0   39.76     1.6   38.66
     2.2   38.66     3.6   40.26     6.3   41.86     6.9   41.86     7.5   41.36
     7.7   40.86       8   40.86     8.6   41.86     9.9   41.86    10.2   41.66
    20.2   41.66
#Mann= 3 , 0 , 0
   -11.5    .025       0       0    .025       0     6.3    .025       0
Levee=-1,0,44,-1,6.3,41.86,,
#XS Ineff= 2 , 0
       0       0   39.76     6.3       0   41.86
Permanent Ineff=
       F       F
Bank Sta=0,6.3
XS Rating Curve= 0
Exp/Cntr=.3,.1

Type RM Length L Ch R = 1 ,667.00  ,17,17,17
BEGIN DESCRIPTION:
13.017
END DESCRIPTION:
#Sta/Elev= 11
     -10    39.4       0    39.4     2.4    37.2     3.4    37.2     4.7    38.6
       5    39.8     8.4    41.2     9.9    41.7    10.5    41.7    10.6    41.6
    20.6    41.6
#Mann= 3 , 0 , 0
     -10    .025       0       0    .025       0     9.9    .025       0
#XS Ineff= 2 , 0
               0    39.4     9.9            41.7
Permanent Ineff=
       F       F
Bank Sta=0,9.9
XS Rating Curve= 0
Exp/Cntr=.3,.1

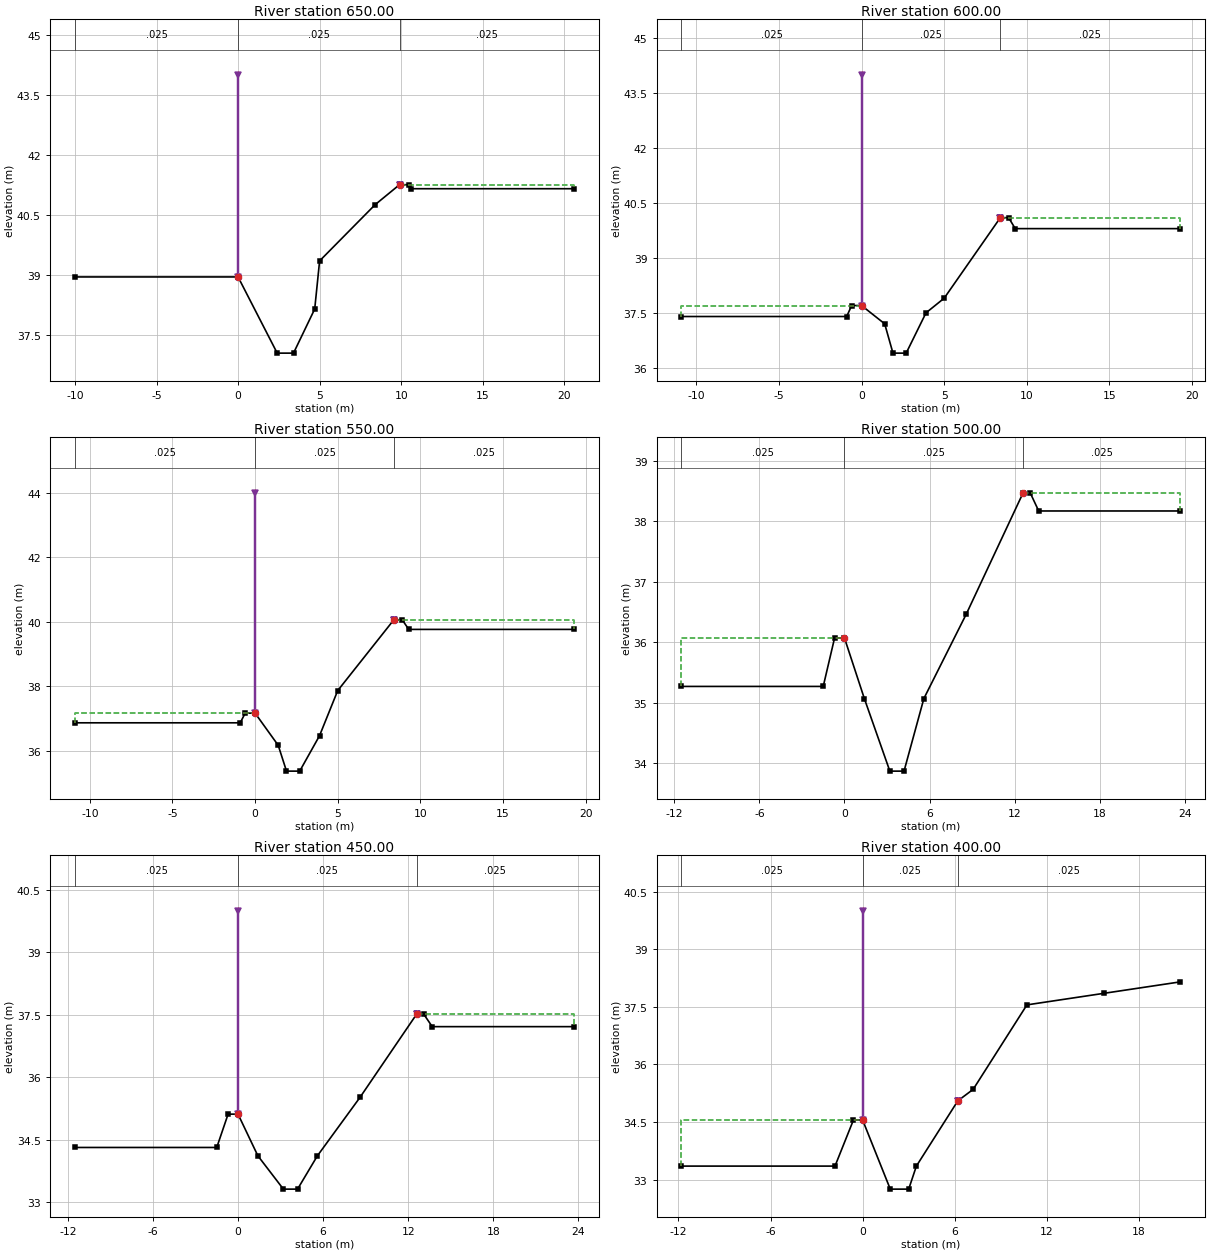
Type RM Length L Ch R = 1 ,650.00  ,50,50,50
BEGIN DESCRIPTION:
13
END DESCRIPTION:
#Sta/Elev= 11
     -10   38.96       0   38.96     2.4   37.06     3.4   37.06     4.7   38.16
       5   39.36     8.4   40.76     9.9   41.26    10.5   41.26    10.6   41.16
    20.6   41.16
#Mann= 3 , 0 , 0
     -10    .025       0       0    .025       0     9.9    .025       0
Levee=-1,0,44,-1,9.9,41.26,,
#XS Ineff= 2 , 0
               0   38.96     9.9           41.26
Permanent Ineff=
       F       F
Bank Sta=0,9.9
XS Rating Curve= 0
Exp/Cntr=.3,.1

Type RM Length L Ch R = 1 ,600.00  ,50,50,50
BEGIN DESCRIPTION:
12
END DESCRIPTION:
#Sta/Elev= 13
   -10.9    37.4     -.9    37.4     -.6    37.7       0    37.7     1.4    37.2
     1.9    36.4     2.7    36.4     3.9    37.5       5    37.9     8.4    40.1
     8.9    40.1     9.3    39.8    19.3    39.8
#Mann= 3 , 0 , 0
   -10.9    .025       0       0    .025       0     8.4    .025       0
Levee=-1,0,44,-1,8.4,40.1,,
#XS Ineff= 2 , 0
               0    37.7     8.4            40.1
Permanent Ineff=
       F       F
Bank Sta=0,8.4
XS Rating Curve= 0
Exp/Cntr=.3,.1

Type RM Length L Ch R = 1 ,550.00  ,50,50,50
BEGIN DESCRIPTION:
11
END DESCRIPTION:
#Sta/Elev= 13
   -10.9   36.86     -.9   36.86     -.6   37.16       0   37.16     1.4   36.16
     1.9   35.36     2.7   35.36     3.9   36.46       5   37.86     8.4   40.06
     8.9   40.06     9.3   39.76    19.3   39.76
#Mann= 3 , 0 , 0
   -10.9    .025       0       0    .025       0     8.4    .025       0
Levee=-1,0,44,-1,8.4,40.06,,
#XS Ineff= 2 , 0
               0   37.16     8.4           40.06
Permanent Ineff=
       F       F
Bank Sta=0,8.4
XS Rating Curve= 0
Exp/Cntr=.3,.1

Type RM Length L Ch R = 1 ,500.00  ,50,50,50
BEGIN DESCRIPTION:
10
END DESCRIPTION:
#Sta/Elev= 13
   -11.5   35.27    -1.5   35.27     -.7   36.07       0   36.07     1.4   35.07
     3.2   33.87     4.2   33.87     5.6   35.07     8.6   36.47    12.6   38.47
    13.1   38.47    13.7   38.17    23.7   38.17
#Mann= 3 , 0 , 0
   -11.5    .025       0       0    .025       0    12.6    .025       0
#XS Ineff= 2 , 0
               0   36.07    12.6           38.47
Permanent Ineff=
       F       F
Bank Sta=0,12.6
XS Rating Curve= 0
Exp/Cntr=.3,.1

Type RM Length L Ch R = 1 ,450.00  ,50,50,50
BEGIN DESCRIPTION:
9
END DESCRIPTION:
#Sta/Elev= 13
   -11.5   34.32    -1.5   34.32     -.7   35.12       0   35.12     1.4   34.12
     3.2   33.32     4.2   33.32     5.6   34.12     8.6   35.52    12.6   37.52
    13.1   37.52    13.7   37.22    23.7   37.22
#Mann= 3 , 0 , 0
   -11.5    .025       0       0    .025       0    12.6    .025       0
Levee=-1,0,40,-1,12.6,37.52,,
#XS Ineff= 2 , 0
       0       0   35.12    12.6       0   37.52
Permanent Ineff=
       F       F
Bank Sta=0,12.6
XS Rating Curve= 0
Exp/Cntr=.3,.1

Type RM Length L Ch R = 1 ,400.00  ,50,50,50
BEGIN DESCRIPTION:
8
END DESCRIPTION:
#Sta/Elev= 12
   -11.8   33.35    -1.8   33.35     -.6   34.55       0   34.55     1.8   32.75
       3   32.75     3.5   33.35     6.2   35.05     7.2   35.35    10.7   37.55
    15.7   37.85    20.7   38.15
#Mann= 3 , 0 , 0
   -11.8    .025       0       0    .025       0     6.2    .025       0
Levee=-1,0,40,-1,6.2,35.05,,
#XS Ineff= 2 , 0
               0   34.55     6.2           35.05
Permanent Ineff=
       F       F
Bank Sta=0,6.2
XS Rating Curve= 0
Exp/Cntr=.3,.1

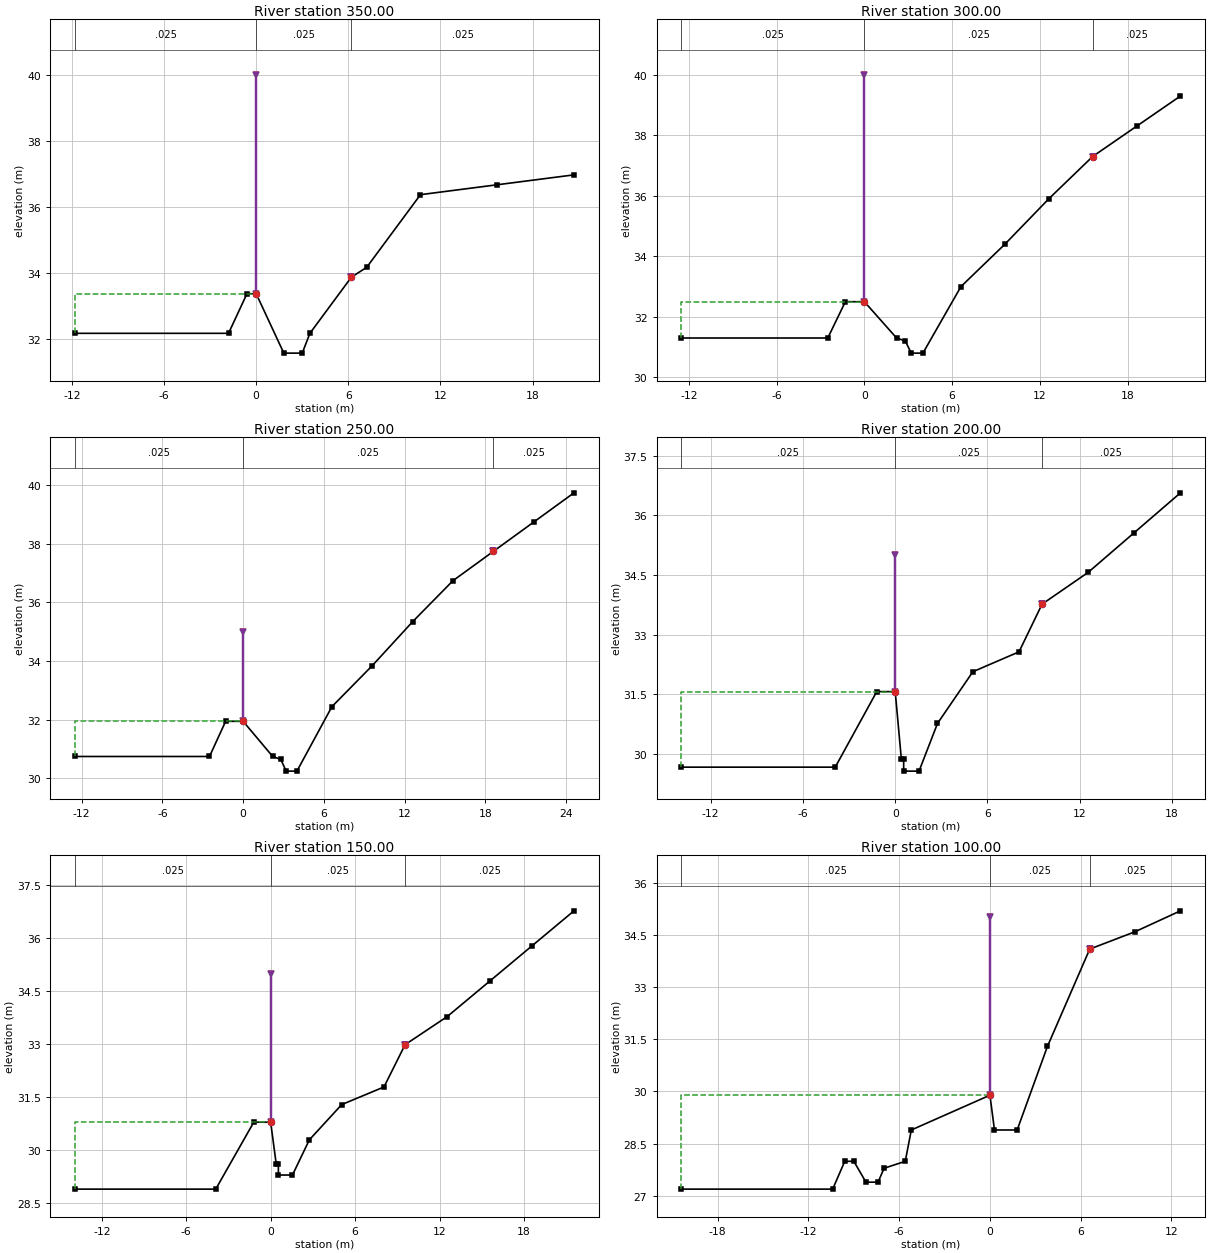
Type RM Length L Ch R = 1 ,350.00  ,50,50,50
BEGIN DESCRIPTION:
7
END DESCRIPTION:
#Sta/Elev= 12
   -11.8   32.17    -1.8   32.17     -.6   33.37       0   33.37     1.8   31.57
       3   31.57     3.5   32.17     6.2   33.87     7.2   34.17    10.7   36.37
    15.7   36.67    20.7   36.97
#Mann= 3 , 0 , 0
   -11.8    .025       0       0    .025       0     6.2    .025       0
Levee=-1,0,40,-1,6.2,33.87,,
#XS Ineff= 2 , 0
               0   33.37     6.2           33.87
Permanent Ineff=
       F       F
Bank Sta=0,6.2
XS Rating Curve= 0
Exp/Cntr=.3,.1

Type RM Length L Ch R = 1 ,300.00  ,50,50,50
BEGIN DESCRIPTION:
6
END DESCRIPTION:
#Sta/Elev= 14
   -12.5    31.3    -2.5    31.3    -1.3    32.5       0    32.5     2.2    31.3
     2.8    31.2     3.2    30.8       4    30.8     6.6      33     9.6    34.4
    12.6    35.9    15.6    37.3    18.6    38.3    21.6    39.3
#Mann= 3 , 0 , 0
   -12.5    .025       0       0    .025       0    15.6    .025       0
Levee=-1,0,40,-1,15.6,37.3,,
#XS Ineff= 2 , 0
               0    32.5    15.6            37.3
Permanent Ineff=
       F       F
Bank Sta=0,15.6
XS Rating Curve= 0
Exp/Cntr=.3,.1

Type RM Length L Ch R = 1 ,250.00  ,50,50,50
BEGIN DESCRIPTION:
5
END DESCRIPTION:
#Sta/Elev= 15
   -12.5   30.74    -2.5   30.74    -1.3   31.94       0   31.94     2.2   30.74
     2.8   30.64     3.2   30.24       4   30.24     6.6   32.44     9.6   33.84
    12.6   35.34    15.6   36.74    18.6   37.74    21.6   38.74    24.6   39.74
#Mann= 3 , 0 , 0
   -12.5    .025       0       0    .025       0    18.6    .025       0
Levee=-1,0,35,-1,18.6,37.74,,
#XS Ineff= 2 , 0
               0   31.94    18.6           37.74
Permanent Ineff=
       F       F
Bank Sta=0,18.6
XS Rating Curve= 0
Exp/Cntr=.3,.1

Type RM Length L Ch R = 1 ,200.00  ,50,50,50
BEGIN DESCRIPTION:
4
END DESCRIPTION:
#Sta/Elev= 15
   -13.9   29.67    -3.9   29.67    -1.2   31.57       0   31.57      .4   29.87
     .55   29.87     .55   29.57    1.55   29.57    2.75   30.77    5.05   32.07
    8.05   32.57    9.55   33.77   12.55   34.57   15.55   35.57   18.55   36.57
#Mann= 3 , 0 , 0
   -13.9    .025       0       0    .025       0    9.55    .025       0
Levee=-1,0,35,-1,9.55,33.77,,
#XS Ineff= 2 , 0
               0   31.57    9.55           33.77
Permanent Ineff=
       F       F
Bank Sta=0,9.55
XS Rating Curve= 0
Exp/Cntr=.3,.1

Type RM Length L Ch R = 1 ,150.00  ,50,50,50
BEGIN DESCRIPTION:
3
END DESCRIPTION:
#Sta/Elev= 16
   -13.9   28.88    -3.9   28.88    -1.2   30.78       0   30.78      .4   29.58
     .55   29.58     .55   29.28    1.55   29.28    2.75   30.28    5.05   31.28
    8.05   31.78    9.55   32.98   12.55   33.78   15.55   34.78   18.55   35.78
   21.55   36.78
#Mann= 3 , 0 , 0
   -13.9    .025       0       0    .025       0    9.55    .025       0
Levee=-1,0,35,-1,9.55,32.98,,
#XS Ineff= 2 , 0
               0   30.78    9.55           32.98
Permanent Ineff=
       F       F
Bank Sta=0,9.55
XS Rating Curve= 0
Exp/Cntr=.3,.1

Type RM Length L Ch R = 1 ,100.00  ,50,50,50
BEGIN DESCRIPTION:
2
END DESCRIPTION:
#Sta/Elev= 16
   -20.4   27.19   -10.4   27.19    -9.6   27.99      -9   27.99    -8.2   27.39
    -7.4   27.39      -7   27.79    -5.6   27.99    -5.2   28.89       0   29.89
      .3   28.89     1.8   28.89     3.8   31.29     6.6   34.09     9.6   34.59
    12.6   35.19
#Mann= 3 , 0 , 0
   -20.4    .025       0       0    .025       0     6.6    .025       0
Levee=-1,0,35,-1,6.6,34.09,,
#XS Ineff= 2 , 0
               0   29.89     6.6           34.09
Permanent Ineff=
       F       F
Bank Sta=0,6.6
XS Rating Curve= 0
Exp/Cntr=.3,.1

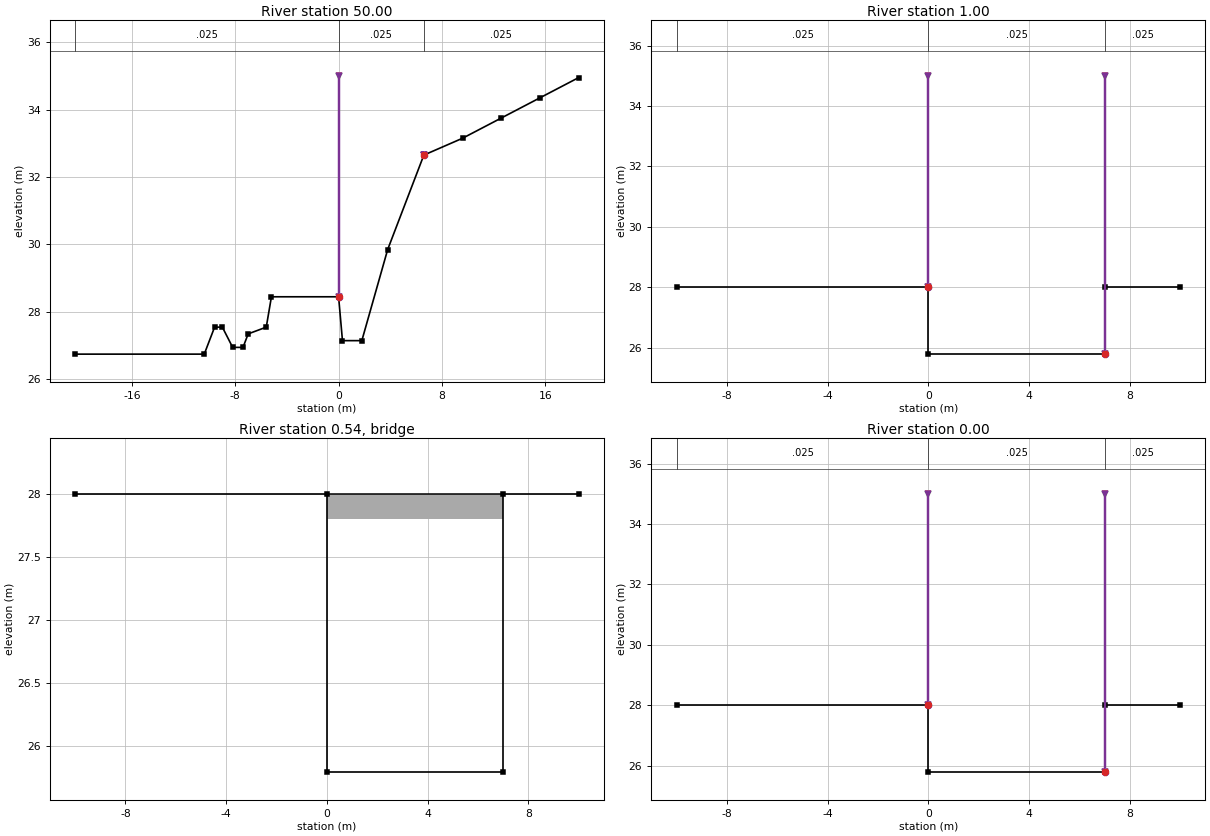
Type RM Length L Ch R = 1 ,50.00   ,49,49,49
BEGIN DESCRIPTION:
1
END DESCRIPTION:
#Sta/Elev= 18
   -20.4   26.75   -10.4   26.75    -9.6   27.55      -9   27.55    -8.2   26.95
    -7.4   26.95      -7   27.35    -5.6   27.55    -5.2   28.45       0   28.45
      .3   27.15     1.8   27.15     3.8   29.85     6.6   32.65     9.6   33.15
    12.6   33.75    15.6   34.35    18.6   34.95
#Mann= 3 , 0 , 0
   -20.4    .025       0       0    .025       0     6.6    .025       0
Levee=-1,0,35,-1,6.6,32.65,,
#XS Ineff= 2 , 0
       0       0   28.45     6.6       0   32.65
Permanent Ineff=
       F       F
Bank Sta=0,6.6
XS Rating Curve= 0
Exp/Cntr=.3,.1

Type RM Length L Ch R = 1 ,1.00    ,1,1,1
BEGIN DESCRIPTION:
0.001
END DESCRIPTION:
#Sta/Elev= 6
     -10      28       0      28       0   25.79       7   25.79       7      28
      10      28
#Mann= 3 , 0 , 0
     -10    .025       0       0    .025       0       7    .025       0
Levee=-1,0,35,-1,7,35,,
Bank Sta=0,7
XS Rating Curve= 0
Exp/Cntr=.3,.1

Type RM Length L Ch R = 3 ,0.54    ,,,
BEGIN DESCRIPTION:
0.0005
END DESCRIPTION:
Bridge Culvert--1,0,-1,-1, 0
Deck Dist Width WeirC Skew NumUp NumDn MinLoCord MaxHiCord MaxSubmerge Is_Ogee
.01,.9,1.44,0, 2, 2, , , .95, 0, 0,0,,
       0       7
      28      28
    27.8    27.8
       0       7
      28      28
    27.8    27.8
BR Coef=-1 , 1 , 0 ,, 0 ,,,.8,-1,1.2,0,
WSPro=,,,, 1 ,,,, 0 ,,,, 0 ,,,,-1 ,-1 ,-1 , 0 , 0 , 0 , 0 , 0
BC Design=,, 0 ,, 0 ,,,,,,

Type RM Length L Ch R = 1 ,0.00    ,0,0,0
BEGIN DESCRIPTION:
0
END DESCRIPTION:
#Sta/Elev= 6
     -10      28       0      28       0   25.79       7   25.79       7      28
      10      28
#Mann= 3 , 0 , 0
     -10    .025       0       0    .025       0       7    .025       0
Levee=-1,0,35,-1,7,35,,
Bank Sta=0,7
XS Rating Curve= 0
Exp/Cntr=.3,.1

Chan Stop Cuts=-1