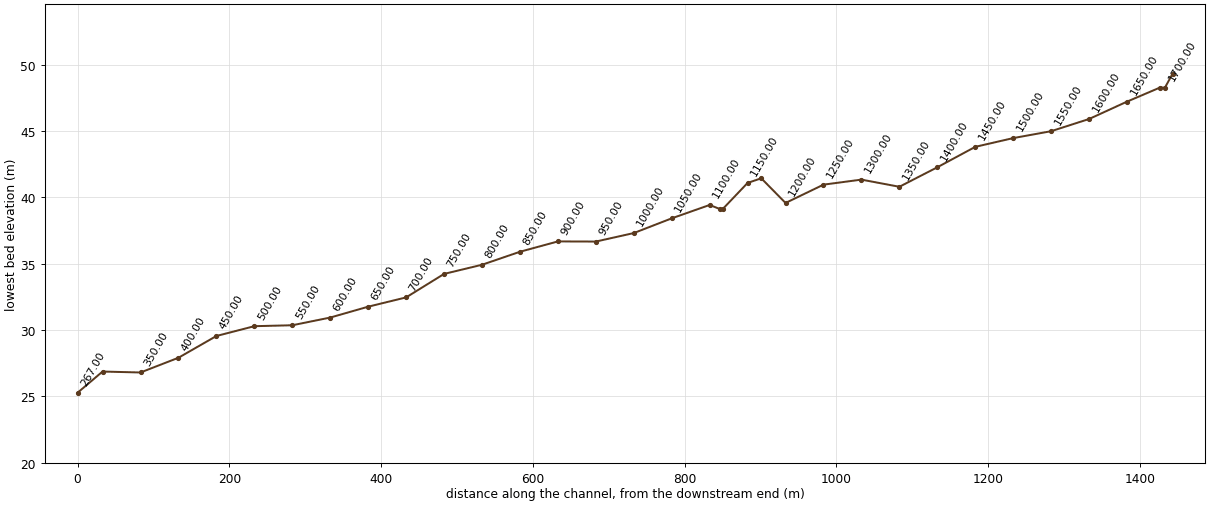
--- jmc.prj (project) ---

Proj Title=zangma-ch
Current Plan=p01
Default Exp/Contr=.3,.1
SI Units
Geom File=g01
Flow File=f01
Plan File=p01
Y Axis Title=Elevation
X Axis Title(PF)=Main Channel Distance
X Axis Title(XS)=Station
BEGIN DESCRIPTION:
           BACK WATER COMPUTATION
      APPLICATION OF HEC-2 BY Samju Construction Engineering
      Àå¸¶Ãµ(¿ËÃµÀ¾): 30,50,80,100,150³âºóµµ °³¼öÀü
END DESCRIPTION:
DSS Export Rating Curves= 0
DSS Export Rating Curve Sorted= 0
DSS Export Volume Flow Curves= 0
DXF OffsetX= 0
DXF OffsetY= 0
DXF ScaleX= 1
DXF ScaleY= 10

--- jmc.p01 (plan) ---

Plan Title=Imported Plan 01
Version=Version 3.0.1  Mar 2001
Short Identifier=Imported Pla
Geom File=g01
Flow File=f01
Subcritical Flow
K Sum by GR= 0
Std Step Tol= 0.003
Critical Tol= 0.003
Num of Std Step Trials= 20
Max Error Tol= 0.1
Flow Tol Ratio= 0.001
Split Flow NTrial= 30
Split Flow Tol= 0.02
Split Flow Ratio= 0.02
Log Output Level= 0
Friction Slope Method= 1
Unsteady Friction Slope Method= 2
Parabolic Critical Depth
Global Vel Dist= 0 , 0 , 0
Global Log Level= 0
CheckData=True
Encroach Param=-1 ,0,0, 0
Computation Interval=1HOUR
Output Interval=1HOUR
Run HTab= 0
Run UNet= 0
Run PostProcess= 0
UNET Theta= 1
UNET ZTol= 0.02
UNET ZSATol= 0.1
UNET MxIter= 20
UNET MaxInSteps= 20
UNET DtIC= 0
UNET DtMin= 0
UNET MaxCRTS= 20
UNET WFStab= 2
UNET SFStab= 1
UNET WFX= 1
UNET SFX= 1
UNET Convert EG Bridges=-1
UNET Use Existing IB Tables=-1
Instantaneous Interval=1HOUR
Write IC File= 0
Write Velocity= 0
Write Detailed= 0

--- jmc.f01 (steady flow) ---

Flow Title=Imported Flow 01
Version=Version 3.0.1  Mar 2001
Number of Profiles= 5
Profile Names=10YR,20YR,30YR,50YR,80YR
River Rch & RM=RIVER-1,Reach-1         ,34.01
   10.29   11.35   11.96   12.74   13.45
River Rch & RM=RIVER-1,Reach-1         ,22
   11.12   12.26   12.93   13.77   14.55
River Rch & RM=jangma,jangma          ,1710.00
   10.29   11.35   11.96   12.74   13.45
River Rch & RM=jangma,jangma          ,1100.00
   11.12   12.26   12.93   13.77   14.55
Boundary for River Rch & Prof#=jangma,jangma          , 1
Up Type= 0
Dn Type= 3
Dn Slope=.0162
Boundary for River Rch & Prof#=jangma,jangma          , 2
Up Type= 0
Dn Type= 3
Dn Slope=.0162
Boundary for River Rch & Prof#=jangma,jangma          , 3
Up Type= 0
Dn Type= 3
Dn Slope=.0162
Boundary for River Rch & Prof#=jangma,jangma          , 4
Up Type= 0
Dn Type= 3
Dn Slope=.0162
Boundary for River Rch & Prof#=jangma,jangma          , 5
Up Type= 0
Dn Type= 3
Dn Slope=.0162
DSS Import GetInterval= 0
DSS Import GetPeak= 0
DSS Import FillOption= 0

--- jmc.g01 (geometry) ---

Geom Title=Imported Geom 01
Version=Version 3.0.1  Mar 2001

River Reach=jangma          ,jangma
Reach XY= 2
              .5             .95              .5             .05

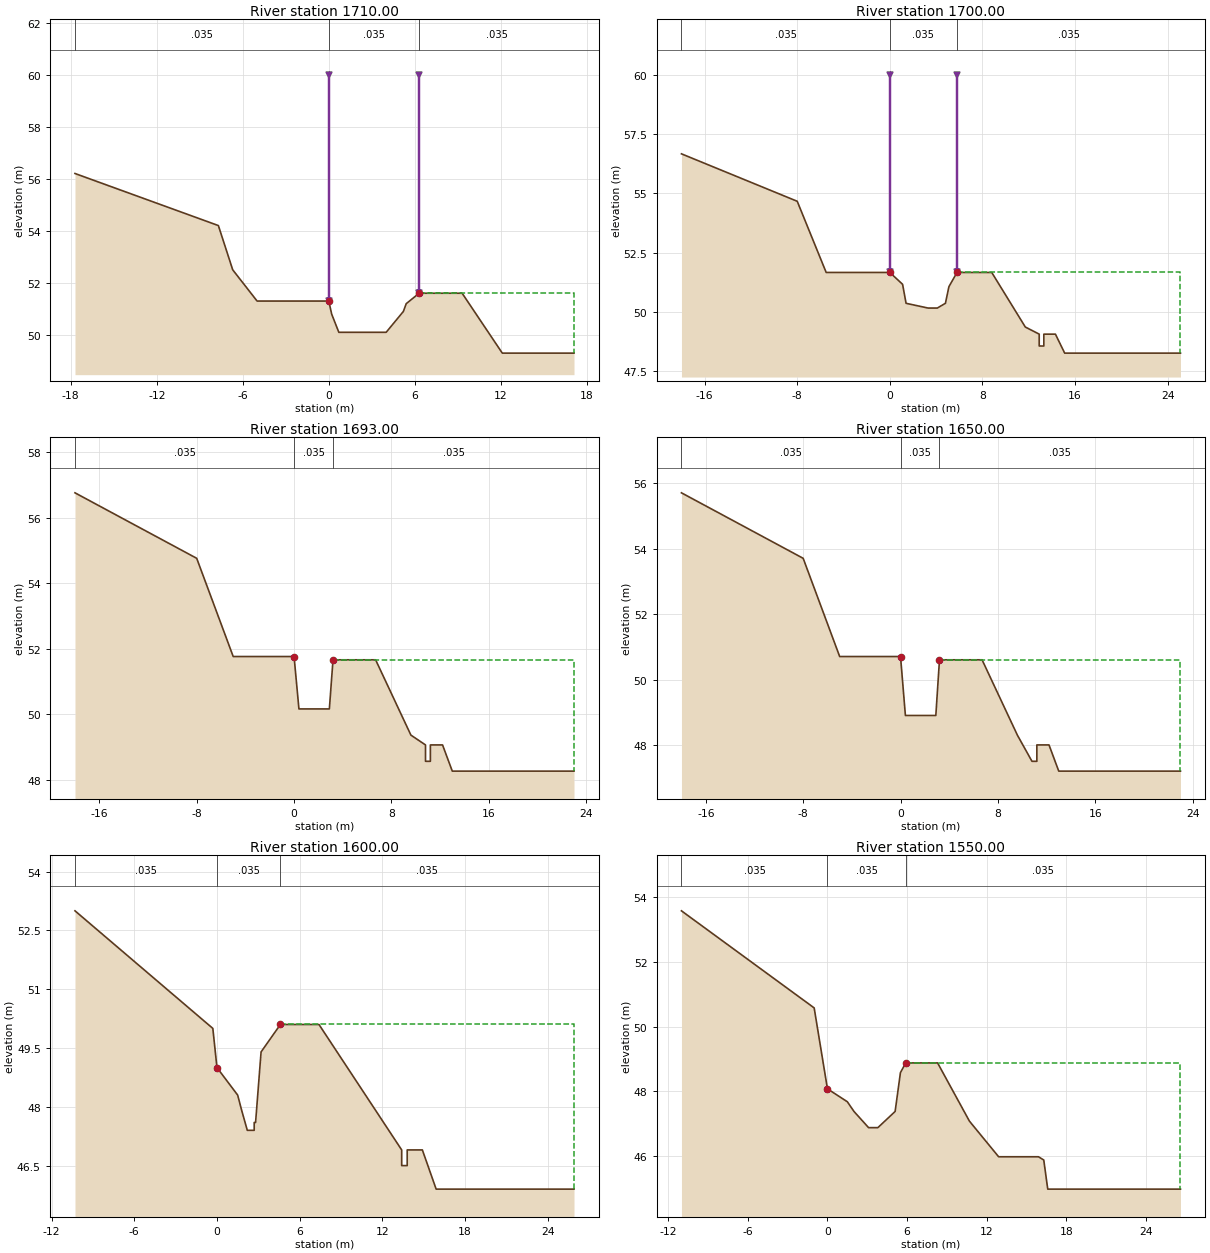
Type RM Length L Ch R = 1 ,1710.00 ,10,10,10
BEGIN DESCRIPTION:
34.01
END DESCRIPTION:
#Sta/Elev= 15
   -17.7   56.21   -12.7   55.21    -7.7   54.21    -6.7   52.51      -5   51.31
       0   51.31      .2   50.81      .7   50.11       4   50.11     5.2   50.91
     5.4   51.21     6.3   51.61     9.3   51.61    12.1   49.31    17.1   49.31
#Mann= 3 , 0 , 0
   -17.7    .035       0       0    .035       0     6.3    .035       0
Levee=-1,0,60,-1,6.3,60,,
#XS Ineff= 2 , 0
               0   51.31     6.3           51.61
Permanent Ineff=
       F       F
Bank Sta=0,6.3
XS Rating Curve= 0
Exp/Cntr=.3,.1

Type RM Length L Ch R = 1 ,1700.00 ,7,7,7
BEGIN DESCRIPTION:
34
END DESCRIPTION:
#Sta/Elev= 21
     -18   56.67     -13   55.67      -8   54.67    -5.5   51.67       0   51.67
     1.1   51.17     1.4   50.37     3.3   50.17     4.1   50.17     4.8   50.37
     5.1   51.07     5.8   51.67     8.8   51.67    11.7   49.37    12.9   49.07
    12.9   48.57    13.3   48.57    13.3   49.07    14.3   49.07    15.1   48.27
    25.1   48.27
#Mann= 3 , 0 , 0
     -18    .035       0       0    .035       0     5.8    .035       0
Levee=-1,0,60,-1,5.8,60,,
#XS Ineff= 2 , 0
               0   51.67     5.8           51.67
Permanent Ineff=
       F       F
Bank Sta=0,5.8
XS Rating Curve= 0
Exp/Cntr=.3,.1

Type RM Length L Ch R = 1 ,1693.00 ,43,43,43
BEGIN DESCRIPTION:
33.043
END DESCRIPTION:
#Sta/Elev= 17
     -18   56.76     -13   55.76      -8   54.76      -5   51.76       0   51.76
      .4   50.16     2.9   50.16     3.2   51.66     6.7   51.66     9.6   49.36
    10.8   49.06    10.8   48.56    11.2   48.56    11.2   49.06    12.2   49.06
      13   48.26      23   48.26
#Mann= 3 , 0 , 0
     -18    .035       0       0    .035       0     3.2    .035       0
#XS Ineff= 2 , 0
               0   51.76     3.2           51.66
Permanent Ineff=
       F       F
Bank Sta=0,3.2
XS Rating Curve= 0
Exp/Cntr=.3,.1

Type RM Length L Ch R = 1 ,1650.00 ,50,50,50
BEGIN DESCRIPTION:
33
END DESCRIPTION:
#Sta/Elev= 16
     -18   55.71     -13   54.71      -8   53.71      -5   50.71       0   50.71
      .4   48.91     2.9   48.91     3.2   50.61     6.7   50.61     9.6   48.31
    10.8   47.51    11.2   47.51    11.2   48.01    12.2   48.01      13   47.21
      23   47.21
#Mann= 3 , 0 , 0
     -18    .035       0       0    .035       0     3.2    .035       0
#XS Ineff= 2 , 0
               0   50.71     3.2           50.61
Permanent Ineff=
       F       F
Bank Sta=0,3.2
XS Rating Curve= 0
Exp/Cntr=.3,.1

Type RM Length L Ch R = 1 ,1600.00 ,50,50,50
BEGIN DESCRIPTION:
32
END DESCRIPTION:
#Sta/Elev= 21
   -10.3      53    -5.3    51.5     -.3      50       0      49     1.5    48.3
     1.8    47.9     2.2    47.4     2.7    47.4     2.7    47.6     2.8    47.6
     3.2    49.4     4.6    50.1     7.4    50.1    10.4    48.5    13.4    46.9
    13.4    46.5    13.8    46.5    13.8    46.9    14.9    46.9    15.9    45.9
    25.9    45.9
#Mann= 3 , 0 , 0
   -10.3    .035       0       0    .035       0     4.6    .035       0
#XS Ineff= 2 , 0
               0      49     4.6            50.1
Permanent Ineff=
       F       F
Bank Sta=0,4.6
XS Rating Curve= 0
Exp/Cntr=.3,.1

Type RM Length L Ch R = 1 ,1550.00 ,50,50,50
BEGIN DESCRIPTION:
31
END DESCRIPTION:
#Sta/Elev= 18
     -11   53.58      -6   52.08      -1   50.58       0   48.08     1.5   47.68
       2   47.38     3.1   46.88     3.8   46.88     5.1   47.38     5.5   48.58
     5.9   48.88     8.3   48.88    10.7   47.08    12.9   45.98    15.9   45.98
    16.3   45.88    16.6   44.98    26.6   44.98
#Mann= 3 , 0 , 0
     -11    .035       0       0    .035       0     5.9    .035       0
#XS Ineff= 2 , 0
               0   48.08     5.9           48.88
Permanent Ineff=
       F       F
Bank Sta=0,5.9
XS Rating Curve= 0
Exp/Cntr=.3,.1

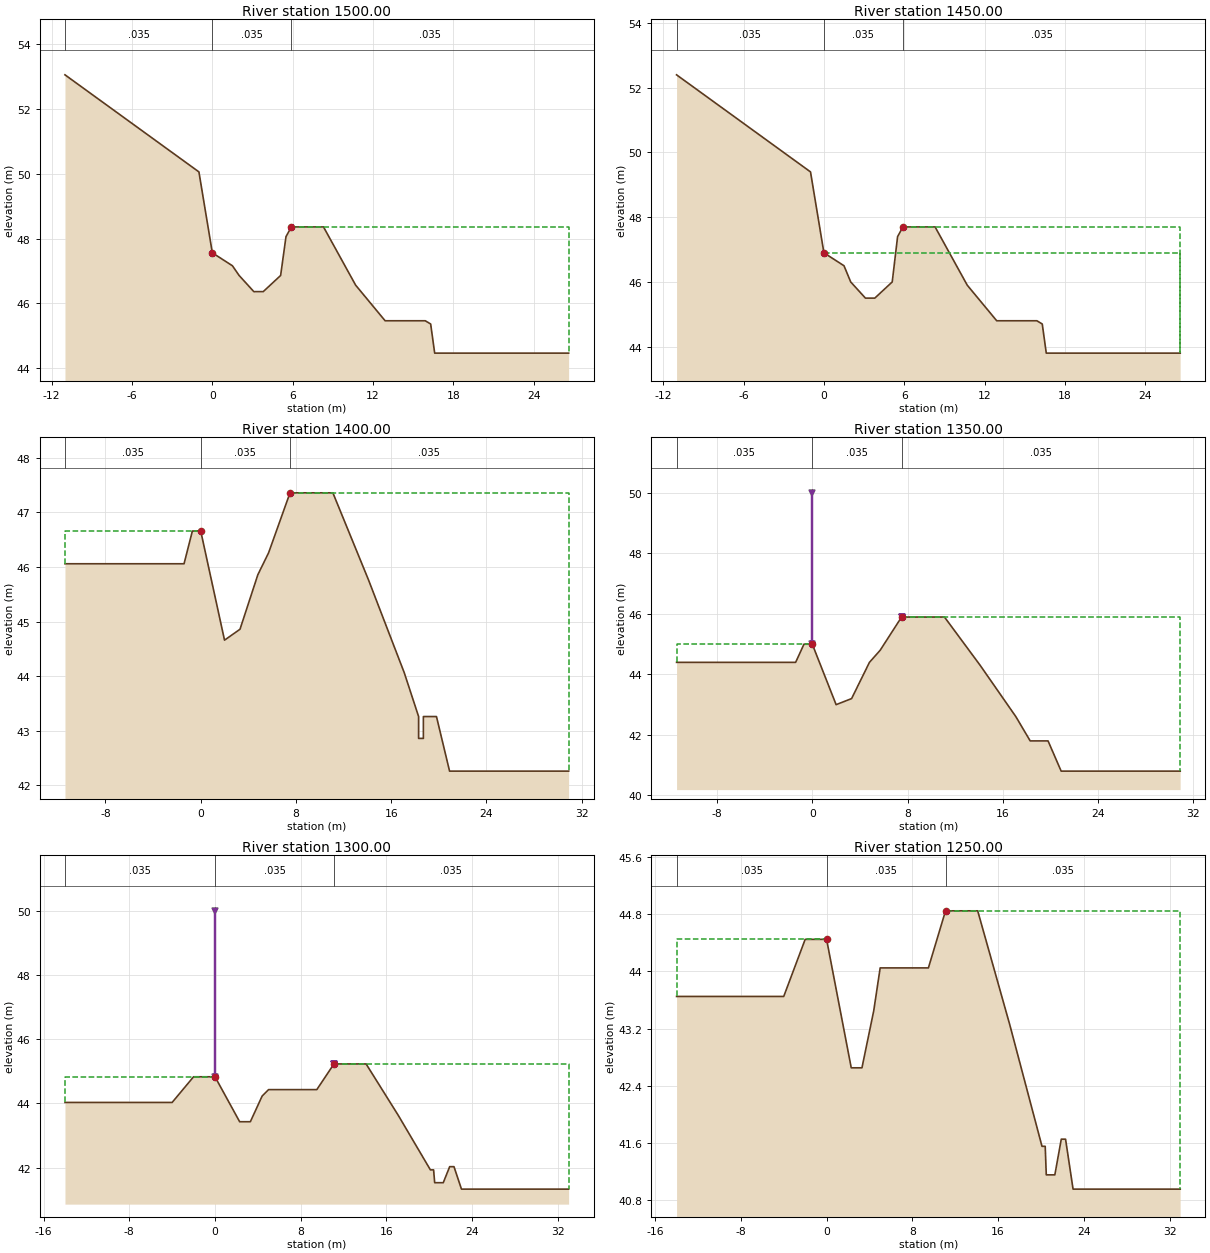
Type RM Length L Ch R = 1 ,1500.00 ,50,50,50
BEGIN DESCRIPTION:
30
END DESCRIPTION:
#Sta/Elev= 18
     -11   53.06      -6   51.56      -1   50.06       0   47.56     1.5   47.16
       2   46.86     3.1   46.36     3.8   46.36     5.1   46.86     5.5   48.06
     5.9   48.36     8.3   48.36    10.7   46.56    12.9   45.46    15.9   45.46
    16.3   45.36    16.6   44.46    26.6   44.46
#Mann= 3 , 0 , 0
     -11    .035       0       0    .035       0     5.9    .035       0
#XS Ineff= 2 , 0
               0   47.56     5.9           48.36
Permanent Ineff=
       F       F
Bank Sta=0,5.9
XS Rating Curve= 0
Exp/Cntr=.3,.1

Type RM Length L Ch R = 1 ,1450.00 ,50,50,50
BEGIN DESCRIPTION:
29
END DESCRIPTION:
#Sta/Elev= 18
     -11    52.4      -6    50.9      -1    49.4       0    46.9     1.5    46.5
       2      46     3.1    45.5     3.8    45.5     5.1      46     5.5    47.4
     5.9    47.7     8.3    47.7    10.7    45.9    12.9    44.8    15.9    44.8
    16.3    44.7    16.6    43.8    26.6    43.8
#Mann= 3 , 0 , 0
     -11    .035       0       0    .035       0     5.9    .035       0
#XS Ineff= 2 , 0
       0       0    46.9     5.9       0    47.7
Permanent Ineff=
       F       F
Bank Sta=0,5.9
XS Rating Curve= 0
Exp/Cntr=.3,.1

Type RM Length L Ch R = 1 ,1400.00 ,50,50,50
BEGIN DESCRIPTION:
28
END DESCRIPTION:
#Sta/Elev= 19
   -11.4   46.06    -1.4   46.06     -.7   46.66       0   46.66       2   44.66
     3.3   44.86     4.8   45.86     5.7   46.26     7.5   47.36    11.1   47.36
    14.1   45.76    17.1   44.06    18.3   43.26    18.3   42.86    18.7   42.86
    18.7   43.26    19.8   43.26    20.9   42.26    30.9   42.26
#Mann= 3 , 0 , 0
   -11.4    .035       0       0    .035       0     7.5    .035       0
#XS Ineff= 2 , 0
               0   46.66     7.5           47.36
Permanent Ineff=
       F       F
Bank Sta=0,7.5
XS Rating Curve= 0
Exp/Cntr=.3,.1

Type RM Length L Ch R = 1 ,1350.00 ,50,50,50
BEGIN DESCRIPTION:
27
END DESCRIPTION:
#Sta/Elev= 17
   -11.4   44.39    -1.4   44.39     -.7   44.99       0   44.99       2   42.99
     3.3   43.19     4.8   44.39     5.7   44.79     7.5   45.89    11.1   45.89
    14.1   44.29    17.1   42.59    18.3   41.79    18.7   41.79    19.8   41.79
    20.9   40.79    30.9   40.79
#Mann= 3 , 0 , 0
   -11.4    .035       0       0    .035       0     7.5    .035       0
Levee=-1,0,50,-1,7.5,45.89,,
#XS Ineff= 2 , 0
               0   44.99     7.5           45.89
Permanent Ineff=
       F       F
Bank Sta=0,7.5
XS Rating Curve= 0
Exp/Cntr=.3,.1

Type RM Length L Ch R = 1 ,1300.00 ,50,50,50
BEGIN DESCRIPTION:
26
END DESCRIPTION:
#Sta/Elev= 20
     -14   44.03      -4   44.03      -2   44.83       0   44.83     2.3   43.43
     3.3   43.43     4.4   44.23       5   44.43     9.5   44.43    11.1   45.23
    14.1   45.23    17.1   43.63    20.1   41.93    20.4   41.93    20.5   41.53
    21.3   41.53    21.9   42.03    22.3   42.03      23   41.33      33   41.33
#Mann= 3 , 0 , 0
     -14    .035       0       0    .035       0    11.1    .035       0
Levee=-1,0,50,-1,11.1,45.23,,
#XS Ineff= 2 , 0
               0   44.83    11.1           45.23
Permanent Ineff=
       F       F
Bank Sta=0,11.1
XS Rating Curve= 0
Exp/Cntr=.3,.1

Type RM Length L Ch R = 1 ,1250.00 ,50,50,50
BEGIN DESCRIPTION:
25
END DESCRIPTION:
#Sta/Elev= 20
     -14   43.65      -4   43.65      -2   44.45       0   44.45     2.3   42.65
     3.3   42.65     4.4   43.45       5   44.05     9.5   44.05    11.1   44.85
    14.1   44.85    17.1   43.25    20.1   41.55    20.4   41.55    20.5   41.15
    21.3   41.15    21.9   41.65    22.3   41.65      23   40.95      33   40.95
#Mann= 3 , 0 , 0
     -14    .035       0       0    .035       0    11.1    .035       0
#XS Ineff= 2 , 0
               0   44.45    11.1           44.85
Permanent Ineff=
       F       F
Bank Sta=0,11.1
XS Rating Curve= 0
Exp/Cntr=.3,.1

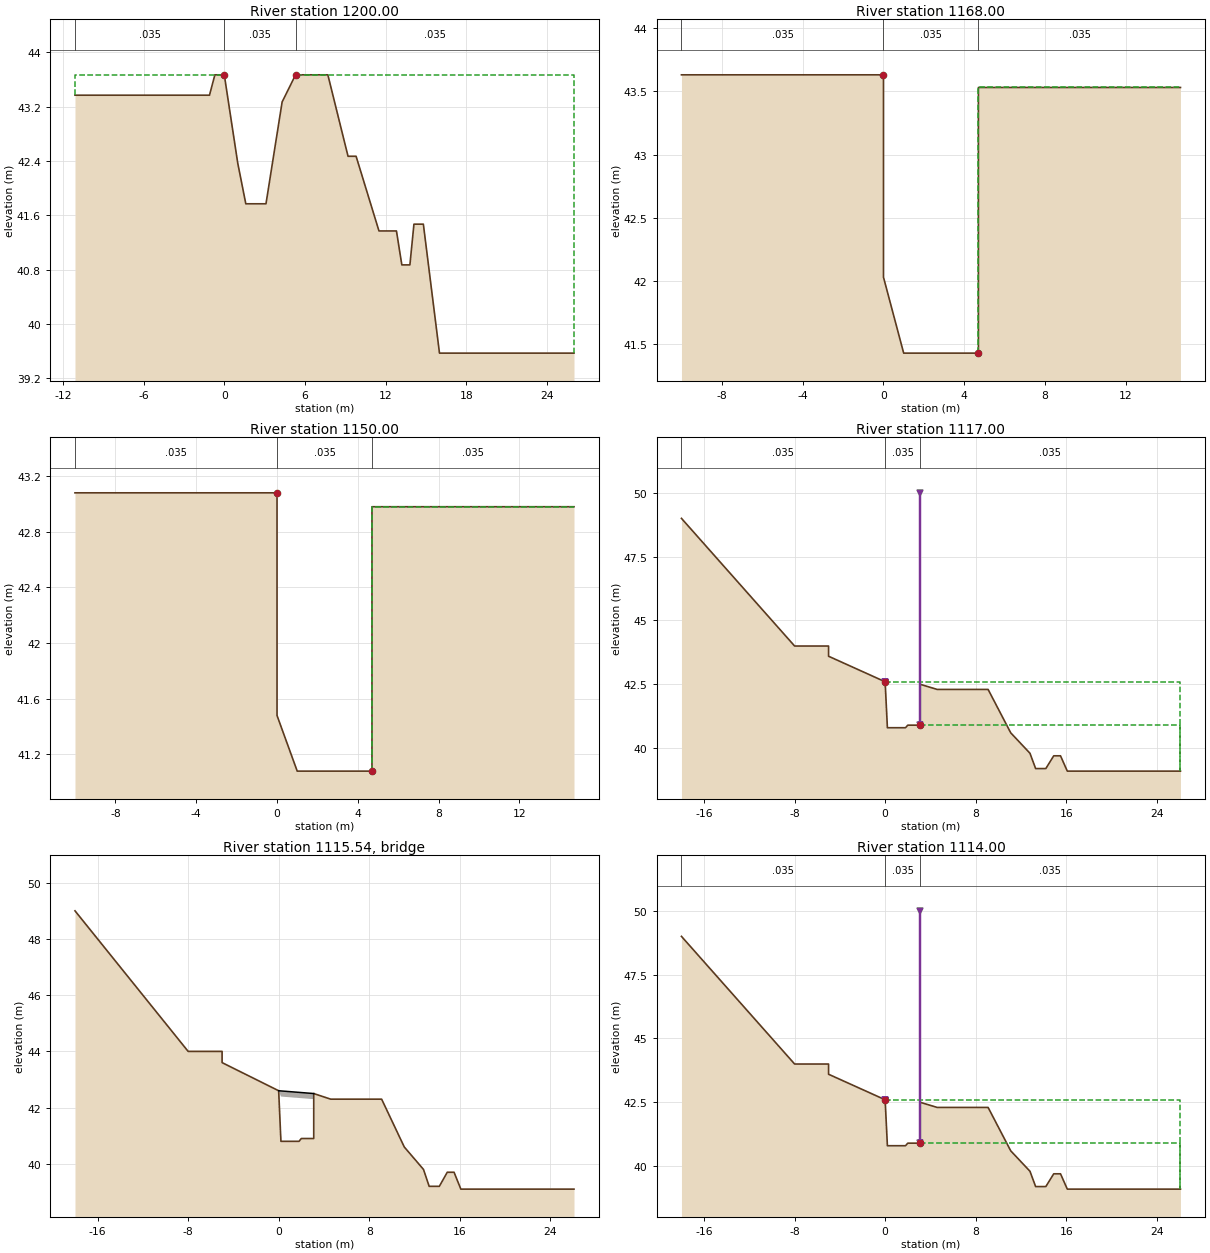
Type RM Length L Ch R = 1 ,1200.00 ,32,32,32
BEGIN DESCRIPTION:
24
END DESCRIPTION:
#Sta/Elev= 20
   -11.1   43.37    -1.1   43.37     -.7   43.67       0   43.67       1   42.37
     1.6   41.77     3.1   41.77     4.3   43.27     5.3   43.67     7.7   43.67
     9.2   42.47     9.8   42.47    11.5   41.37    12.8   41.37    13.2   40.87
    13.8   40.87    14.1   41.47    14.8   41.47      16   39.57      26   39.57
#Mann= 3 , 0 , 0
   -11.1    .035       0       0    .035       0     5.3    .035       0
#XS Ineff= 2 , 0
               0   43.67     5.3           43.67
Permanent Ineff=
       F       F
Bank Sta=0,5.3
XS Rating Curve= 0
Exp/Cntr=.3,.1

Type RM Length L Ch R = 1 ,1168.00 ,18,18,18
BEGIN DESCRIPTION:
23.018
END DESCRIPTION:
#Sta/Elev= 7
     -10   43.63       0   43.63       0   42.03       1   41.43     4.7   41.43
     4.7   43.53    14.7   43.53
#Mann= 3 , 0 , 0
     -10    .035       0       0    .035       0     4.7    .035       0
#XS Ineff= 2 , 0
               0   43.63     4.7           43.53
Permanent Ineff=
       F       F
Bank Sta=0,4.7
XS Rating Curve= 0
Exp/Cntr=.3,.1

Type RM Length L Ch R = 1 ,1150.00 ,33,33,33
BEGIN DESCRIPTION:
23
END DESCRIPTION:
#Sta/Elev= 7
     -10   43.08       0   43.08       0   41.48       1   41.08     4.7   41.08
     4.7   42.98    14.7   42.98
#Mann= 3 , 0 , 0
     -10    .035       0       0    .035       0     4.7    .035       0
#XS Ineff= 2 , 0
               0   43.08     4.7           42.98
Permanent Ineff=
       F       F
Bank Sta=0,4.7
XS Rating Curve= 0
Exp/Cntr=.3,.1

Type RM Length L Ch R = 1 ,1117.00 ,3,3,3
BEGIN DESCRIPTION:
22.017
END DESCRIPTION:
#Sta/Elev= 21
     -18      49     -13    46.5      -8      44      -5      44      -5    43.6
       0    42.6      .2    40.8     1.8    40.8       2    40.9     3.1    40.9
     3.1    42.5     4.6    42.3     9.1    42.3    11.1    40.6    12.8    39.8
    13.3    39.2    14.2    39.2    14.9    39.7    15.5    39.7    16.1    39.1
    26.1    39.1
#Mann= 3 , 0 , 0
     -18    .035       0       0    .035       0     3.1    .035       0
Levee=-1,0,42.6,-1,3.1,50,,
#XS Ineff= 2 , 0
       0       0    42.6     3.1       0    40.9
Permanent Ineff=
       F       F
Bank Sta=0,3.1
XS Rating Curve= 0
Exp/Cntr=.3,.1

Type RM Length L Ch R = 3 ,1115.54 ,,,
BEGIN DESCRIPTION:
22.0155
END DESCRIPTION:
Bridge Culvert--1,0,-1,-1, 0
Deck Dist Width WeirC Skew NumUp NumDn MinLoCord MaxHiCord MaxSubmerge Is_Ogee
.01,2.9,1.44,0, 2, 2, , , .95, 0, 0,0,,
       0     3.1
    42.6    42.5
    42.4    42.3
       0     3.1
    42.6    42.5
    42.4    42.3
BR Coef=-1 , 1 , 0 ,, 0 ,,,.8,-1,1.2,0,
WSPro=,,,, 1 ,,,, 0 ,,,, 0 ,,,,-1 ,-1 ,-1 , 0 , 0 , 0 , 0 , 0
BC Design=,, 0 ,, 0 ,,,,,,

Type RM Length L Ch R = 1 ,1114.00 ,14,14,14
BEGIN DESCRIPTION:
22.014
END DESCRIPTION:
#Sta/Elev= 21
     -18      49     -13    46.5      -8      44      -5      44      -5    43.6
       0    42.6      .2    40.8     1.8    40.8       2    40.9     3.1    40.9
     3.1    42.5     4.6    42.3     9.1    42.3    11.1    40.6    12.8    39.8
    13.3    39.2    14.2    39.2    14.9    39.7    15.5    39.7    16.1    39.1
    26.1    39.1
#Mann= 3 , 0 , 0
     -18    .035       0       0    .035       0     3.1    .035       0
Levee=-1,0,42.6,-1,3.1,50,,
#XS Ineff= 2 , 0
       0       0    42.6     3.1       0    40.9
Permanent Ineff=
       F       F
Bank Sta=0,3.1
XS Rating Curve= 0
Exp/Cntr=.3,.1

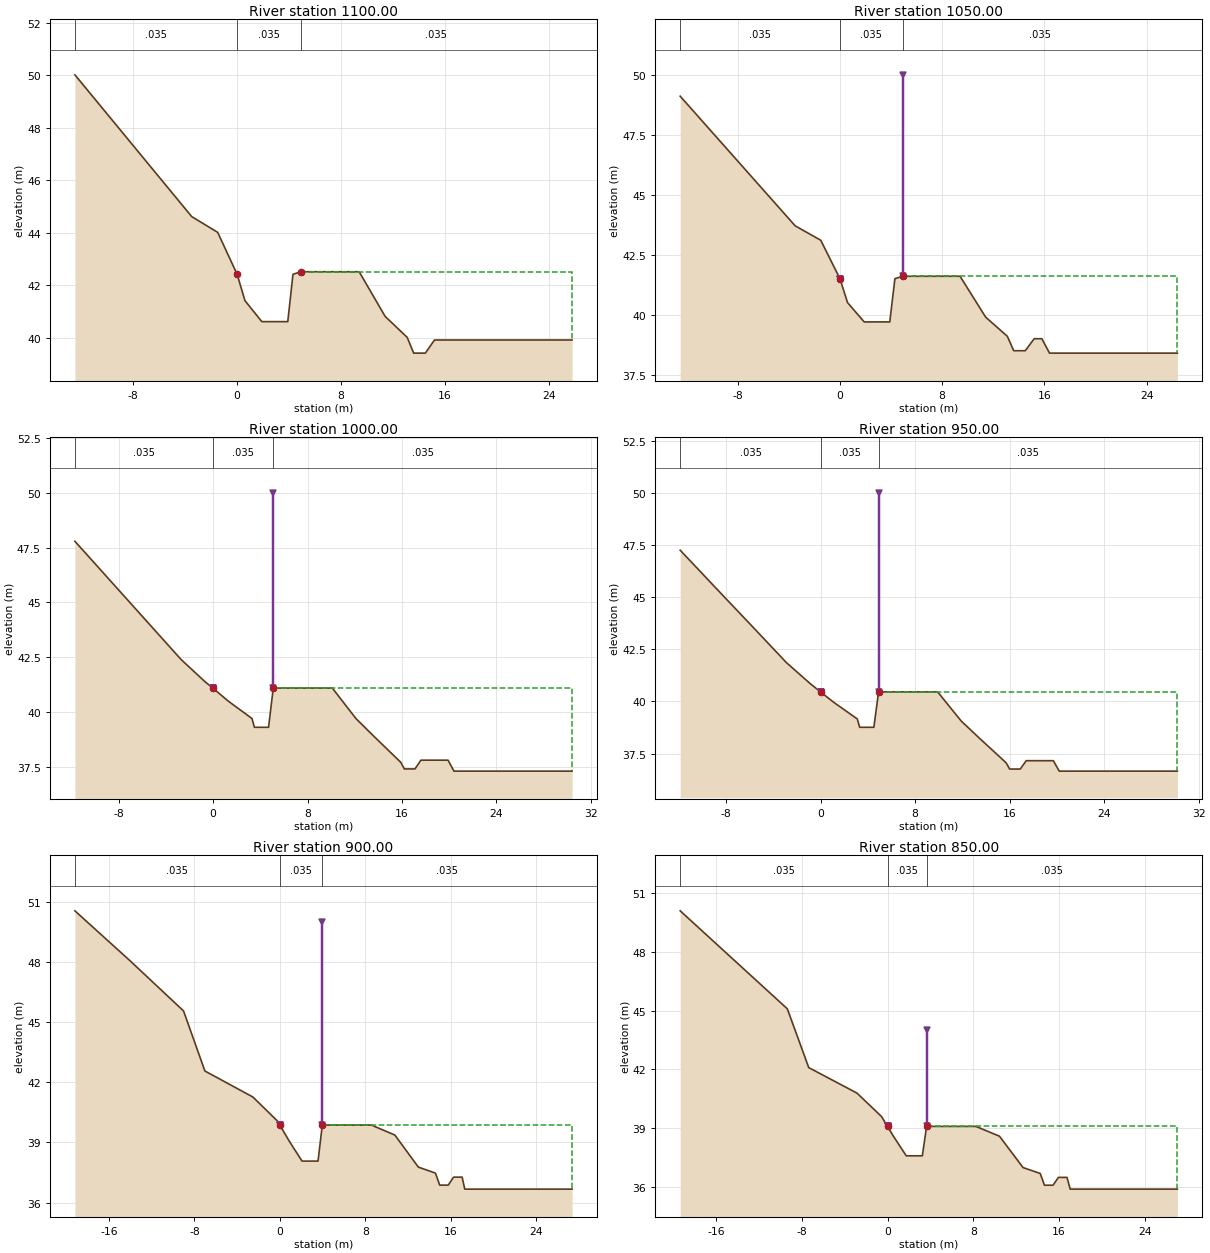
Type RM Length L Ch R = 1 ,1100.00 ,50,50,50
BEGIN DESCRIPTION:
22
END DESCRIPTION:
#Sta/Elev= 19
   -12.5   50.02    -9.5   48.22    -6.5   46.42    -3.5   44.62    -1.5   44.02
       0   42.42      .6   41.42     1.9   40.62     3.9   40.62     4.3   42.42
     4.9   42.52     9.4   42.52    11.4   40.82    13.1   40.02    13.6   39.42
    14.5   39.42    15.2   39.92    15.8   39.92    25.8   39.92
#Mann= 3 , 0 , 0
   -12.5    .035       0       0    .035       0     4.9    .035       0
#XS Ineff= 2 , 0
               0   42.42     4.9           42.52
Permanent Ineff=
       F       F
Bank Sta=0,4.9
XS Rating Curve= 0
Exp/Cntr=.3,.1

Type RM Length L Ch R = 1 ,1050.00 ,50,50,50
BEGIN DESCRIPTION:
21
END DESCRIPTION:
#Sta/Elev= 20
   -12.5   49.11    -9.5   47.31    -6.5   45.51    -3.5   43.71    -1.5   43.11
       0   41.51      .6   40.51     1.9   39.71     3.9   39.71     4.3   41.51
     4.9   41.61     9.4   41.61    11.4   39.91    13.1   39.11    13.6   38.51
    14.5   38.51    15.2   39.01    15.8   39.01    16.4   38.41    26.4   38.41
#Mann= 3 , 0 , 0
   -12.5    .035       0       0    .035       0     4.9    .035       0
Levee=-1,0,41.51,-1,4.9,50,,
#XS Ineff= 2 , 0
               0   41.51     4.9           41.61
Permanent Ineff=
       F       F
Bank Sta=0,4.9
XS Rating Curve= 0
Exp/Cntr=.3,.1

Type RM Length L Ch R = 1 ,1000.00 ,50,50,50
BEGIN DESCRIPTION:
20
END DESCRIPTION:
#Sta/Elev= 21
   -11.7   47.79    -8.7   45.99    -5.7   44.19    -2.7   42.39     -.7   41.39
       0   41.08     1.3   40.49     3.3    39.7     3.5    39.3     4.7    39.3
     5.1   41.09    10.1   41.09    12.1    39.7    13.6    38.9    15.9    37.7
    16.2    37.4    17.1    37.4    17.6    37.8    19.9    37.8    20.4    37.3
    30.4    37.3
#Mann= 3 , 0 , 0
   -11.7    .035       0       0    .035       0     5.1    .035       0
Levee=-1,0,41.08,-1,5.1,50,,
#XS Ineff= 2 , 0
               0   41.08     5.1           41.09
Permanent Ineff=
       F       F
Bank Sta=0,5.1
XS Rating Curve= 0
Exp/Cntr=.3,.1

Type RM Length L Ch R = 1 ,950.00  ,50,50,50
BEGIN DESCRIPTION:
19
END DESCRIPTION:
#Sta/Elev= 21
   -11.9   47.25    -8.9   45.45    -5.9   43.66    -2.9   41.86     -.9   40.86
       0   40.45     1.1   39.96     3.1   39.16     3.3   38.76     4.5   38.76
     4.9   40.46     9.9   40.46    11.9   39.06    13.4   38.26    15.7   37.06
      16   36.76    16.9   36.76    17.4   37.16    19.7   37.16    20.2   36.66
    30.2   36.66
#Mann= 3 , 0 , 0
   -11.9    .035       0       0    .035       0     4.9    .035       0
Levee=-1,0,40.45,-1,4.9,50,,
#XS Ineff= 2 , 0
               0   40.45     4.9           40.46
Permanent Ineff=
       F       F
Bank Sta=0,4.9
XS Rating Curve= 0
Exp/Cntr=.3,.1

Type RM Length L Ch R = 1 ,900.00  ,50,50,50
BEGIN DESCRIPTION:
18
END DESCRIPTION:
#Sta/Elev= 21
   -19.2   50.57  -14.02   48.07   -9.02   45.57   -7.02   42.57   -2.52   41.27
    -.22   40.07       0   39.87     .88   39.07    2.08   38.07    3.58   38.07
    3.98   39.87    8.58   39.87   10.78   39.37   12.98   37.77   14.58   37.47
   14.98   36.87   15.78   36.87   16.28   37.27   17.08   37.27   17.33   36.67
   27.38   36.67
#Mann= 3 , 0 , 0
   -19.2    .035       0       0    .035       0    3.98    .035       0
Levee=-1,0,39.87,-1,3.98,50,,
#XS Ineff= 2 , 0
               0   39.87    3.98           39.87
Permanent Ineff=
       F       F
Bank Sta=0,3.98
XS Rating Curve= 0
Exp/Cntr=.3,.1

Type RM Length L Ch R = 1 ,850.00  ,50,50,50
BEGIN DESCRIPTION:
17
END DESCRIPTION:
#Sta/Elev= 21
  -19.35   50.09  -14.35   47.59   -9.35   45.09   -7.35   42.09   -2.85   40.79
    -.55   39.59       0   39.09     .55   38.59    1.75   37.59    3.25   37.59
    3.65   39.09    8.25   39.09   10.45   38.59   12.65   36.99   14.25   36.69
   14.65   36.09   15.45   36.09   15.95   36.49   16.75   36.49   17.05   35.89
   27.05   35.89
#Mann= 3 , 0 , 0
  -19.35    .035       0       0    .035       0    3.65    .035       0
Levee=-1,0,39.09,-1,3.65,44,,
#XS Ineff= 2 , 0
               0   39.09    3.65           39.09
Permanent Ineff=
       F       F
Bank Sta=0,3.65
XS Rating Curve= 0
Exp/Cntr=.3,.1

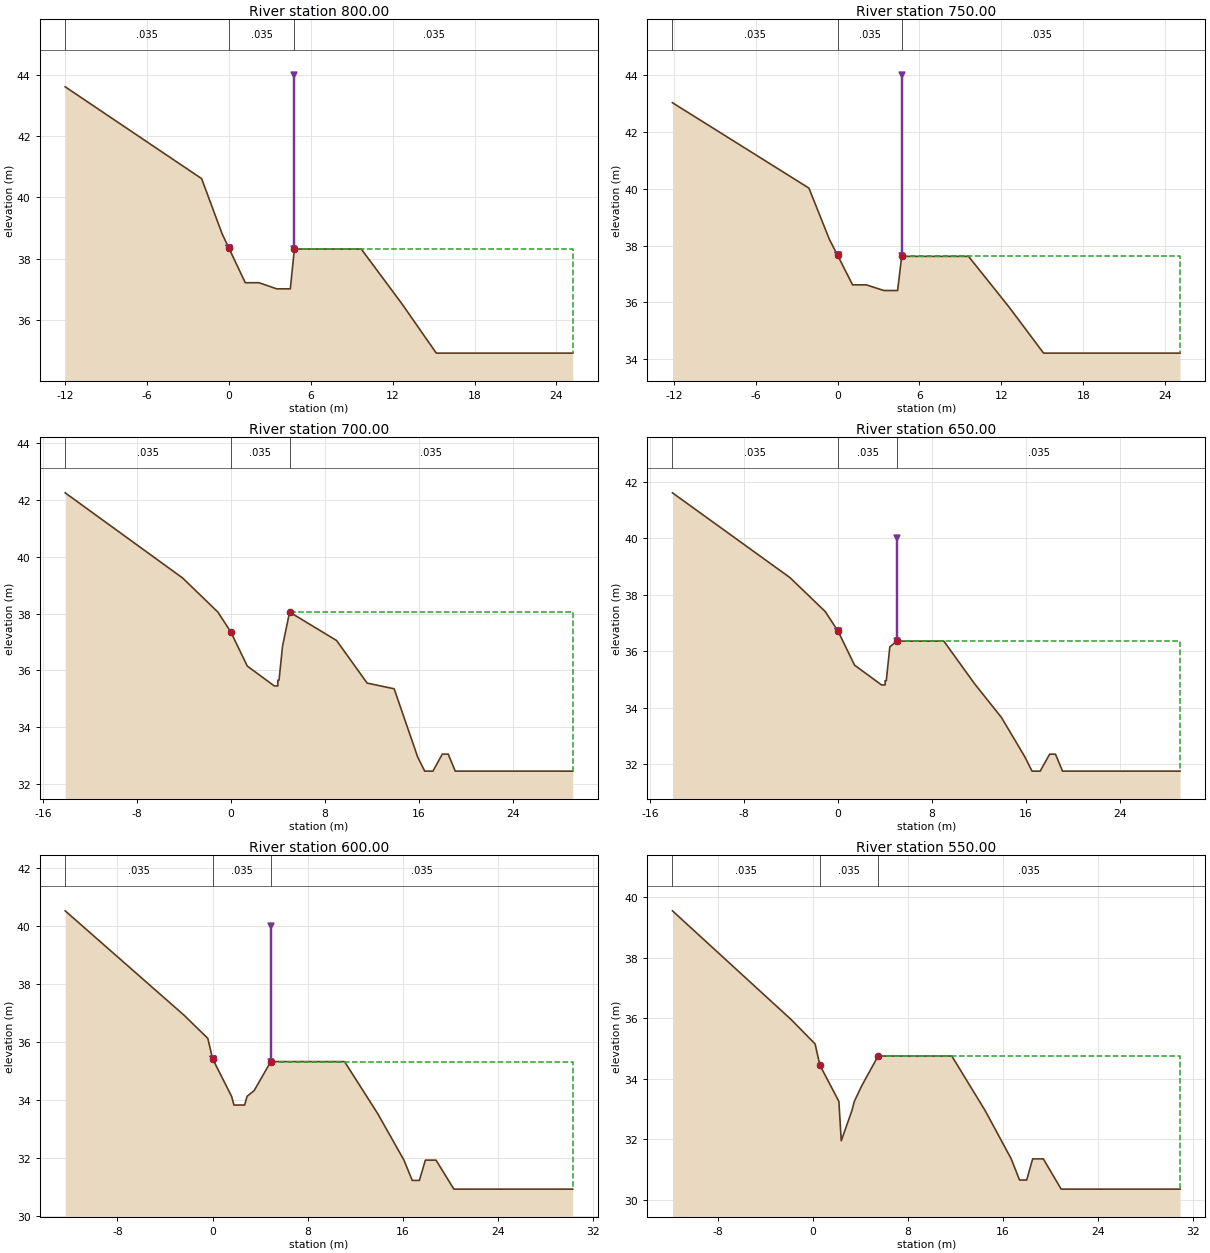
Type RM Length L Ch R = 1 ,800.00  ,50,50,50
BEGIN DESCRIPTION:
16
END DESCRIPTION:
#Sta/Elev= 14
     -12   43.61      -7   42.11      -2   40.61     -.5   38.81       0   38.34
     1.2   37.21     2.2   37.21     3.5   37.01     4.5   37.01     4.8   38.31
     9.7   38.31    12.7   36.51    15.2   34.91    25.2   34.91
#Mann= 3 , 0 , 0
     -12    .035       0       0    .035       0     4.8    .035       0
Levee=-1,0,38.34,-1,4.8,44,,
#XS Ineff= 2 , 0
               0   38.34     4.8           38.31
Permanent Ineff=
       F       F
Bank Sta=0,4.8
XS Rating Curve= 0
Exp/Cntr=.3,.1

Type RM Length L Ch R = 1 ,750.00  ,50,50,50
BEGIN DESCRIPTION:
15
END DESCRIPTION:
#Sta/Elev= 14
   -12.1   43.02    -7.1   41.52    -2.1   40.02     -.6   38.22       0   37.66
     1.1   36.62     2.1   36.62     3.4   36.42     4.4   36.42     4.7   37.62
     9.6   37.62    12.6   35.82    15.1   34.22    25.1   34.22
#Mann= 3 , 0 , 0
   -12.1    .035       0       0    .035       0     4.7    .035       0
Levee=-1,0,37.66,-1,4.7,44,,
#XS Ineff= 2 , 0
               0   37.66     4.7           37.62
Permanent Ineff=
       F       F
Bank Sta=0,4.7
XS Rating Curve= 0
Exp/Cntr=.3,.1

Type RM Length L Ch R = 1 ,700.00  ,50,50,50
BEGIN DESCRIPTION:
14
END DESCRIPTION:
#Sta/Elev= 22
   -14.1   42.25    -9.1   40.75    -4.1   39.25    -1.1   38.05       0   37.35
     1.4   36.15     3.7   35.45       4   35.45       4   35.65     4.1   35.65
     4.4   36.85       5   38.05       9   37.05    11.6   35.55    13.9   35.35
    15.9   32.95    16.5   32.45    17.2   32.45      18   33.05    18.5   33.05
    19.1   32.45    29.1   32.45
#Mann= 3 , 0 , 0
   -14.1    .035       0       0    .035       0       5    .035       0
#XS Ineff= 2 , 0
               0   37.35       5           38.05
Permanent Ineff=
       F       F
Bank Sta=0,5
XS Rating Curve= 0
Exp/Cntr=.3,.1

Type RM Length L Ch R = 1 ,650.00  ,50,50,50
BEGIN DESCRIPTION:
13
END DESCRIPTION:
#Sta/Elev= 22
   -14.1    41.6    -9.1    40.1    -4.1    38.6    -1.1    37.4       0    36.7
     1.4    35.5     3.7    34.8       4    34.8       4   34.95     4.1   34.95
     4.4   36.15       5   36.35       9   36.35    11.6   34.85    13.9   33.65
    15.9   32.25    16.5   31.75    17.2   31.75      18   32.35    18.5   32.35
    19.1   31.75    29.1   31.75
#Mann= 3 , 0 , 0
   -14.1    .035       0       0    .035       0       5    .035       0
Levee=-1,0,36.7,-1,5,40,,
#XS Ineff= 2 , 0
               0    36.7       5           36.35
Permanent Ineff=
       F       F
Bank Sta=0,5
XS Rating Curve= 0
Exp/Cntr=.3,.1

Type RM Length L Ch R = 1 ,600.00  ,50,50,50
BEGIN DESCRIPTION:
12
END DESCRIPTION:
#Sta/Elev= 20
   -12.4   40.53    -7.4   38.73    -2.4   36.93     -.4   36.13       0   35.43
     1.6   34.13     1.8   33.83     2.7   33.83     2.9   34.13     3.5   34.33
     4.9   35.33    11.1   35.33    13.9   33.53    16.1   31.93    16.8   31.23
    17.4   31.23    17.9   31.93    18.8   31.93    20.3   30.93    30.3   30.93
#Mann= 3 , 0 , 0
   -12.4    .035       0       0    .035       0     4.9    .035       0
Levee=-1,0,35.43,-1,4.9,40,,
#XS Ineff= 2 , 0
               0   35.43     4.9           35.33
Permanent Ineff=
       F       F
Bank Sta=0,4.9
XS Rating Curve= 0
Exp/Cntr=.3,.1

Type RM Length L Ch R = 1 ,550.00  ,50,50,50
BEGIN DESCRIPTION:
11
END DESCRIPTION:
#Sta/Elev= 21
   -11.8   39.55    -6.8   37.75    -1.8   35.95       0   35.23      .2   35.15
      .6   34.45     2.2   33.25     2.4   31.95     3.3   32.95     3.5   33.25
     4.1   33.75     5.5   34.75    11.7   34.75    14.5   32.95    16.7   31.35
    17.4   30.65      18   30.65    18.5   31.35    19.4   31.35    20.9   30.35
    30.9   30.35
#Mann= 3 , 0 , 0
   -11.8    .035       0      .6    .035       0     5.5    .035       0
#XS Ineff= 2 , 0
       0      .6   34.45     5.5       0   34.75
Permanent Ineff=
       F       F
Bank Sta=.6,5.5
XS Rating Curve= 0
Exp/Cntr=.3,.1

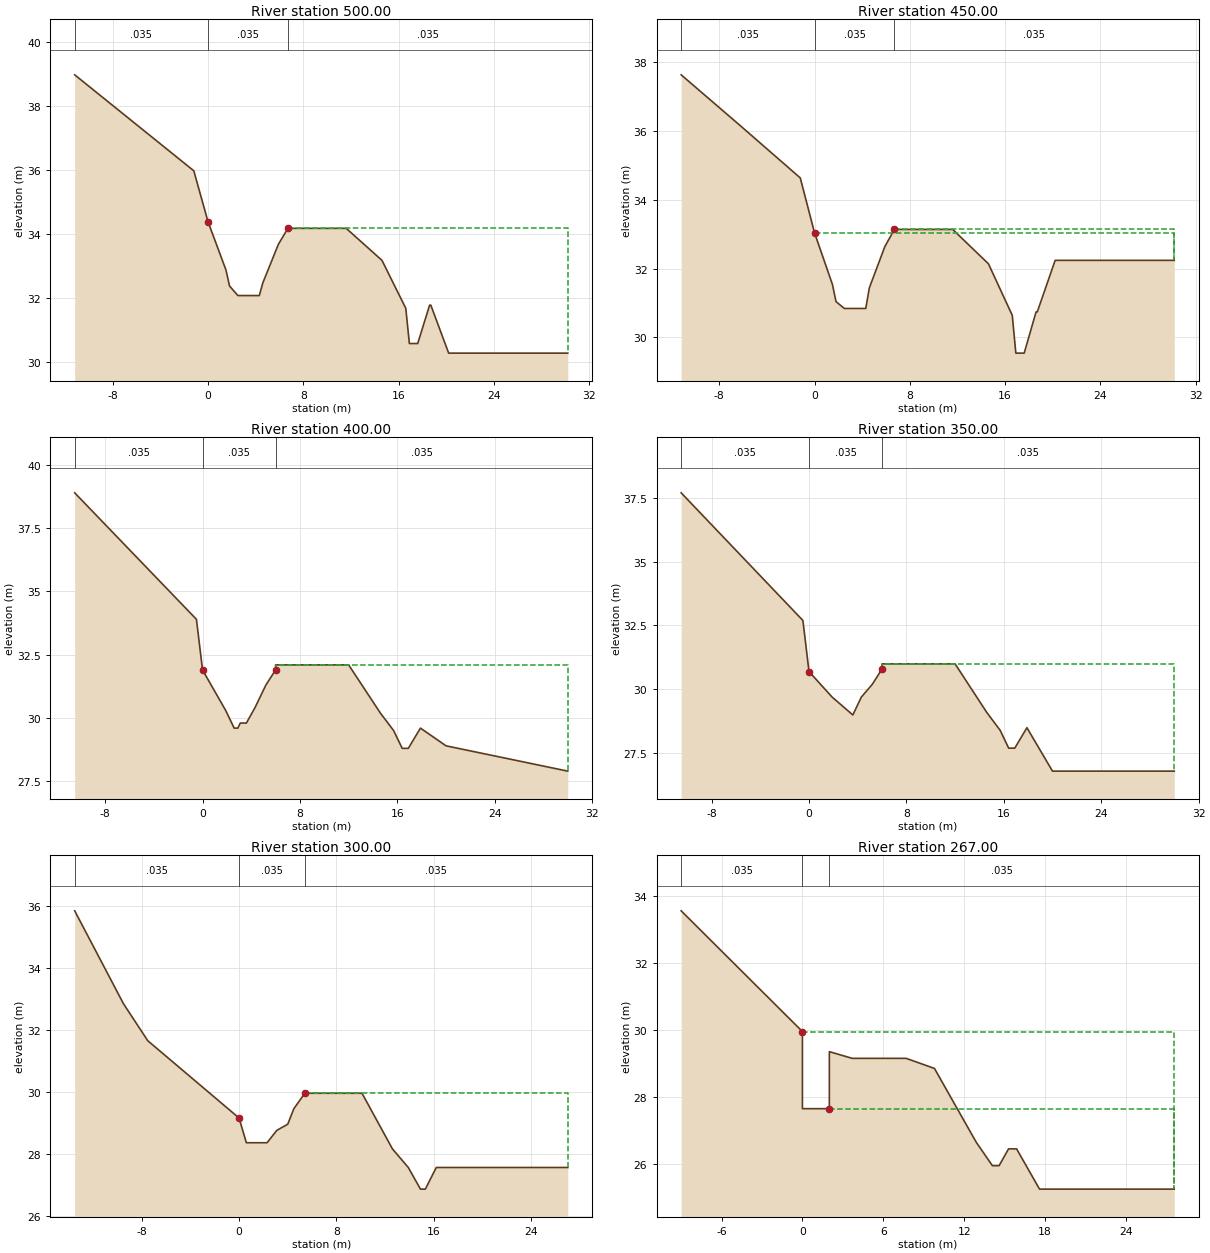
Type RM Length L Ch R = 1 ,500.00  ,50,50,50
BEGIN DESCRIPTION:
10
END DESCRIPTION:
#Sta/Elev= 20
   -11.2   38.98    -6.2   37.48    -1.2   35.98       0   34.38     1.5   32.88
     1.8   32.38     2.5   32.08     4.3   32.08     4.6   32.48     5.9   33.68
     6.7   34.18    11.6   34.18    14.6   33.18    16.6   31.68    16.9   30.58
    17.6   30.58    18.6   31.78    18.7   31.78    20.2   30.28    30.2   30.28
#Mann= 3 , 0 , 0
   -11.2    .035       0       0    .035       0     6.7    .035       0
#XS Ineff= 2 , 0
               0   34.38     6.7           34.18
Permanent Ineff=
       F       F
Bank Sta=0,6.7
XS Rating Curve= 0
Exp/Cntr=.3,.1

Type RM Length L Ch R = 1 ,450.00  ,50,50,50
BEGIN DESCRIPTION:
9
END DESCRIPTION:
#Sta/Elev= 20
   -11.2   37.64    -6.2   36.15    -1.2   34.64       0   33.04     1.5   31.54
     1.8   31.04     2.5   30.84     4.3   30.84     4.6   31.44     5.9   32.64
     6.7   33.14    11.6   33.14    14.6   32.14    16.6   30.64    16.9   29.54
    17.6   29.54    18.6   30.74    18.7   30.74    20.2   32.24    30.2   32.24
#Mann= 3 , 0 , 0
   -11.2    .035       0       0    .035       0     6.7    .035       0
#XS Ineff= 2 , 0
       0       0   33.04     6.7       0   33.14
Permanent Ineff=
       F       F
Bank Sta=0,6.7
XS Rating Curve= 0
Exp/Cntr=.3,.1

Type RM Length L Ch R = 1 ,400.00  ,50,50,50
BEGIN DESCRIPTION:
8
END DESCRIPTION:
#Sta/Elev= 21
   -10.5    38.9    -5.5    36.4     -.5    33.9       0    31.9     1.9    30.3
     2.6    29.6     2.9    29.6     3.1    29.8     3.6    29.8     4.3    30.4
     5.2    31.3       6    31.9       6    32.1      12    32.1    14.6    30.2
    15.7    29.5    16.4    28.8    16.9    28.8    17.9    29.6      20    28.9
      30    27.9
#Mann= 3 , 0 , 0
   -10.5    .035       0       0    .035       0       6    .035       0
#XS Ineff= 2 , 0
               0    31.9       6            32.1
Permanent Ineff=
       F       F
Bank Sta=0,6
XS Rating Curve= 0
Exp/Cntr=.3,.1

Type RM Length L Ch R = 1 ,350.00  ,50,50,50
BEGIN DESCRIPTION:
7
END DESCRIPTION:
#Sta/Elev= 18
   -10.5   37.69    -5.5   35.19     -.5   32.69       0   30.69     1.9   29.69
     3.6   28.99     4.3   29.69     5.2   30.19       6   30.79       6   30.99
      12   30.99    14.6   29.09    15.7   28.39    16.4   27.69    16.9   27.69
    17.9   28.49      20   26.79      30   26.79
#Mann= 3 , 0 , 0
   -10.5    .035       0       0    .035       0       6    .035       0
#XS Ineff= 2 , 0
               0   30.69       6           30.99
Permanent Ineff=
       F       F
Bank Sta=0,6
XS Rating Curve= 0
Exp/Cntr=.3,.1

Type RM Length L Ch R = 1 ,300.00  ,33,33,33
BEGIN DESCRIPTION:
6
END DESCRIPTION:
#Sta/Elev= 19
   -13.5   35.86   -11.5   34.36    -9.5   32.86    -7.5   31.66       0   29.16
      .6   28.36     2.3   28.36     3.1   28.76       4   28.96     4.5   29.46
     5.4   29.96    10.1   29.96    12.6   28.16    13.9   27.56    14.9   26.86
    15.3   26.86    16.2   27.56      17   27.56      27   27.56
#Mann= 3 , 0 , 0
   -13.5    .035       0       0    .035       0     5.4    .035       0
#XS Ineff= 2 , 0
               0   29.16     5.4           29.96
Permanent Ineff=
       F       F
Bank Sta=0,5.4
XS Rating Curve= 0
Exp/Cntr=.3,.1

Type RM Length L Ch R = 1 ,267.00  ,4,4,4
BEGIN DESCRIPTION:
5.017
END DESCRIPTION:
#Sta/Elev= 17
      -9   33.56      -6   32.36      -3   31.16       0   29.96       0   27.66
       2   27.66       2   29.36     3.7   29.16     7.7   29.16     9.8   28.86
    12.9   26.66    14.1   25.96    14.6   25.96    15.3   26.46    15.9   26.46
    17.6   25.26    27.6   25.26
#Mann= 3 , 0 , 0
      -9    .035       0       0    .035       0       2    .035       0
#XS Ineff= 2 , 0
       0       0   29.96       2       0   27.66
Permanent Ineff=
       F       F
Bank Sta=0,2
XS Rating Curve= 0
Exp/Cntr=.3,.1