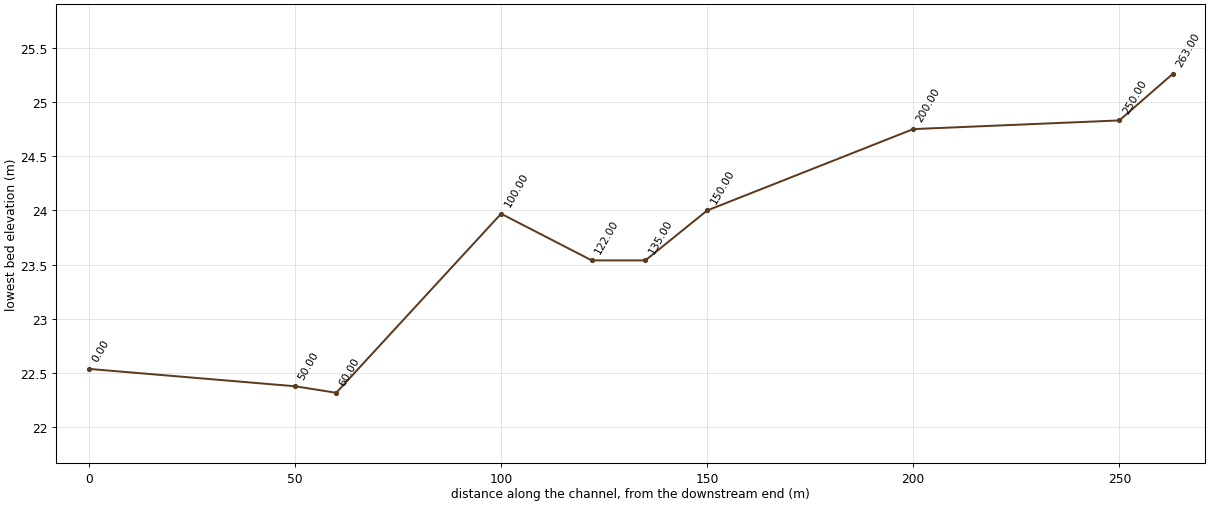
HEC-RAS study jmc.prj: zangma-ch

--- jmc.g01 (geometry) --- (continued)

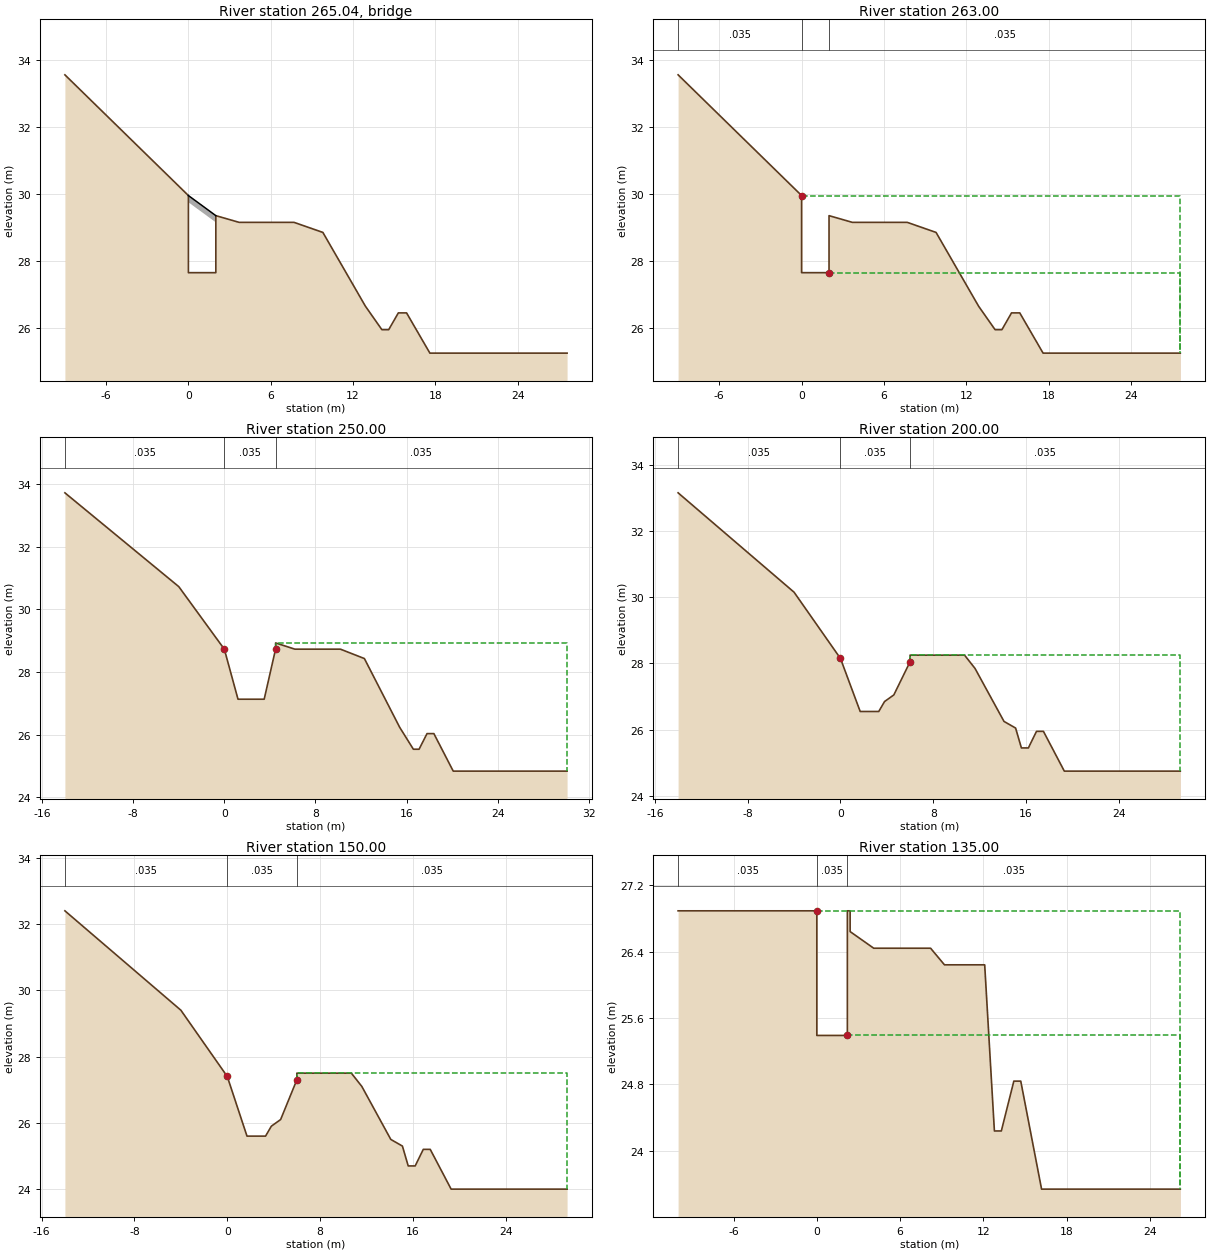
Type RM Length L Ch R = 3 ,265.04  ,,,
BEGIN DESCRIPTION:
5.015
END DESCRIPTION:
Bridge Culvert--1,0,-1,-1, 0
Deck Dist Width WeirC Skew NumUp NumDn MinLoCord MaxHiCord MaxSubmerge Is_Ogee
.01,3.9,1.44,0, 2, 2, , , .95, 0, 0,0,,
       0       2
   29.96   29.36
   29.76   29.16
       0       2
   29.96   29.36
   29.76   29.16
BR Coef=-1 , 1 , 0 ,, 0 ,,,.8,-1,1.2,0,
WSPro=,,,, 1 ,,,, 0 ,,,, 0 ,,,,-1 ,-1 ,-1 , 0 , 0 , 0 , 0 , 0
BC Design=,, 0 ,, 0 ,,,,,,

Type RM Length L Ch R = 1 ,263.00  ,13,13,13
BEGIN DESCRIPTION:
5.013
END DESCRIPTION:
#Sta/Elev= 17
      -9   33.56      -6   32.36      -3   31.16       0   29.96       0   27.66
       2   27.66       2   29.36     3.7   29.16     7.7   29.16     9.8   28.86
    12.9   26.66    14.1   25.96    14.6   25.96    15.3   26.46    15.9   26.46
    17.6   25.26    27.6   25.26
#Mann= 3 , 0 , 0
      -9    .035       0       0    .035       0       2    .035       0
#XS Ineff= 2 , 0
       0       0   29.96       2       0   27.66
Permanent Ineff=
       F       F
Bank Sta=0,2
XS Rating Curve= 0
Exp/Cntr=.3,.1

Type RM Length L Ch R = 1 ,250.00  ,50,50,50
BEGIN DESCRIPTION:
5
END DESCRIPTION:
#Sta/Elev= 18
     -14   33.73      -9   32.23      -4   30.73       0   28.73     1.2   27.13
     3.5   27.13     4.5   28.73     4.5   28.93     6.2   28.73    10.2   28.73
    12.3   28.43    15.4   26.23    16.6   25.53    17.1   25.53    17.8   26.03
    18.4   26.03    20.1   24.83    30.1   24.83
#Mann= 3 , 0 , 0
     -14    .035       0       0    .035       0     4.5    .035       0
#XS Ineff= 2 , 0
               0   28.73     4.5           28.93
Permanent Ineff=
       F       F
Bank Sta=0,4.5
XS Rating Curve= 0
Exp/Cntr=.3,.1

Type RM Length L Ch R = 1 ,200.00  ,50,50,50
BEGIN DESCRIPTION:
4
END DESCRIPTION:
#Sta/Elev= 20
     -14   33.15      -9   31.65      -4   30.15       0   28.15     1.7   26.55
     3.3   26.55     3.8   26.85     4.6   27.05       6   28.05       6   28.25
    10.7   28.25    11.6   27.85    14.1   26.25    15.1   26.05    15.6   25.45
    16.2   25.45    16.9   25.95    17.5   25.95    19.3   24.75    29.3   24.75
#Mann= 3 , 0 , 0
     -14    .035       0       0    .035       0       6    .035       0
#XS Ineff= 2 , 0
               0   28.15       6           28.25
Permanent Ineff=
       F       F
Bank Sta=0,6
XS Rating Curve= 0
Exp/Cntr=.3,.1

Type RM Length L Ch R = 1 ,150.00  ,15,15,15
BEGIN DESCRIPTION:
3
END DESCRIPTION:
#Sta/Elev= 20
     -14    32.4      -9    30.9      -4    29.4       0    27.4     1.7    25.6
     3.3    25.6     3.8    25.9     4.6    26.1       6    27.3       6    27.5
    10.7    27.5    11.6    27.1    14.1    25.5    15.1    25.3    15.6    24.7
    16.2    24.7    16.9    25.2    17.5    25.2    19.3      24    29.3      24
#Mann= 3 , 0 , 0
     -14    .035       0       0    .035       0       6    .035       0
#XS Ineff= 2 , 0
               0    27.4       6            27.5
Permanent Ineff=
       F       F
Bank Sta=0,6
XS Rating Curve= 0
Exp/Cntr=.3,.1

Type RM Length L Ch R = 1 ,135.00  ,13,13,13
BEGIN DESCRIPTION:
2.035
END DESCRIPTION:
#Sta/Elev= 17
     -10   26.89       0   26.89       0   25.39     2.2   25.39     2.2   26.89
     2.4   26.89     2.4   26.64     4.1   26.44     8.2   26.44     9.2   26.24
    12.1   26.24    12.8   24.24    13.3   24.24    14.2   24.84    14.7   24.84
    16.2   23.54    26.2   23.54
#Mann= 3 , 0 , 0
     -10    .035       0       0    .035       0     2.2    .035       0
#XS Ineff= 2 , 0
       0       0   26.89     2.2       0   25.39
Permanent Ineff=
       F       F
Bank Sta=0,2.2
XS Rating Curve= 0
Exp/Cntr=.3,.1

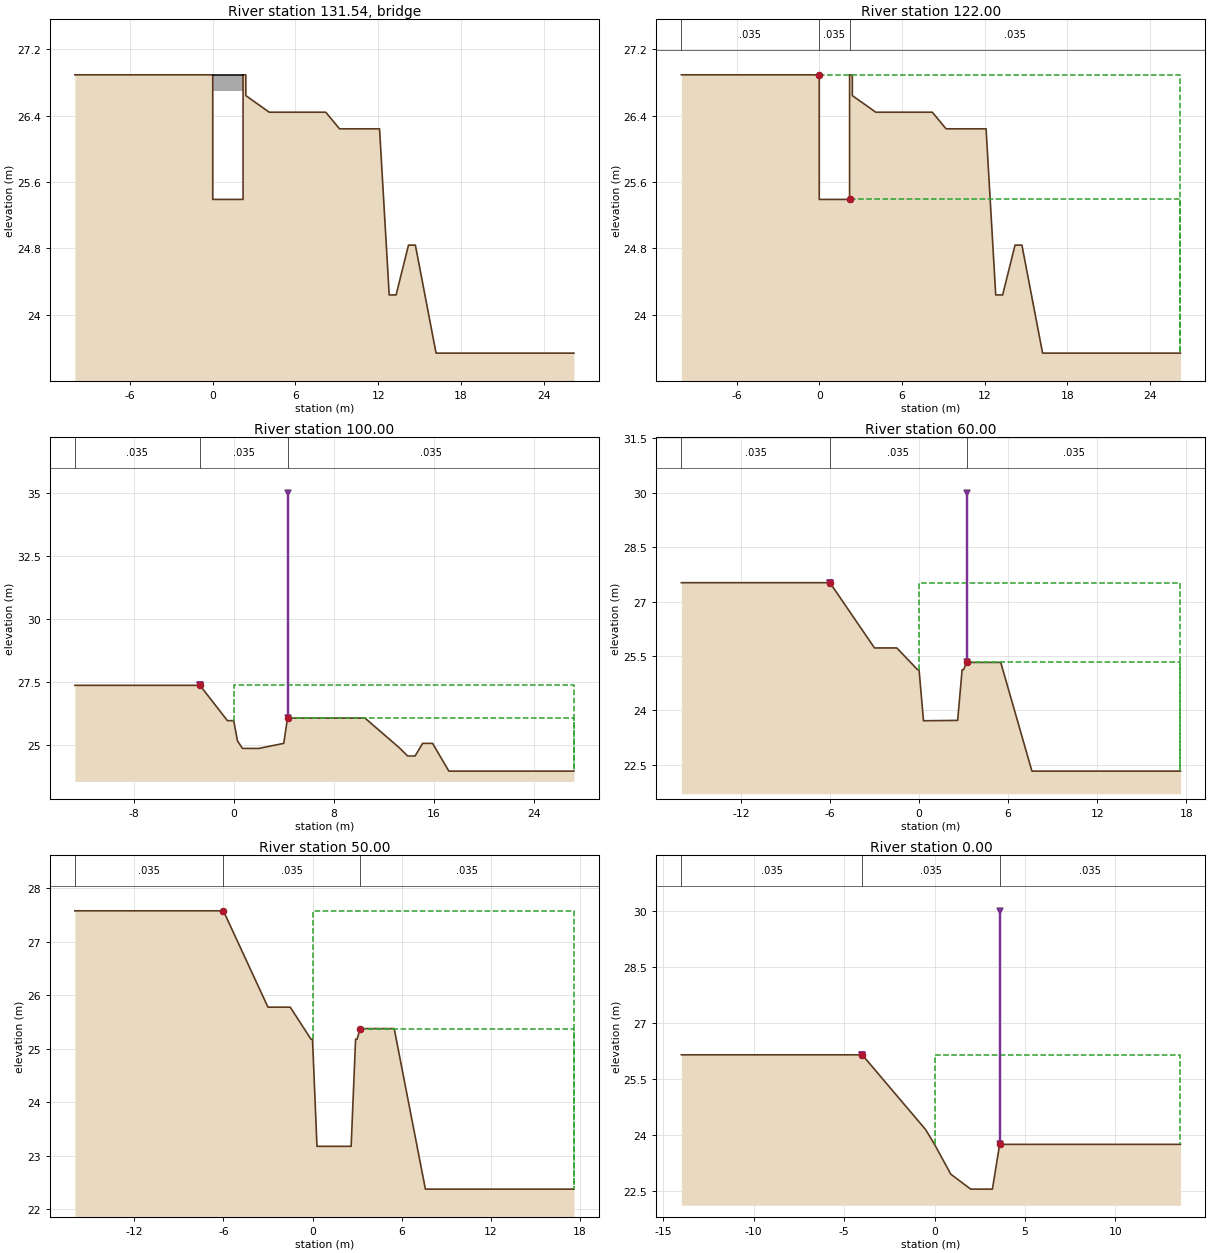
Type RM Length L Ch R = 3 ,131.54  ,,,
BEGIN DESCRIPTION:
2.0315
END DESCRIPTION:
Bridge Culvert--1,0,-1,-1, 0
Deck Dist Width WeirC Skew NumUp NumDn MinLoCord MaxHiCord MaxSubmerge Is_Ogee
.01,6.9,1.44,0, 2, 2, , , .95, 0, 0,0,,
       0     2.2
   26.89   26.89
   26.69   26.69
       0     2.2
   26.89   26.89
   26.69   26.69
BR Coef=-1 , 1 , 0 ,, 0 ,,,.8,-1,1.2,0,
WSPro=,,,, 1 ,,,, 0 ,,,, 0 ,,,,-1 ,-1 ,-1 , 0 , 0 , 0 , 0 , 0
BC Design=,, 0 ,, 0 ,,,,,,

Type RM Length L Ch R = 1 ,122.00  ,22,22,22
BEGIN DESCRIPTION:
2.022
END DESCRIPTION:
#Sta/Elev= 17
     -10   26.89       0   26.89       0   25.39     2.2   25.39     2.2   26.89
     2.4   26.89     2.4   26.64     4.1   26.44     8.2   26.44     9.2   26.24
    12.1   26.24    12.8   24.24    13.3   24.24    14.2   24.84    14.7   24.84
    16.2   23.54    26.2   23.54
#Mann= 3 , 0 , 0
     -10    .035       0       0    .035       0     2.2    .035       0
#XS Ineff= 2 , 0
       0       0   26.89     2.2       0   25.39
Permanent Ineff=
       F       F
Bank Sta=0,2.2
XS Rating Curve= 0
Exp/Cntr=.3,.1

Type RM Length L Ch R = 1 ,100.00  ,40,40,40
BEGIN DESCRIPTION:
2
END DESCRIPTION:
#Sta/Elev= 17
   -12.7   27.37    -2.7   27.37     -.5   25.97       0   25.97      .3   25.17
      .7   24.87       2   24.87       4   25.07     4.3   26.07    10.5   26.07
    13.3   24.87    13.9   24.57    14.5   24.57    15.1   25.07    15.9   25.07
    17.2   23.97    27.2   23.97
#Mann= 3 , 0 , 0
   -12.7    .035       0    -2.7    .035       0     4.3    .035       0
Levee=-1,-2.7,27.37,-1,4.3,35,,
#XS Ineff= 2 , 0
       0    -2.7   27.37     4.3       0   26.07
Permanent Ineff=
       F       F
Bank Sta=-2.7,4.3
XS Rating Curve= 0
Exp/Cntr=.3,.1

Type RM Length L Ch R = 1 ,60.00   ,10,10,10
BEGIN DESCRIPTION:
1.01
END DESCRIPTION:
#Sta/Elev= 14
     -16   27.52      -6   27.52      -3   25.72    -1.5   25.72     -.1   25.12
       0   25.12      .3   23.71     2.6   23.72     2.9   25.12       3   25.12
     3.2   25.32     5.5   25.32     7.6   22.32    17.6   22.32
#Mann= 3 , 0 , 0
     -16    .035       0      -6    .035       0     3.2    .035       0
Levee=-1,-6,27.52,-1,3.2,30,,
#XS Ineff= 2 , 0
       0      -6   27.52     3.2       0   25.32
Permanent Ineff=
       F       F
Bank Sta=-6,3.2
XS Rating Curve= 0
Exp/Cntr=.3,.1

Type RM Length L Ch R = 1 ,50.00   ,50,50,50
BEGIN DESCRIPTION:
1
END DESCRIPTION:
#Sta/Elev= 14
     -16   27.58      -6   27.58      -3   25.78    -1.5   25.78     -.1   25.18
       0   25.18      .3   23.18     2.6   23.18     2.9   25.18       3   25.18
     3.2   25.38     5.5   25.38     7.6   22.38    17.6   22.38
#Mann= 3 , 0 , 0
     -16    .035       0      -6    .035       0     3.2    .035       0
#XS Ineff= 2 , 0
       0      -6   27.58     3.2       0   25.38
Permanent Ineff=
       F       F
Bank Sta=-6,3.2
XS Rating Curve= 0
Exp/Cntr=.3,.1

Type RM Length L Ch R = 1 ,0.00    ,0,0,0
BEGIN DESCRIPTION:
0
END DESCRIPTION:
#Sta/Elev= 9
     -14   26.14      -4   26.14     -.5   24.14       0   23.74      .9   22.94
       2   22.54     3.2   22.54     3.6   23.74    13.6   23.74
#Mann= 3 , 0 , 0
     -14    .035       0      -4    .035       0     3.6    .035       0
Levee=-1,-4,26.14,-1,3.6,30,,
#XS Ineff= 2 , 0
       0      -4   26.14     3.6       0   23.74
Permanent Ineff=
       F       F
Bank Sta=-4,3.6
XS Rating Curve= 0
Exp/Cntr=.3,.1

Chan Stop Cuts=-1