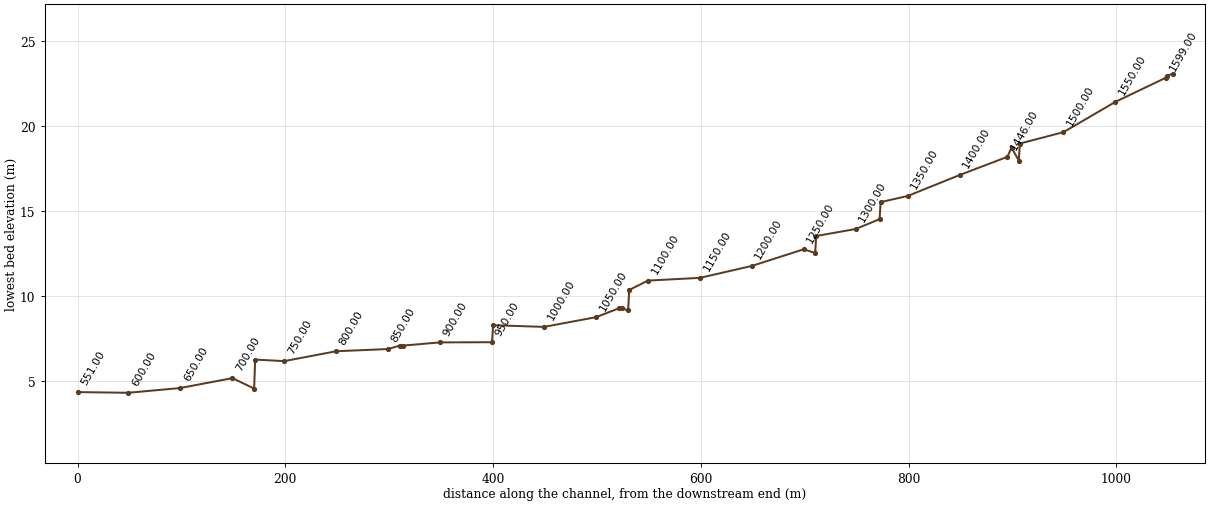
--- kdc.prj (project) ---

Proj Title=kwondong-ch
Current Plan=p01
Default Exp/Contr=.3,.1
SI Units
Geom File=g01
Flow File=f01
Plan File=p01
Y Axis Title=Elevation
X Axis Title(PF)=Main Channel Distance
X Axis Title(XS)=Station
BEGIN DESCRIPTION:
           BACK WATER COMPUTATION
      APPLICATION OF HEC-2 BY Samju Construction Engineering
      °üµ¿Ãµ(¿ËÃµÀ¾): 30,50,80,100,150³âºóµµ °³¼öÀü
END DESCRIPTION:
DSS Export Rating Curves= 0
DSS Export Rating Curve Sorted= 0
DSS Export Volume Flow Curves= 0
DXF OffsetX= 0
DXF OffsetY= 0
DXF ScaleX= 1
DXF ScaleY= 10

--- kdc.p01 (plan) ---

Plan Title=Imported Plan 01
Version=Version 3.0.1  Mar 2001
Short Identifier=Imported Pla
Geom File=g01
Flow File=f01
Subcritical Flow
K Sum by GR= 0
Std Step Tol= 0.003
Critical Tol= 0.003
Num of Std Step Trials= 20
Max Error Tol= 0.1
Flow Tol Ratio= 0.001
Split Flow NTrial= 30
Split Flow Tol= 0.02
Split Flow Ratio= 0.02
Log Output Level= 0
Friction Slope Method= 1
Unsteady Friction Slope Method= 2
Parabolic Critical Depth
Global Vel Dist= 0 , 0 , 0
Global Log Level= 0
CheckData=True
Encroach Param=-1 ,0,0, 0
Computation Interval=1HOUR
Output Interval=1HOUR
Run HTab= 0
Run UNet= 0
Run PostProcess= 0
UNET Theta= 1
UNET ZTol= 0.02
UNET ZSATol= 0.1
UNET MxIter= 20
UNET MaxInSteps= 20
UNET DtIC= 0
UNET DtMin= 0
UNET MaxCRTS= 20
UNET WFStab= 2
UNET SFStab= 1
UNET WFX= 1
UNET SFX= 1
UNET Convert EG Bridges=-1
UNET Use Existing IB Tables=-1
Instantaneous Interval=1HOUR
Write IC File= 0
Write Velocity= 0
Write Detailed= 0

--- kdc.f01 (steady flow) ---

Flow Title=Imported Flow 01
Version=Version 3.0.1  Mar 2001
Number of Profiles= 5
Profile Names=10yr,20yr,30yr,50yr,80yr
River Rch & RM=RIVER-1,Reach-1         ,32.005
    9.15   10.08   10.62   11.31   11.94
River Rch & RM=RIVER-1,Reach-1         ,20
   15.11   16.65   17.56   18.69   19.74
River Rch & RM=kwandong,kwandong        ,1605.00
    9.15   10.08   10.62   11.31   11.94
River Rch & RM=kwandong,kwandong        ,1000.00
   15.11   16.65   17.56   18.69   19.74
Boundary for River Rch & Prof#=kwandong,kwandong        , 1
Up Type= 0
Dn Type= 3
Dn Slope=.0131
Boundary for River Rch & Prof#=kwandong,kwandong        , 2
Up Type= 0
Dn Type= 3
Dn Slope=.0131
Boundary for River Rch & Prof#=kwandong,kwandong        , 3
Up Type= 0
Dn Type= 3
Dn Slope=.0131
Boundary for River Rch & Prof#=kwandong,kwandong        , 4
Up Type= 0
Dn Type= 3
Dn Slope=.0131
Boundary for River Rch & Prof#=kwandong,kwandong        , 5
Up Type= 0
Dn Type= 3
Dn Slope=.0131
DSS Import GetInterval= 0
DSS Import GetPeak= 0
DSS Import FillOption= 0

--- kdc.g01 (geometry) ---

Geom Title=Imported Geom 01
Version=Version 3.0.1  Mar 2001

River Reach=kwandong        ,kwandong
Reach XY= 2
              .5             .95              .5             .05

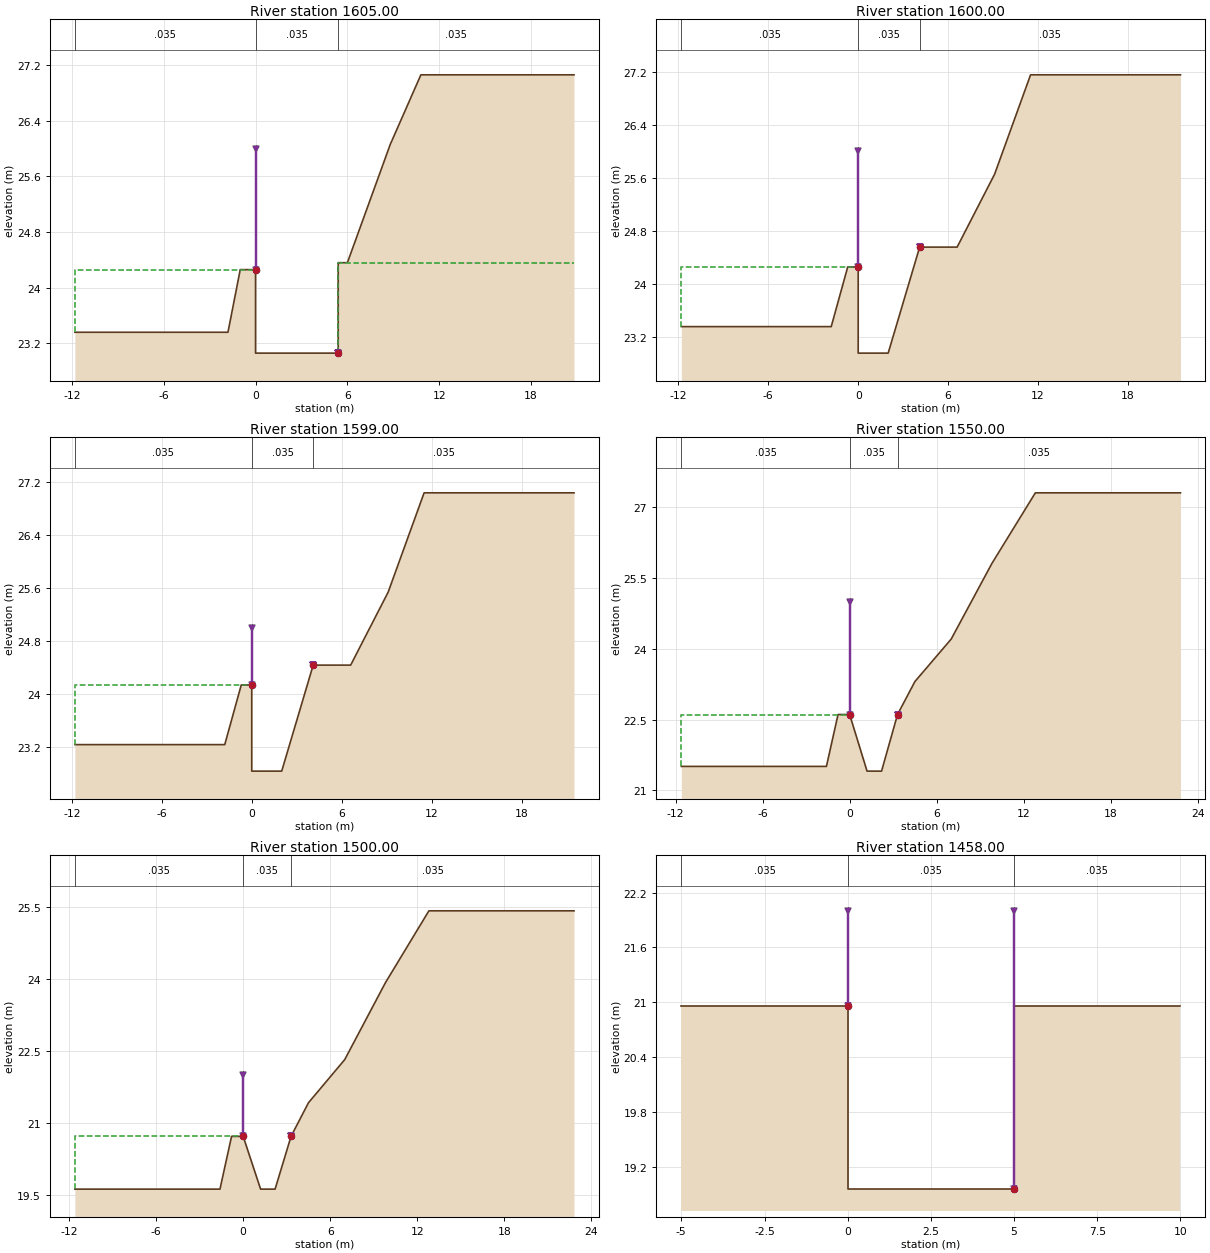
Type RM Length L Ch R = 1 ,1605.00 ,5,5,5
BEGIN DESCRIPTION:
32.005
END DESCRIPTION:
#Sta/Elev= 11
   -11.8   23.36    -1.8   23.36      -1   24.26       0   24.26       0   23.06
     5.4   23.06     5.4   24.36       6   24.36     8.8   26.06    10.8   27.06
    20.8   27.06
#Mann= 3 , 0 , 0
   -11.8    .035       0       0    .035       0     5.4    .035       0
Levee=-1,0,26,-1,5.4,23.06,,
#XS Ineff= 2 , 0
               0   24.26     5.4           24.36
Permanent Ineff=
       F       F
Bank Sta=0,5.4
XS Rating Curve= 0
Exp/Cntr=.3,.1

Type RM Length L Ch R = 1 ,1600.00 ,1,1,1
BEGIN DESCRIPTION:
32
END DESCRIPTION:
#Sta/Elev= 11
   -11.8   23.35    -1.8   23.35     -.7   24.25       0   24.25       0   22.95
       2   22.95     4.1   24.55     6.6   24.55     9.1   25.65    11.5   27.15
    21.5   27.15
#Mann= 3 , 0 , 0
   -11.8    .035       0       0    .035       0     4.1    .035       0
Levee=-1,0,26,-1,4.1,24.55,,
#XS Ineff= 2 , 0
               0   24.25     4.1           24.55
Permanent Ineff=
       F       F
Bank Sta=0,4.1
XS Rating Curve= 0
Exp/Cntr=.3,.1

Type RM Length L Ch R = 1 ,1599.00 ,49,49,49
BEGIN DESCRIPTION:
31.049
END DESCRIPTION:
#Sta/Elev= 11
   -11.8   23.24    -1.8   23.24     -.7   24.14       0   24.14       0   22.84
       2   22.84     4.1   24.44     6.6   24.44     9.1   25.54    11.5   27.04
    21.5   27.04
#Mann= 3 , 0 , 0
   -11.8    .035       0       0    .035       0     4.1    .035       0
Levee=-1,0,25,-1,4.1,24.44,,
#XS Ineff= 2 , 0
               0   24.14     4.1           24.44
Permanent Ineff=
       F       F
Bank Sta=0,4.1
XS Rating Curve= 0
Exp/Cntr=.3,.1

Type RM Length L Ch R = 1 ,1550.00 ,50,50,50
BEGIN DESCRIPTION:
31
END DESCRIPTION:
#Sta/Elev= 12
   -11.6   21.51    -1.6   21.51     -.8   22.61       0   22.61     1.2   21.41
     2.2   21.41     3.3   22.61     4.5   23.31       7   24.21     9.8   25.81
    12.8   27.31    22.8   27.31
#Mann= 3 , 0 , 0
   -11.6    .035       0       0    .035       0     3.3    .035       0
Levee=-1,0,25,-1,3.3,22.61,,
#XS Ineff= 2 , 0
               0   22.61     3.3           22.61
Permanent Ineff=
       F       F
Bank Sta=0,3.3
XS Rating Curve= 0
Exp/Cntr=.3,.1

Type RM Length L Ch R = 1 ,1500.00 ,42,42,42
BEGIN DESCRIPTION:
30
END DESCRIPTION:
#Sta/Elev= 12
   -11.6   19.63    -1.6   19.63     -.8   20.73       0   20.73     1.2   19.63
     2.2   19.63     3.3   20.73     4.5   21.43       7   22.33     9.8   23.93
    12.8   25.43    22.8   25.43
#Mann= 3 , 0 , 0
   -11.6    .035       0       0    .035       0     3.3    .035       0
Levee=-1,0,22,-1,3.3,20.73,,
#XS Ineff= 2 , 0
               0   20.73     3.3           20.73
Permanent Ineff=
       F       F
Bank Sta=0,3.3
XS Rating Curve= 0
Exp/Cntr=.3,.1

Type RM Length L Ch R = 1 ,1458.00 ,1,1,1
BEGIN DESCRIPTION:
29.008
END DESCRIPTION:
#Sta/Elev= 6
      -5   20.96       0   20.96       0   18.96       5   18.96       5   20.96
      10   20.96
#Mann= 3 , 0 , 0
      -5    .035       0       0    .035       0       5    .035       0
Levee=-1,0,22,-1,5,22,,
Bank Sta=0,5
XS Rating Curve= 0
Exp/Cntr=.3,.1

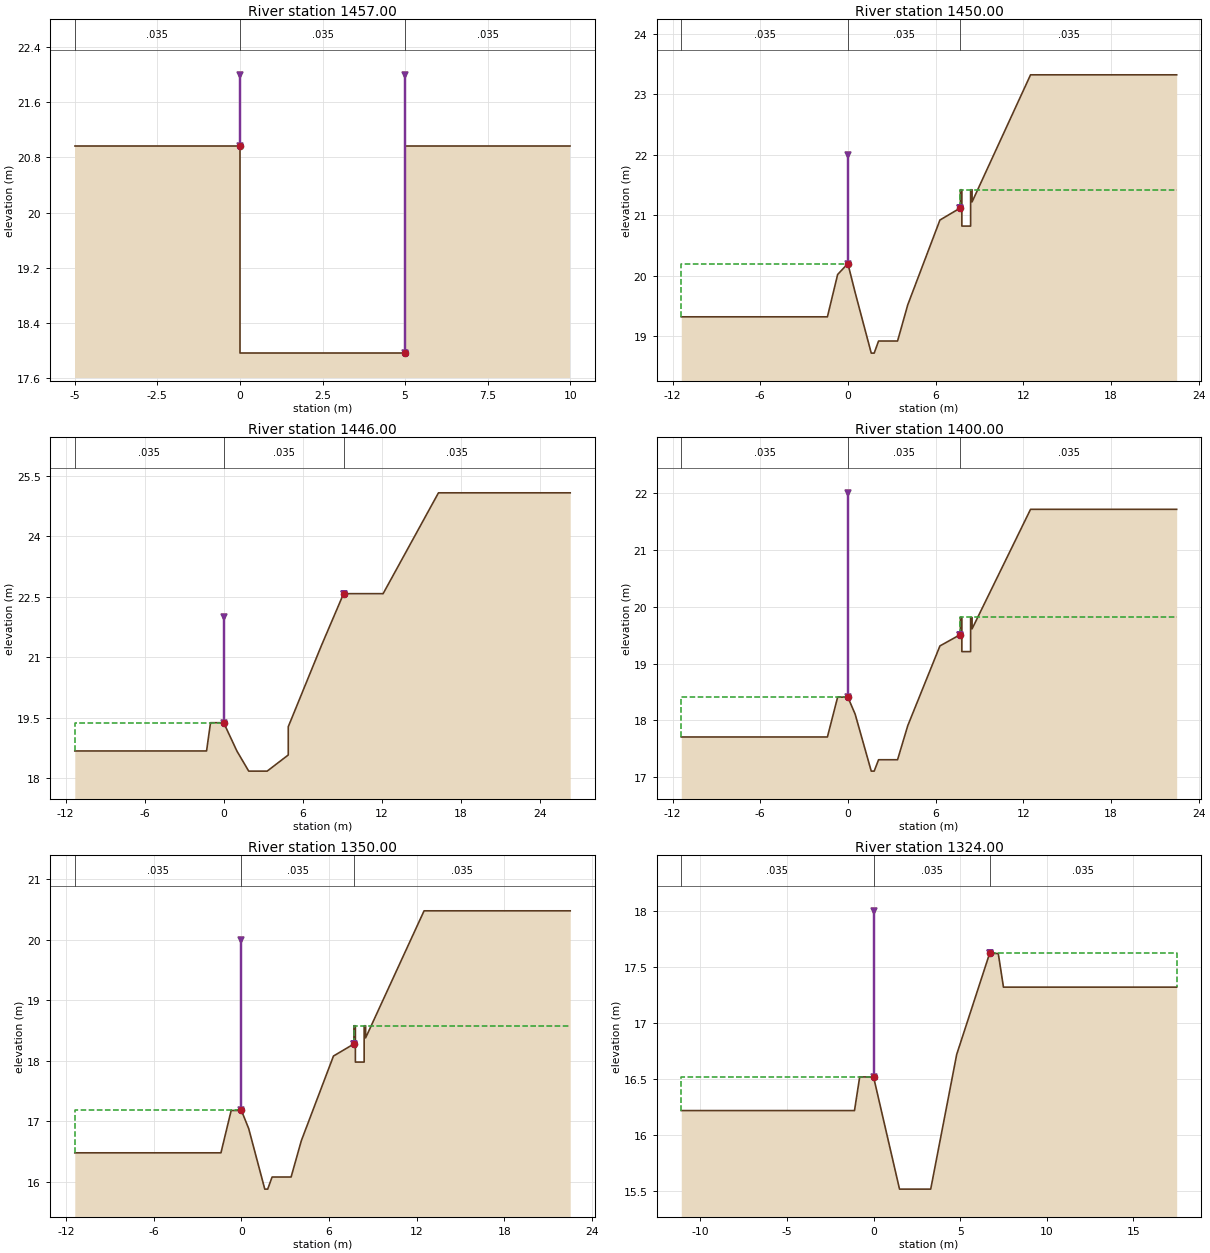
Type RM Length L Ch R = 1 ,1457.00 ,7,7,7
BEGIN DESCRIPTION:
29.007
END DESCRIPTION:
#Sta/Elev= 6
      -5   20.96       0   20.96       0   17.96       5   17.96       5   20.96
      10   20.96
#Mann= 3 , 0 , 0
      -5    .035       0       0    .035       0       5    .035       0
Levee=-1,0,22,-1,5,22,,
Bank Sta=0,5
XS Rating Curve= 0
Exp/Cntr=.3,.1

Type RM Length L Ch R = 1 ,1450.00 ,4,4,4
BEGIN DESCRIPTION:
29
END DESCRIPTION:
#Sta/Elev= 21
   -11.4   19.32    -1.4   19.32     -.7   20.02       0    20.2      .5   19.72
     1.6   18.72     1.8   18.72     2.1   18.92     3.4   18.92     4.1   19.52
     6.3   20.92     7.7   21.12     7.7   21.42     7.8   21.42     7.8   20.82
     8.4   20.82     8.4   21.42     8.5   21.42     8.5   21.22    12.5   23.32
    22.5   23.32
#Mann= 3 , 0 , 0
   -11.4    .035       0       0    .035       0     7.7    .035       0
Levee=-1,0,22,-1,7.7,21.12,,
#XS Ineff= 2 , 0
               0    20.2     7.7           21.42
Permanent Ineff=
       F       F
Bank Sta=0,7.7
XS Rating Curve= 0
Exp/Cntr=.3,.1

Type RM Length L Ch R = 1 ,1446.00 ,46,46,46
BEGIN DESCRIPTION:
28.046
END DESCRIPTION:
#Sta/Elev= 14
   -11.3   18.68    -1.3   18.68      -1   19.38       0   19.38       1   18.68
     1.9   18.18     3.3   18.18     4.9   18.58     4.9   19.28     7.4   21.28
     9.1   22.58    12.1   22.58    16.3   25.08    26.3   25.08
#Mann= 3 , 0 , 0
   -11.3    .035       0       0    .035       0     9.1    .035       0
Levee=-1,0,22,-1,9.1,22.58,,
#XS Ineff= 2 , 0
               0   19.38     9.1           22.58
Permanent Ineff=
       F       F
Bank Sta=0,9.1
XS Rating Curve= 0
Exp/Cntr=.3,.1

Type RM Length L Ch R = 1 ,1400.00 ,50,50,50
BEGIN DESCRIPTION:
28
END DESCRIPTION:
#Sta/Elev= 21
   -11.4   17.71    -1.4   17.71     -.7   18.41       0   18.41      .5   18.11
     1.6   17.11     1.8   17.11     2.1   17.31     3.4   17.31     4.1   17.91
     6.3   19.31     7.7   19.51     7.7   19.81     7.8   19.81     7.8   19.21
     8.4   19.21     8.4   19.81     8.5   19.81     8.5   19.61    12.5   21.71
    22.5   21.71
#Mann= 3 , 0 , 0
   -11.4    .035       0       0    .035       0     7.7    .035       0
Levee=-1,0,22,-1,7.7,19.51,,
#XS Ineff= 2 , 0
               0   18.41     7.7           19.81
Permanent Ineff=
       F       F
Bank Sta=0,7.7
XS Rating Curve= 0
Exp/Cntr=.3,.1

Type RM Length L Ch R = 1 ,1350.00 ,26,26,26
BEGIN DESCRIPTION:
27
END DESCRIPTION:
#Sta/Elev= 21
   -11.4   16.48    -1.4   16.48     -.7   17.18       0   17.18      .5   16.88
     1.6   15.88     1.8   15.88     2.1   16.08     3.4   16.08     4.1   16.68
     6.3   18.08     7.7   18.28     7.7   18.58     7.8   18.58     7.8   17.98
     8.4   17.98     8.4   18.58     8.5   18.58     8.5   18.38    12.5   20.48
    22.5   20.48
#Mann= 3 , 0 , 0
   -11.4    .035       0       0    .035       0     7.7    .035       0
Levee=-1,0,20,-1,7.7,18.28,,
#XS Ineff= 2 , 0
               0   17.18     7.7           18.58
Permanent Ineff=
       F       F
Bank Sta=0,7.7
XS Rating Curve= 0
Exp/Cntr=.3,.1

Type RM Length L Ch R = 1 ,1324.00 ,1,1,1
BEGIN DESCRIPTION:
26.024
END DESCRIPTION:
#Sta/Elev= 11
   -11.1   16.22    -1.1   16.22     -.8   16.52       0   16.52     1.5   15.52
     3.3   15.52     4.8   16.72     6.7   17.62     7.2   17.62     7.5   17.32
    17.5   17.32
#Mann= 3 , 0 , 0
   -11.1    .035       0       0    .035       0     6.7    .035       0
Levee=-1,0,18,-1,6.7,17.62,,
#XS Ineff= 2 , 0
               0   16.52     6.7           17.62
Permanent Ineff=
       F       F
Bank Sta=0,6.7
XS Rating Curve= 0
Exp/Cntr=.3,.1

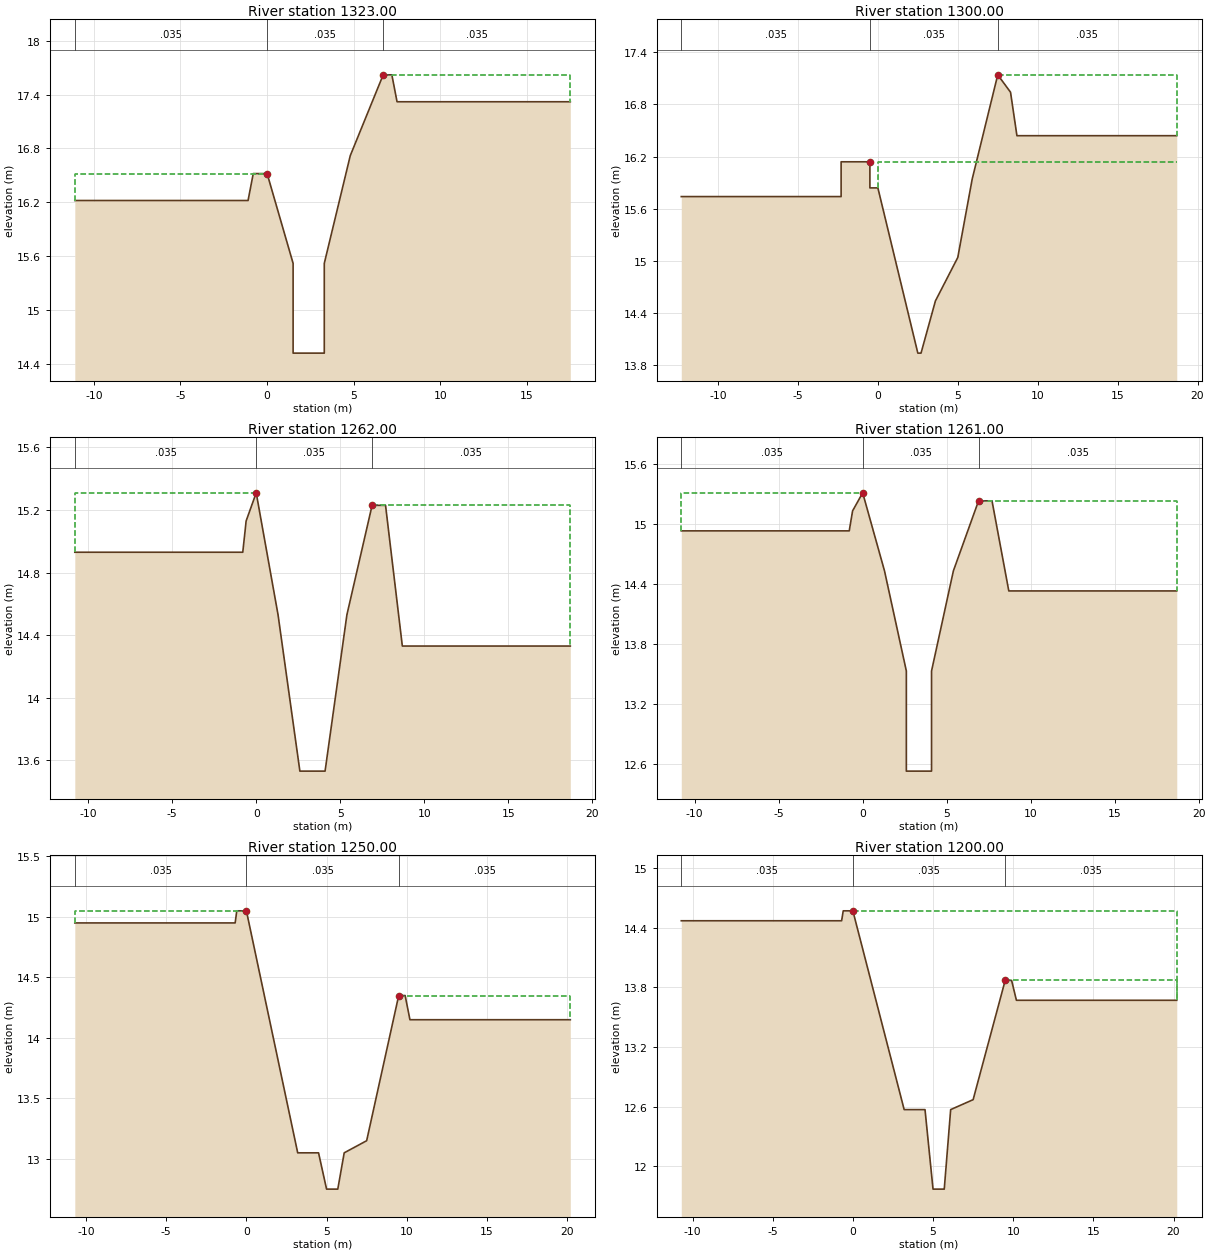
Type RM Length L Ch R = 1 ,1323.00 ,23,23,23
BEGIN DESCRIPTION:
26.023
END DESCRIPTION:
#Sta/Elev= 13
   -11.1   16.22    -1.1   16.22     -.8   16.52       0   16.52     1.5   15.52
     1.5   14.52     3.3   14.52     3.3   15.52     4.8   16.72     6.7   17.62
     7.2   17.62     7.5   17.32    17.5   17.32
#Mann= 3 , 0 , 0
   -11.1    .035       0       0    .035       0     6.7    .035       0
#XS Ineff= 2 , 0
               0   16.52     6.7           17.62
Permanent Ineff=
       F       F
Bank Sta=0,6.7
XS Rating Curve= 0
Exp/Cntr=.3,.1

Type RM Length L Ch R = 1 ,1300.00 ,38,38,38
BEGIN DESCRIPTION:
26
END DESCRIPTION:
#Sta/Elev= 15
   -12.3   15.74    -2.3   15.74    -2.3   16.14     -.5   16.14     -.5   15.84
       0   15.84     2.5   13.94     2.7   13.94     3.6   14.54       5   15.04
     5.9   15.94     7.5   17.14     8.3   16.94     8.7   16.44    18.7   16.44
#Mann= 3 , 0 , 0
   -12.3    .035       0     -.5    .035       0     7.5    .035       0
#XS Ineff= 2 , 0
       0     -.5   16.14     7.5       0   17.14
Permanent Ineff=
       F       F
Bank Sta=-.5,7.5
XS Rating Curve= 0
Exp/Cntr=.3,.1

Type RM Length L Ch R = 1 ,1262.00 ,1,1,1
BEGIN DESCRIPTION:
25.012
END DESCRIPTION:
#Sta/Elev= 12
   -10.8   14.93     -.8   14.93     -.6   15.13       0   15.31     1.3   14.53
     2.6   13.53     4.1   13.53     5.4   14.53     6.9   15.23     7.7   15.23
     8.7   14.33    18.7   14.33
#Mann= 3 , 0 , 0
   -10.8    .035       0       0    .035       0     6.9    .035       0
#XS Ineff= 2 , 0
               0   15.31     6.9           15.23
Permanent Ineff=
       F       F
Bank Sta=0,6.9
XS Rating Curve= 0
Exp/Cntr=.3,.1

Type RM Length L Ch R = 1 ,1261.00 ,11,11,11
BEGIN DESCRIPTION:
25.011
END DESCRIPTION:
#Sta/Elev= 14
   -10.8   14.93     -.8   14.93     -.6   15.13       0   15.31     1.3   14.53
     2.6   13.53     2.6   12.53     4.1   12.53     4.1   13.53     5.4   14.53
     6.9   15.23     7.7   15.23     8.7   14.33    18.7   14.33
#Mann= 3 , 0 , 0
   -10.8    .035       0       0    .035       0     6.9    .035       0
#XS Ineff= 2 , 0
               0   15.31     6.9           15.23
Permanent Ineff=
       F       F
Bank Sta=0,6.9
XS Rating Curve= 0
Exp/Cntr=.3,.1

Type RM Length L Ch R = 1 ,1250.00 ,50,50,50
BEGIN DESCRIPTION:
25
END DESCRIPTION:
#Sta/Elev= 14
   -10.7   14.95     -.7   14.95     -.6   15.05       0   15.05     3.2   13.05
     4.5   13.05       5   12.75     5.7   12.75     6.1   13.05     7.5   13.15
     9.5   14.35     9.9   14.35    10.2   14.15    20.2   14.15
#Mann= 3 , 0 , 0
   -10.7    .035       0       0    .035       0     9.5    .035       0
#XS Ineff= 2 , 0
               0   15.05     9.5           14.35
Permanent Ineff=
       F       F
Bank Sta=0,9.5
XS Rating Curve= 0
Exp/Cntr=.3,.1

Type RM Length L Ch R = 1 ,1200.00 ,50,50,50
BEGIN DESCRIPTION:
24
END DESCRIPTION:
#Sta/Elev= 14
   -10.7   14.47     -.7   14.47     -.6   14.57       0   14.57     3.2   12.57
     4.5   12.57       5   11.77     5.7   11.77     6.1   12.57     7.5   12.67
     9.5   13.87     9.9   13.87    10.2   13.67    20.2   13.67
#Mann= 3 , 0 , 0
   -10.7    .035       0       0    .035       0     9.5    .035       0
#XS Ineff= 2 , 0
       0       0   14.57     9.5       0   13.87
Permanent Ineff=
       F       F
Bank Sta=0,9.5
XS Rating Curve= 0
Exp/Cntr=.3,.1

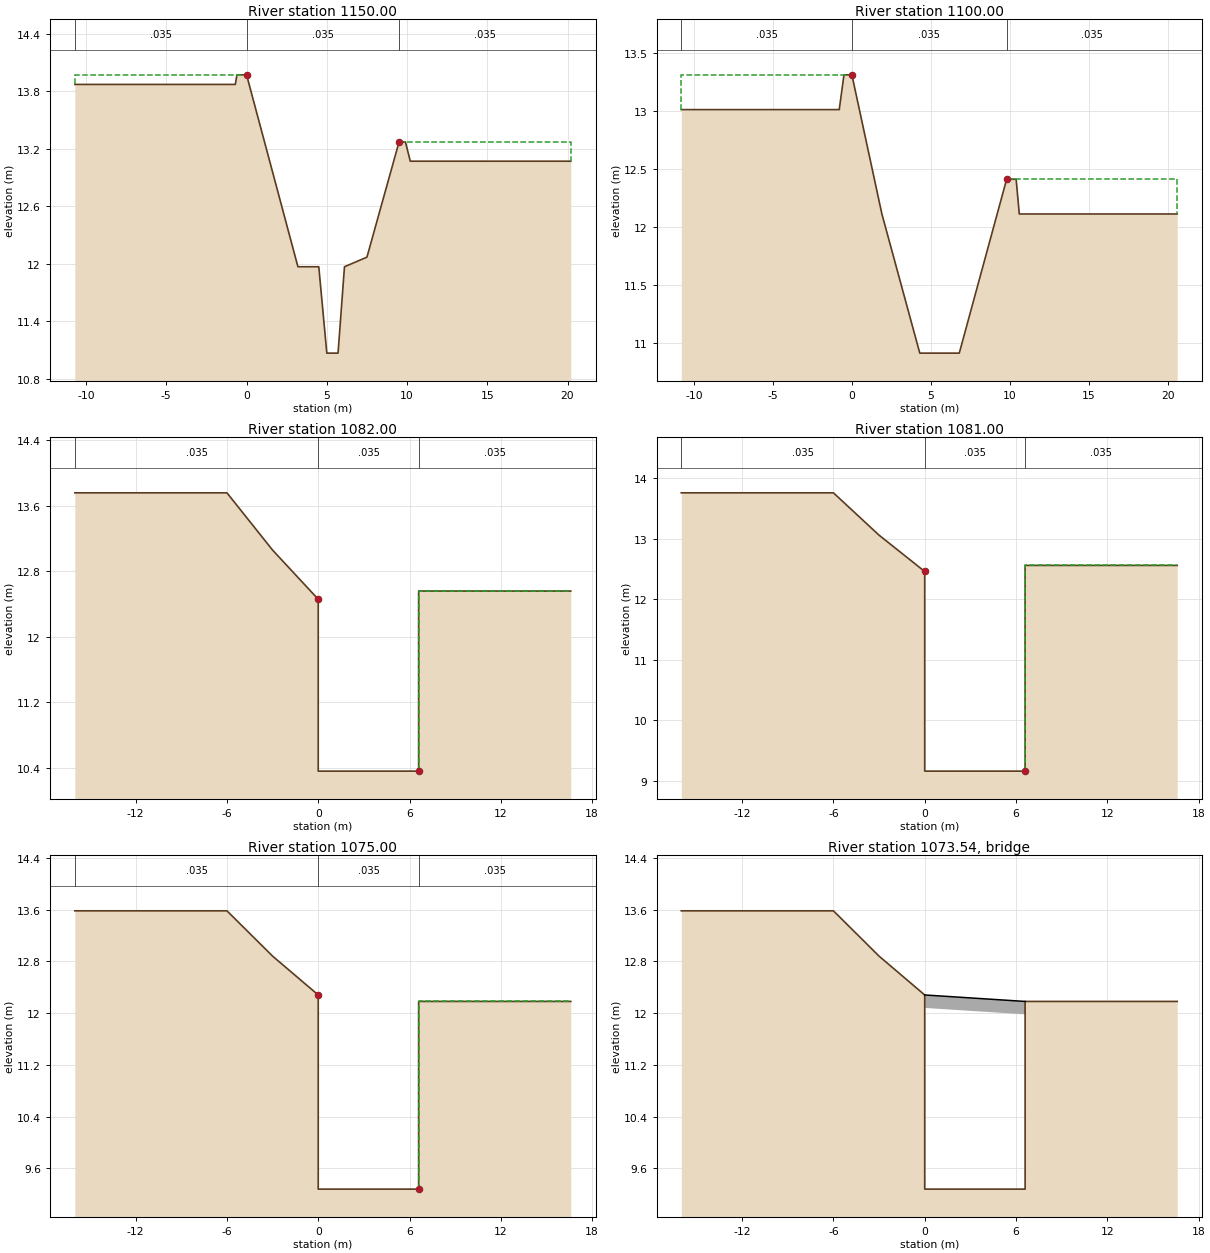
Type RM Length L Ch R = 1 ,1150.00 ,50,50,50
BEGIN DESCRIPTION:
23
END DESCRIPTION:
#Sta/Elev= 14
   -10.7   13.87     -.7   13.87     -.6   13.97       0   13.97     3.2   11.97
     4.5   11.97       5   11.07     5.7   11.07     6.1   11.97     7.5   12.07
     9.5   13.27     9.9   13.27    10.2   13.07    20.2   13.07
#Mann= 3 , 0 , 0
   -10.7    .035       0       0    .035       0     9.5    .035       0
#XS Ineff= 2 , 0
               0   13.97     9.5           13.27
Permanent Ineff=
       F       F
Bank Sta=0,9.5
XS Rating Curve= 0
Exp/Cntr=.3,.1

Type RM Length L Ch R = 1 ,1100.00 ,18,18,18
BEGIN DESCRIPTION:
22
END DESCRIPTION:
#Sta/Elev= 12
   -10.8   13.01     -.8   13.01     -.5   13.31       0   13.31     1.9   12.11
     4.3   10.91     6.8   10.91     9.2   12.11     9.8   12.41    10.4   12.41
    10.6   12.11    20.6   12.11
#Mann= 3 , 0 , 0
   -10.8    .035       0       0    .035       0     9.8    .035       0
#XS Ineff= 2 , 0
               0   13.31     9.8           12.41
Permanent Ineff=
       F       F
Bank Sta=0,9.8
XS Rating Curve= 0
Exp/Cntr=.3,.1

Type RM Length L Ch R = 1 ,1082.00 ,1,1,1
BEGIN DESCRIPTION:
21.032
END DESCRIPTION:
#Sta/Elev= 8
     -16   13.76      -6   13.76      -3   13.06       0   12.46       0   10.36
     6.6   10.36     6.6   12.56    16.6   12.56
#Mann= 3 , 0 , 0
     -16    .035       0       0    .035       0     6.6    .035       0
#XS Ineff= 2 , 0
               0   12.46     6.6           12.56
Permanent Ineff=
       F       F
Bank Sta=0,6.6
XS Rating Curve= 0
Exp/Cntr=.3,.1

Type RM Length L Ch R = 1 ,1081.00 ,6,6,6
BEGIN DESCRIPTION:
21.031
END DESCRIPTION:
#Sta/Elev= 10
     -16   13.76      -6   13.76      -3   13.06       0   12.46       0   10.36
       0    9.16     6.6    9.16     6.6   10.36     6.6   12.56    16.6   12.56
#Mann= 3 , 0 , 0
     -16    .035       0       0    .035       0     6.6    .035       0
#XS Ineff= 2 , 0
               0   12.46     6.6           12.56
Permanent Ineff=
       F       F
Bank Sta=0,6.6
XS Rating Curve= 0
Exp/Cntr=.3,.1

Type RM Length L Ch R = 1 ,1075.00 ,3,3,3
BEGIN DESCRIPTION:
21.025
END DESCRIPTION:
#Sta/Elev= 8
     -16   13.58      -6   13.58      -3   12.88       0   12.28       0    9.28
     6.6    9.28     6.6   12.18    16.6   12.18
#Mann= 3 , 0 , 0
     -16    .035       0       0    .035       0     6.6    .035       0
#XS Ineff= 2 , 0
               0   12.28     6.6           12.18
Permanent Ineff=
       F       F
Bank Sta=0,6.6
XS Rating Curve= 0
Exp/Cntr=.3,.1

Type RM Length L Ch R = 3 ,1073.54 ,,,
BEGIN DESCRIPTION:
21.0235
END DESCRIPTION:
Bridge Culvert--1,0,-1,-1, 0
Deck Dist Width WeirC Skew NumUp NumDn MinLoCord MaxHiCord MaxSubmerge Is_Ogee
.01,2.9,1.44,0, 2, 2, , , .95, 0, 0,0,,
       0     6.6
   12.28   12.18
   12.08   11.98
       0     6.6
   12.28   12.18
   12.08   11.98
BR Coef=-1 , 1 , 0 ,, 0 ,,,.8,-1,1.2,0,
WSPro=,,,, 1 ,,,, 0 ,,,, 0 ,,,,-1 ,-1 ,-1 , 0 , 0 , 0 , 0 , 0
BC Design=,, 0 ,, 0 ,,,,,,

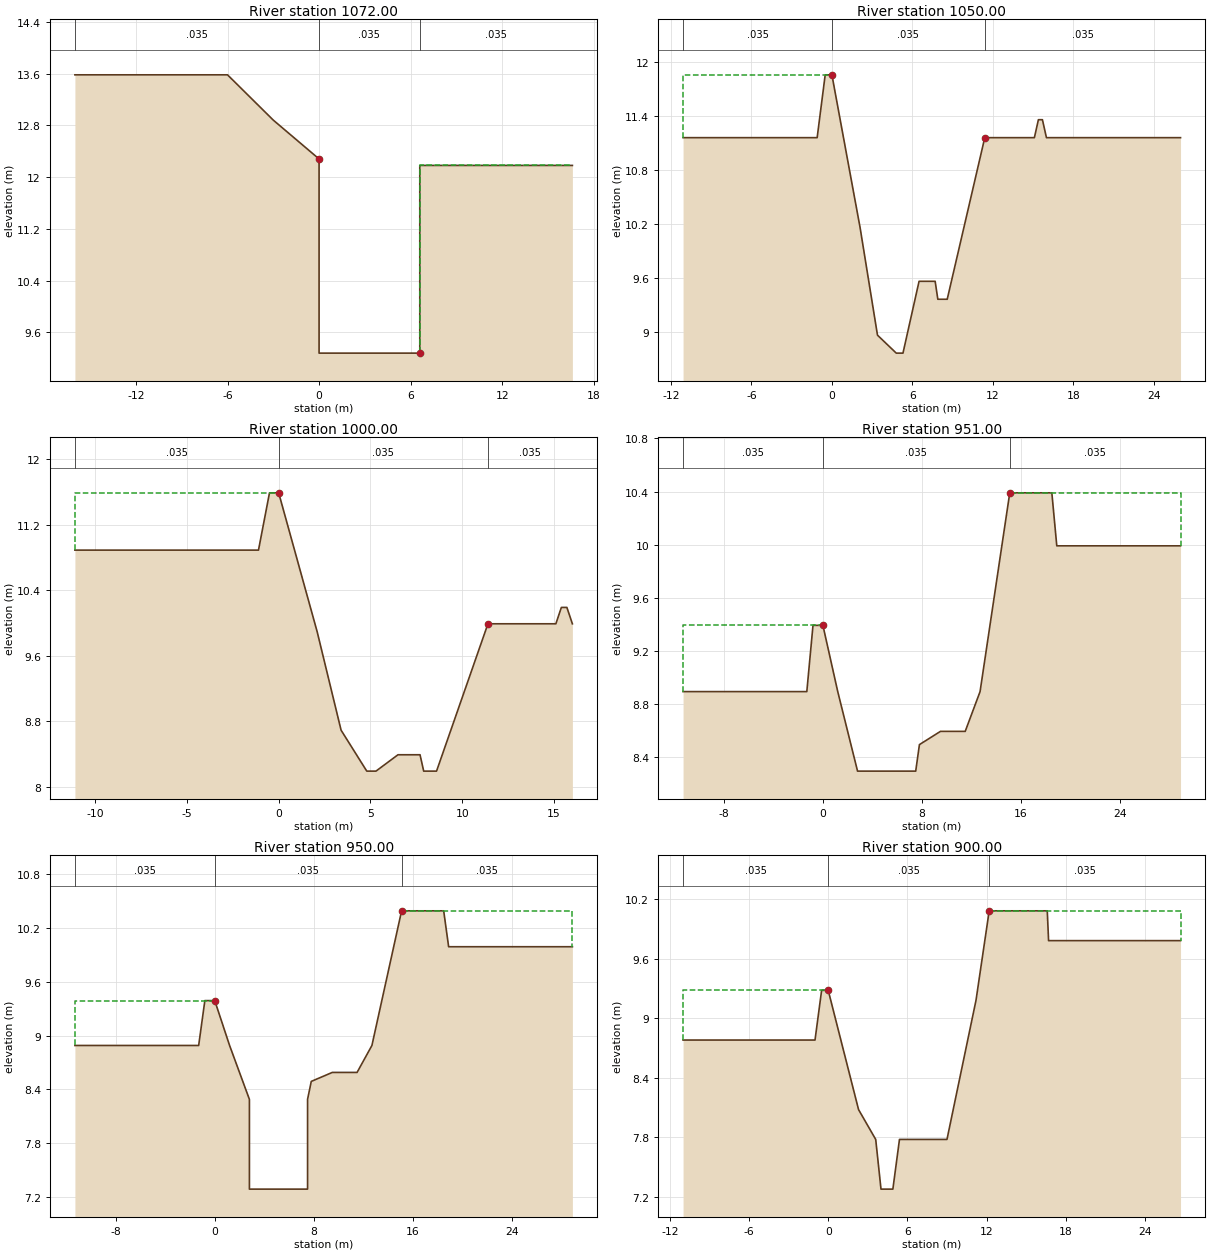
Type RM Length L Ch R = 1 ,1072.00 ,22,22,22
BEGIN DESCRIPTION:
21.022
END DESCRIPTION:
#Sta/Elev= 8
     -16   13.58      -6   13.58      -3   12.88       0   12.28       0    9.28
     6.6    9.28     6.6   12.18    16.6   12.18
#Mann= 3 , 0 , 0
     -16    .035       0       0    .035       0     6.6    .035       0
#XS Ineff= 2 , 0
               0   12.28     6.6           12.18
Permanent Ineff=
       F       F
Bank Sta=0,6.6
XS Rating Curve= 0
Exp/Cntr=.3,.1

Type RM Length L Ch R = 1 ,1050.00 ,50,50,50
BEGIN DESCRIPTION:
21
END DESCRIPTION:
#Sta/Elev= 20
   -11.1   11.16    -1.1   11.16     -.5   11.86       0   11.86     2.1   10.16
     3.4    8.96     4.8    8.76     5.3    8.76     6.5    9.56     7.7    9.56
     7.9    9.36     8.6    9.36    11.4   11.16    11.8   11.16    14.8   11.16
    15.1   11.16    15.4   11.36    15.7   11.36      16   11.16      26   11.16
#Mann= 3 , 0 , 0
   -11.1    .035       0       0    .035       0    11.4    .035       0
#XS Ineff= 2 , 0
               0   11.86    11.4           11.16
Permanent Ineff=
       F       F
Bank Sta=0,11.4
XS Rating Curve= 0
Exp/Cntr=.3,.1

Type RM Length L Ch R = 1 ,1000.00 ,49,49,49
BEGIN DESCRIPTION:
20
END DESCRIPTION:
#Sta/Elev= 19
   -11.1   10.89    -1.1   10.89     -.5   11.59       0   11.59     2.1    9.89
     3.4    8.69     4.8    8.19     5.3    8.19     6.5    8.39     7.7    8.39
     7.9    8.19     8.6    8.19    11.4    9.99    11.8    9.99    14.8    9.99
    15.1    9.99    15.4   10.19    15.7   10.19      16    9.99
#Mann= 3 , 0 , 0
   -11.1    .035       0       0    .035       0    11.4    .035       0
#XS Ineff= 2 , 0
               0   11.59    11.4            9.99
Permanent Ineff=
       F       F
Bank Sta=0,11.4
XS Rating Curve= 0
Exp/Cntr=.3,.1

Type RM Length L Ch R = 1 ,951.00  ,1,1,1
BEGIN DESCRIPTION:
19.001
END DESCRIPTION:
#Sta/Elev= 16
   -11.3    8.89    -1.3    8.89     -.8    9.39       0    9.39     1.2    8.89
     2.8    8.29     7.5    8.29     7.8    8.49     9.5    8.59    11.5    8.59
    12.7    8.89    15.1   10.39    15.5   10.39    18.5   10.39    18.9    9.99
    28.9    9.99
#Mann= 3 , 0 , 0
   -11.3    .035       0       0    .035       0    15.1    .035       0
#XS Ineff= 2 , 0
               0    9.39    15.1           10.39
Permanent Ineff=
       F       F
Bank Sta=0,15.1
XS Rating Curve= 0
Exp/Cntr=.3,.1

Type RM Length L Ch R = 1 ,950.00  ,50,50,50
BEGIN DESCRIPTION:
19
END DESCRIPTION:
#Sta/Elev= 18
   -11.3    8.89    -1.3    8.89     -.8    9.39       0    9.39     1.2    8.89
     2.8    8.29     2.8    7.29     7.5    7.29     7.5    8.29     7.8    8.49
     9.5    8.59    11.5    8.59    12.7    8.89    15.1   10.39    15.5   10.39
    18.5   10.39    18.9    9.99    28.9    9.99
#Mann= 3 , 0 , 0
   -11.3    .035       0       0    .035       0    15.1    .035       0
#XS Ineff= 2 , 0
               0    9.39    15.1           10.39
Permanent Ineff=
       F       F
Bank Sta=0,15.1
XS Rating Curve= 0
Exp/Cntr=.3,.1

Type RM Length L Ch R = 1 ,900.00  ,36,36,36
BEGIN DESCRIPTION:
18
END DESCRIPTION:
#Sta/Elev= 17
     -11    8.78      -1    8.78     -.5    9.28       0    9.28     2.3    8.08
     3.6    7.78       4    7.28     4.9    7.28     5.4    7.78       9    7.78
    11.2    9.18    12.2   10.08      13   10.08      16   10.08    16.6   10.08
    16.7    9.78    26.7    9.78
#Mann= 3 , 0 , 0
     -11    .035       0       0    .035       0    12.2    .035       0
#XS Ineff= 2 , 0
               0    9.28    12.2           10.08
Permanent Ineff=
       F       F
Bank Sta=0,12.2
XS Rating Curve= 0
Exp/Cntr=.3,.1

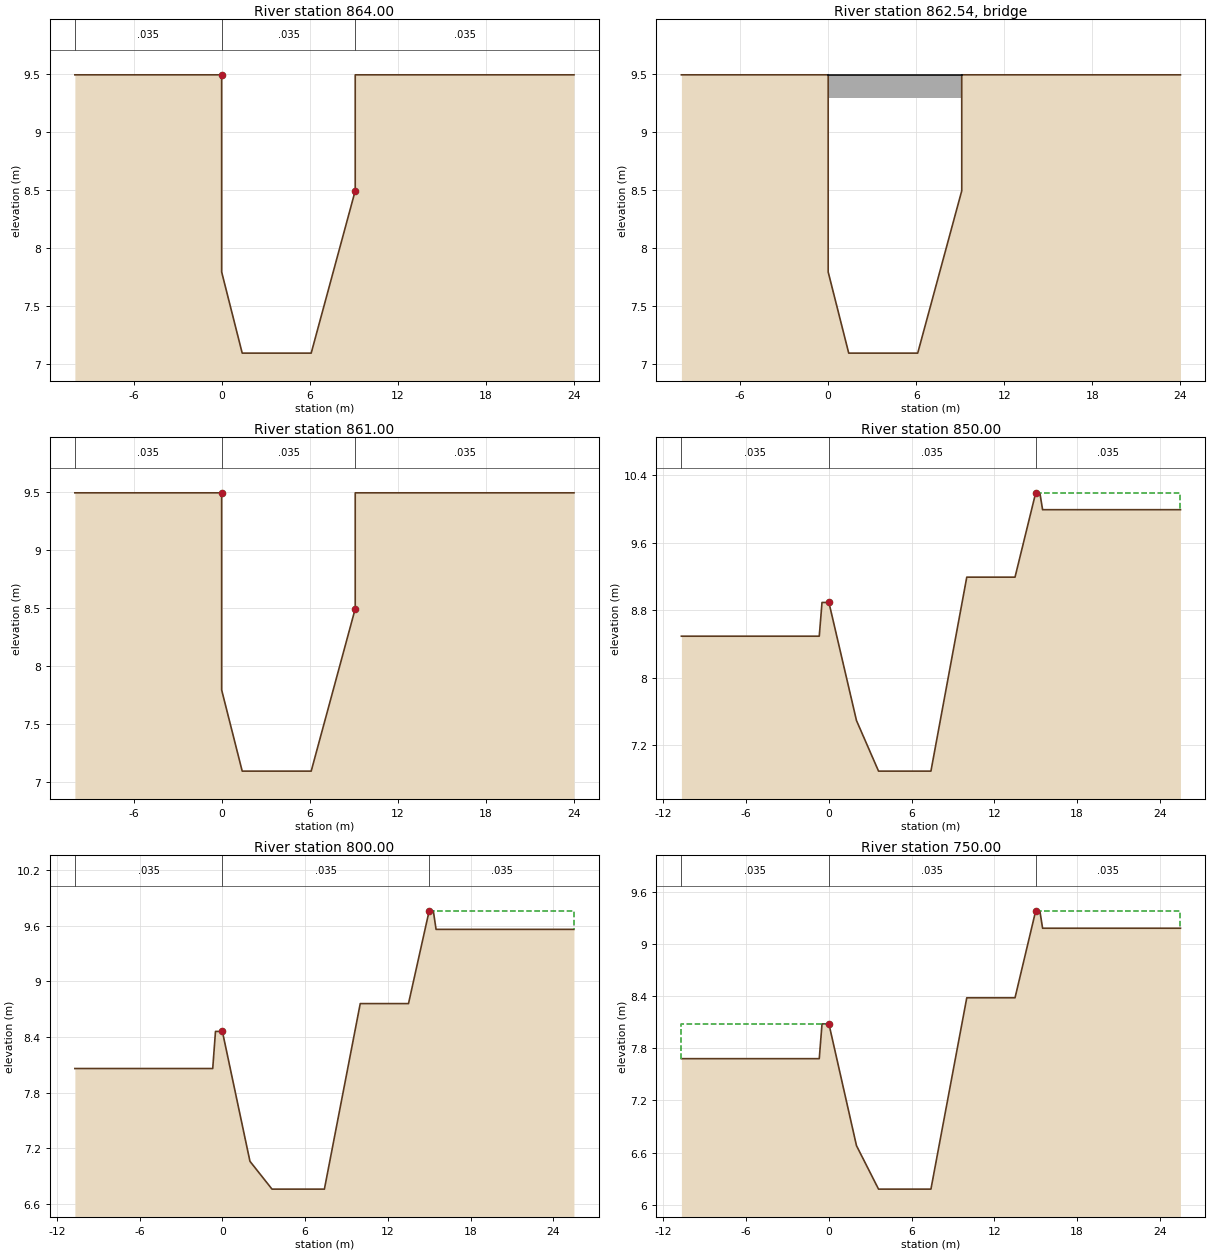
Type RM Length L Ch R = 1 ,864.00  ,3,3,3
BEGIN DESCRIPTION:
17.014
END DESCRIPTION:
#Sta/Elev= 8
     -10    9.49       0    9.49       0    7.79     1.4    7.09     6.1    7.09
     9.1    8.49     9.1    9.49      24    9.49
#Mann= 3 , 0 , 0
     -10    .035       0       0    .035       0     9.1    .035       0
#XS Ineff= 2 , 0
       0       0    9.49     9.1       0    8.49
Permanent Ineff=
       F       F
Bank Sta=0,9.1
XS Rating Curve= 0
Exp/Cntr=.3,.1

Type RM Length L Ch R = 3 ,862.54  ,,,
BEGIN DESCRIPTION:
17.0125
END DESCRIPTION:
Bridge Culvert--1,0,-1,-1, 0
Deck Dist Width WeirC Skew NumUp NumDn MinLoCord MaxHiCord MaxSubmerge Is_Ogee
.01,2.9,1.44,0, 2, 2, , , .95, 0, 0,0,,
       0     9.1
    9.49    9.49
    9.29    9.29
       0     9.1
    9.49    9.49
    9.29    9.29
BR Coef=-1 , 1 , 0 ,, 0 ,,,.8,-1,1.2,0,
WSPro=,,,, 1 ,,,, 0 ,,,, 0 ,,,,-1 ,-1 ,-1 , 0 , 0 , 0 , 0 , 0
BC Design=,, 0 ,, 0 ,,,,,,

Type RM Length L Ch R = 1 ,861.00  ,11,11,11
BEGIN DESCRIPTION:
17.011
END DESCRIPTION:
#Sta/Elev= 8
     -10    9.49       0    9.49       0    7.79     1.4    7.09     6.1    7.09
     9.1    8.49     9.1    9.49      24    9.49
#Mann= 3 , 0 , 0
     -10    .035       0       0    .035       0     9.1    .035       0
#XS Ineff= 2 , 0
       0       0    9.49     9.1       0    8.49
Permanent Ineff=
       F       F
Bank Sta=0,9.1
XS Rating Curve= 0
Exp/Cntr=.3,.1

Type RM Length L Ch R = 1 ,850.00  ,50,50,50
BEGIN DESCRIPTION:
17
END DESCRIPTION:
#Sta/Elev= 14
   -10.7    8.49     -.7    8.49     -.5    8.89       0    8.89       2    7.49
     3.6    6.89     7.4    6.89      10    9.19    10.5    9.19    13.5    9.19
      15   10.19    15.3   10.19    15.5    9.99    25.5    9.99
#Mann= 3 , 0 , 0
   -10.7    .035       0       0    .035       0      15    .035       0
#XS Ineff= 2 , 0
       0       0    8.89      15       0   10.19
Permanent Ineff=
       F       F
Bank Sta=0,15
XS Rating Curve= 0
Exp/Cntr=.3,.1

Type RM Length L Ch R = 1 ,800.00  ,50,50,50
BEGIN DESCRIPTION:
16
END DESCRIPTION:
#Sta/Elev= 14
   -10.7    8.06     -.7    8.06     -.5    8.46       0    8.46       2    7.06
     3.6    6.76     7.4    6.76      10    8.76    10.5    8.76    13.5    8.76
      15    9.76    15.3    9.76    15.5    9.56    25.5    9.56
#Mann= 3 , 0 , 0
   -10.7    .035       0       0    .035       0      15    .035       0
#XS Ineff= 2 , 0
       0       0    8.46      15       0    9.76
Permanent Ineff=
       F       F
Bank Sta=0,15
XS Rating Curve= 0
Exp/Cntr=.3,.1

Type RM Length L Ch R = 1 ,750.00  ,28,28,28
BEGIN DESCRIPTION:
15
END DESCRIPTION:
#Sta/Elev= 14
   -10.7    7.68     -.7    7.68     -.5    8.08       0    8.08       2    6.68
     3.6    6.18     7.4    6.18      10    8.38    10.5    8.38    13.5    8.38
      15    9.38    15.3    9.38    15.5    9.18    25.5    9.18
#Mann= 3 , 0 , 0
   -10.7    .035       0       0    .035       0      15    .035       0
#XS Ineff= 2 , 0
               0    8.08      15            9.38
Permanent Ineff=
       F       F
Bank Sta=0,15
XS Rating Curve= 0
Exp/Cntr=.3,.1

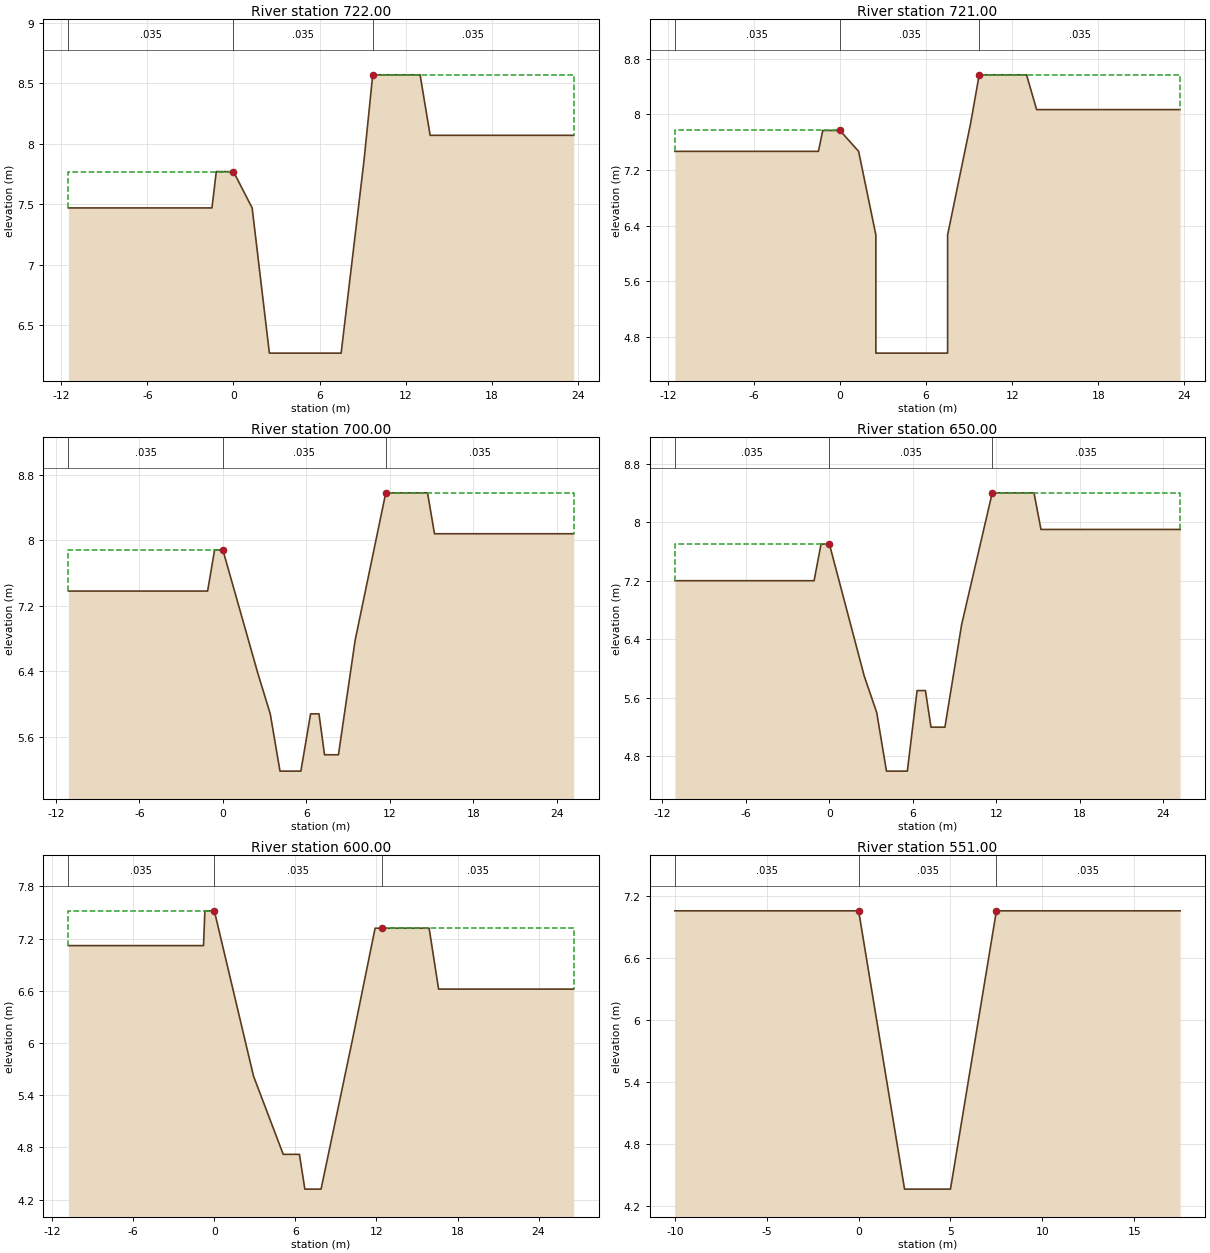
Type RM Length L Ch R = 1 ,722.00  ,1,1,1
BEGIN DESCRIPTION:
14.022
END DESCRIPTION:
#Sta/Elev= 13
   -11.5    7.47    -1.5    7.47    -1.2    7.77       0    7.77     1.3    7.47
     2.5    6.27     7.5    6.27     9.1    7.87     9.7    8.57      10    8.57
      13    8.57    13.7    8.07    23.7    8.07
#Mann= 3 , 0 , 0
   -11.5    .035       0       0    .035       0     9.7    .035       0
#XS Ineff= 2 , 0
               0    7.77     9.7            8.57
Permanent Ineff=
       F       F
Bank Sta=0,9.7
XS Rating Curve= 0
Exp/Cntr=.3,.1

Type RM Length L Ch R = 1 ,721.00  ,21,21,21
BEGIN DESCRIPTION:
14.021
END DESCRIPTION:
#Sta/Elev= 15
   -11.5    7.47    -1.5    7.47    -1.2    7.77       0    7.77     1.3    7.47
     2.5    6.27     2.5    4.57     7.5    4.57     7.5    6.27     9.1    7.87
     9.7    8.57      10    8.57      13    8.57    13.7    8.07    23.7    8.07
#Mann= 3 , 0 , 0
   -11.5    .035       0       0    .035       0     9.7    .035       0
#XS Ineff= 2 , 0
               0    7.77     9.7            8.57
Permanent Ineff=
       F       F
Bank Sta=0,9.7
XS Rating Curve= 0
Exp/Cntr=.3,.1

Type RM Length L Ch R = 1 ,700.00  ,50,50,50
BEGIN DESCRIPTION:
14
END DESCRIPTION:
#Sta/Elev= 17
   -11.1    7.38    -1.1    7.38     -.6    7.88       0    7.88     2.5    6.38
     3.4    5.88     4.1    5.18     5.6    5.18     6.3    5.88     6.9    5.88
     7.3    5.38     8.3    5.38     9.5    6.78    11.7    8.58    14.7    8.58
    15.2    8.08    25.2    8.08
#Mann= 3 , 0 , 0
   -11.1    .035       0       0    .035       0    11.7    .035       0
#XS Ineff= 2 , 0
               0    7.88    11.7            8.58
Permanent Ineff=
       F       F
Bank Sta=0,11.7
XS Rating Curve= 0
Exp/Cntr=.3,.1

Type RM Length L Ch R = 1 ,650.00  ,50,50,50
BEGIN DESCRIPTION:
13
END DESCRIPTION:
#Sta/Elev= 17
   -11.1     7.2    -1.1     7.2     -.6     7.7       0     7.7     2.5     5.9
     3.4     5.4     4.1     4.6     5.6     4.6     6.3     5.7     6.9     5.7
     7.3     5.2     8.3     5.2     9.5     6.6    11.7     8.4    14.7     8.4
    15.2     7.9    25.2     7.9
#Mann= 3 , 0 , 0
   -11.1    .035       0       0    .035       0    11.7    .035       0
#XS Ineff= 2 , 0
               0     7.7    11.7             8.4
Permanent Ineff=
       F       F
Bank Sta=0,11.7
XS Rating Curve= 0
Exp/Cntr=.3,.1

Type RM Length L Ch R = 1 ,600.00  ,49,49,49
BEGIN DESCRIPTION:
12
END DESCRIPTION:
#Sta/Elev= 16
   -10.8    7.12     -.8    7.12     -.7    7.52       0    7.52     2.9    5.62
     5.1    4.72     6.3    4.72     6.7    4.32     7.9    4.32    10.2    6.02
    11.9    7.32    12.4    7.32    15.4    7.32    15.9    7.32    16.6    6.62
    26.6    6.62
#Mann= 3 , 0 , 0
   -10.8    .035       0       0    .035       0    12.4    .035       0
#XS Ineff= 2 , 0
               0    7.52    12.4            7.32
Permanent Ineff=
       F       F
Bank Sta=0,12.4
XS Rating Curve= 0
Exp/Cntr=.3,.1

Type RM Length L Ch R = 1 ,551.00  ,1,1,1
BEGIN DESCRIPTION:
11.001
END DESCRIPTION:
#Sta/Elev= 6
     -10    7.06       0    7.06     2.5    4.36       5    4.36     7.5    7.06
    17.5    7.06
#Mann= 3 , 0 , 0
     -10    .035       0       0    .035       0     7.5    .035       0
#XS Ineff= 2 , 0
               0    7.06     7.5            7.06
Permanent Ineff=
       F       F
Bank Sta=0,7.5
XS Rating Curve= 0
Exp/Cntr=.3,.1