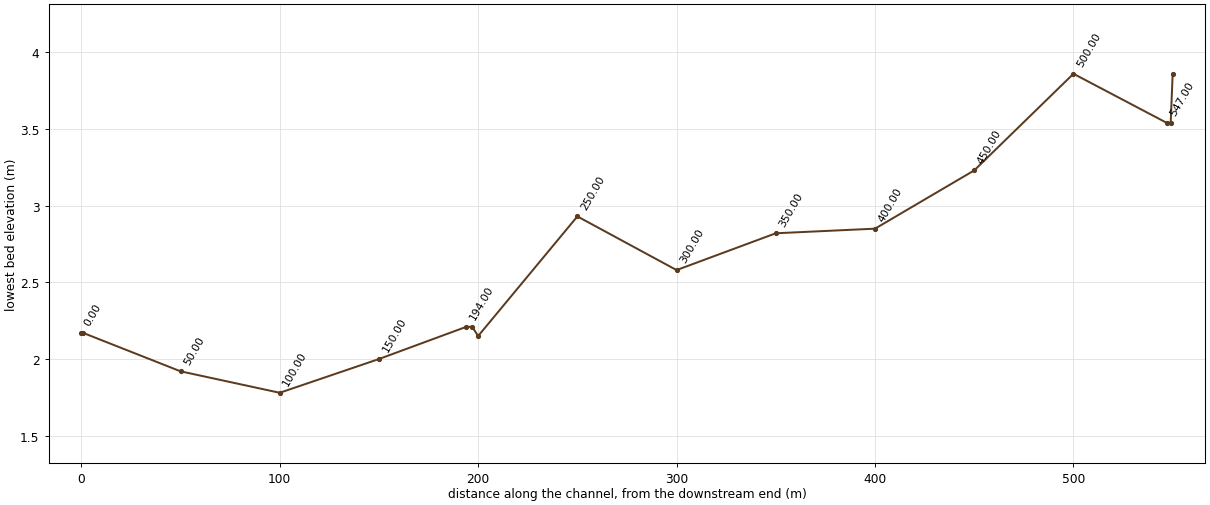
HEC-RAS study kdc.prj: kwondong-ch

--- kdc.g01 (geometry) --- (continued)

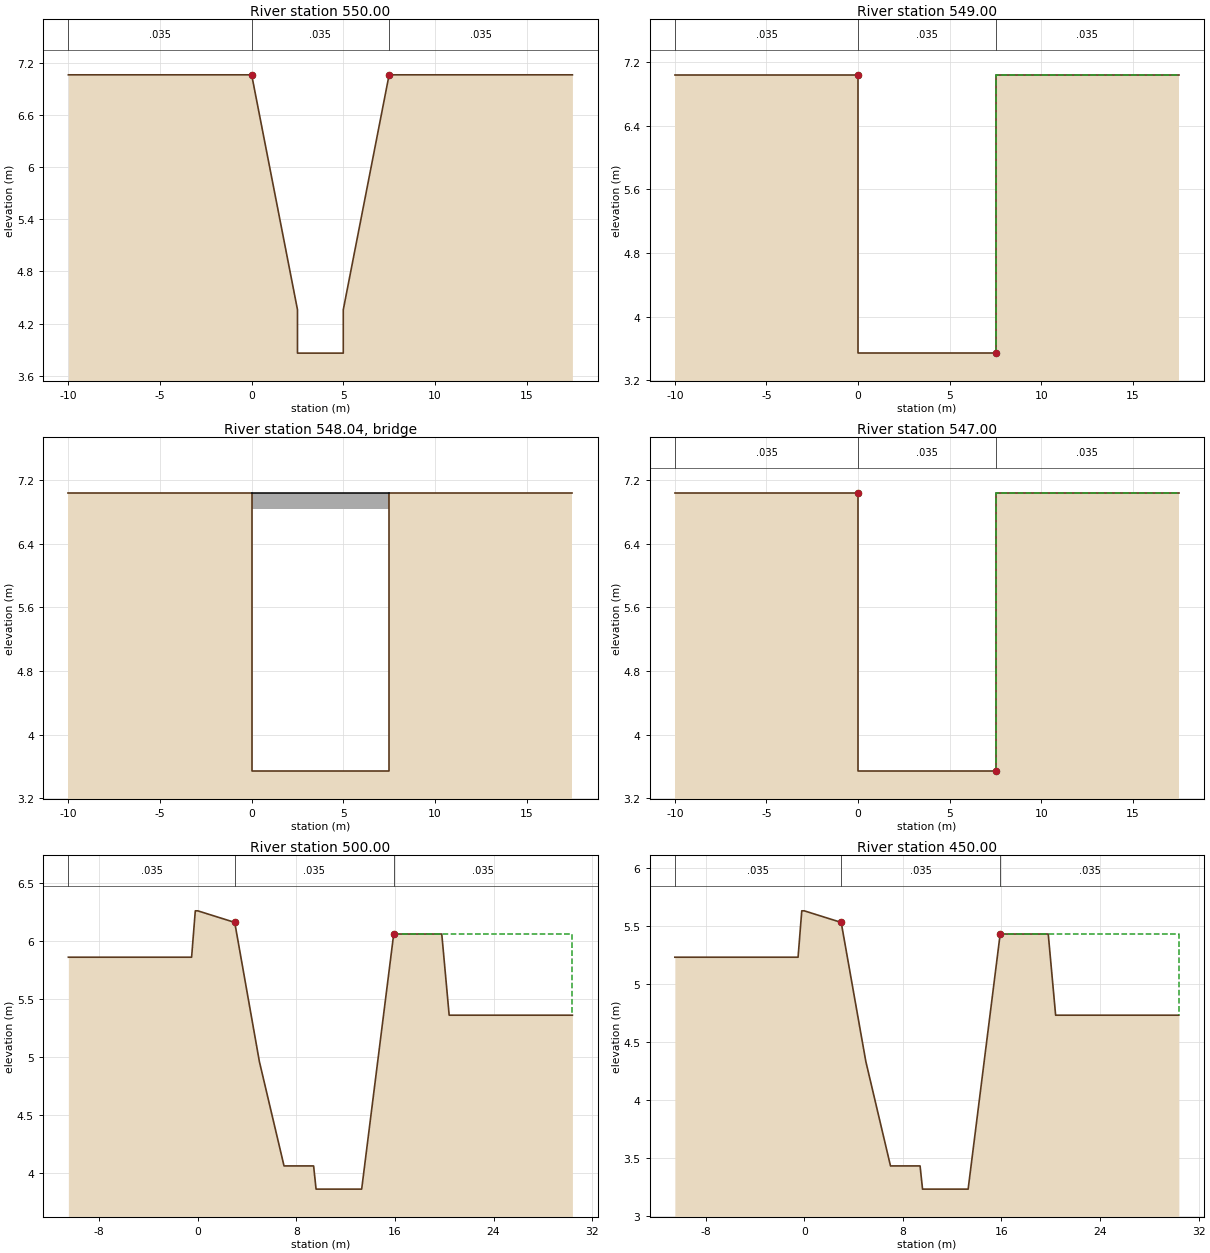
Type RM Length L Ch R = 1 ,550.00  ,1,1,1
BEGIN DESCRIPTION:
11
END DESCRIPTION:
#Sta/Elev= 8
     -10    7.06       0    7.06     2.5    4.36     2.5    3.86       5    3.86
       5    4.36     7.5    7.06    17.5    7.06
#Mann= 3 , 0 , 0
     -10    .035       0       0    .035       0     7.5    .035       0
#XS Ineff= 2 , 0
               0    7.06     7.5            7.06
Permanent Ineff=
       F       F
Bank Sta=0,7.5
XS Rating Curve= 0
Exp/Cntr=.3,.1

Type RM Length L Ch R = 1 ,549.00  ,2,2,2
BEGIN DESCRIPTION:
10.049
END DESCRIPTION:
#Sta/Elev= 6
     -10    7.04       0    7.04       0    3.54     7.5    3.54     7.5    7.04
    17.5    7.04
#Mann= 3 , 0 , 0
     -10    .035       0       0    .035       0     7.5    .035       0
#XS Ineff= 2 , 0
               0    7.04     7.5            7.04
Permanent Ineff=
       F       F
Bank Sta=0,7.5
XS Rating Curve= 0
Exp/Cntr=.3,.1

Type RM Length L Ch R = 3 ,548.04  ,,,
BEGIN DESCRIPTION:
10.048
END DESCRIPTION:
Bridge Culvert--1,0,-1,-1, 0
Deck Dist Width WeirC Skew NumUp NumDn MinLoCord MaxHiCord MaxSubmerge Is_Ogee
.01,1.9,1.44,0, 2, 2, , , .95, 0, 0,0,,
       0     7.5
    7.04    7.04
    6.84    6.84
       0     7.5
    7.04    7.04
    6.84    6.84
BR Coef=-1 , 1 , 0 ,, 0 ,,,.8,-1,1.2,0,
WSPro=,,,, 1 ,,,, 0 ,,,, 0 ,,,,-1 ,-1 ,-1 , 0 , 0 , 0 , 0 , 0
BC Design=,, 0 ,, 0 ,,,,,,

Type RM Length L Ch R = 1 ,547.00  ,47,47,47
BEGIN DESCRIPTION:
10.047
END DESCRIPTION:
#Sta/Elev= 6
     -10    7.04       0    7.04       0    3.54     7.5    3.54     7.5    7.04
    17.5    7.04
#Mann= 3 , 0 , 0
     -10    .035       0       0    .035       0     7.5    .035       0
#XS Ineff= 2 , 0
               0    7.04     7.5            7.04
Permanent Ineff=
       F       F
Bank Sta=0,7.5
XS Rating Curve= 0
Exp/Cntr=.3,.1

Type RM Length L Ch R = 1 ,500.00  ,50,50,50
BEGIN DESCRIPTION:
10
END DESCRIPTION:
#Sta/Elev= 15
   -10.5    5.86     -.5    5.86     -.2    6.26       0    6.26       3    6.16
       5    4.96       7    4.06     9.4    4.06     9.6    3.86    13.3    3.86
    15.9    6.06    16.8    6.06    19.8    6.06    20.4    5.36    30.4    5.36
#Mann= 3 , 0 , 0
   -10.5    .035       0       3    .035       0    15.9    .035       0
#XS Ineff= 2 , 0
       0       3    6.16    15.9       0    6.06
Permanent Ineff=
       F       F
Bank Sta=3,15.9
XS Rating Curve= 0
Exp/Cntr=.3,.1

Type RM Length L Ch R = 1 ,450.00  ,50,50,50
BEGIN DESCRIPTION:
9
END DESCRIPTION:
#Sta/Elev= 15
   -10.5    5.23     -.5    5.23     -.2    5.63       0    5.63       3    5.53
       5    4.33       7    3.43     9.4    3.43     9.6    3.23    13.3    3.23
    15.9    5.43    16.8    5.43    19.8    5.43    20.4    4.73    30.4    4.73
#Mann= 3 , 0 , 0
   -10.5    .035       0       3    .035       0    15.9    .035       0
#XS Ineff= 2 , 0
       0       3    5.53    15.9       0    5.43
Permanent Ineff=
       F       F
Bank Sta=3,15.9
XS Rating Curve= 0
Exp/Cntr=.3,.1

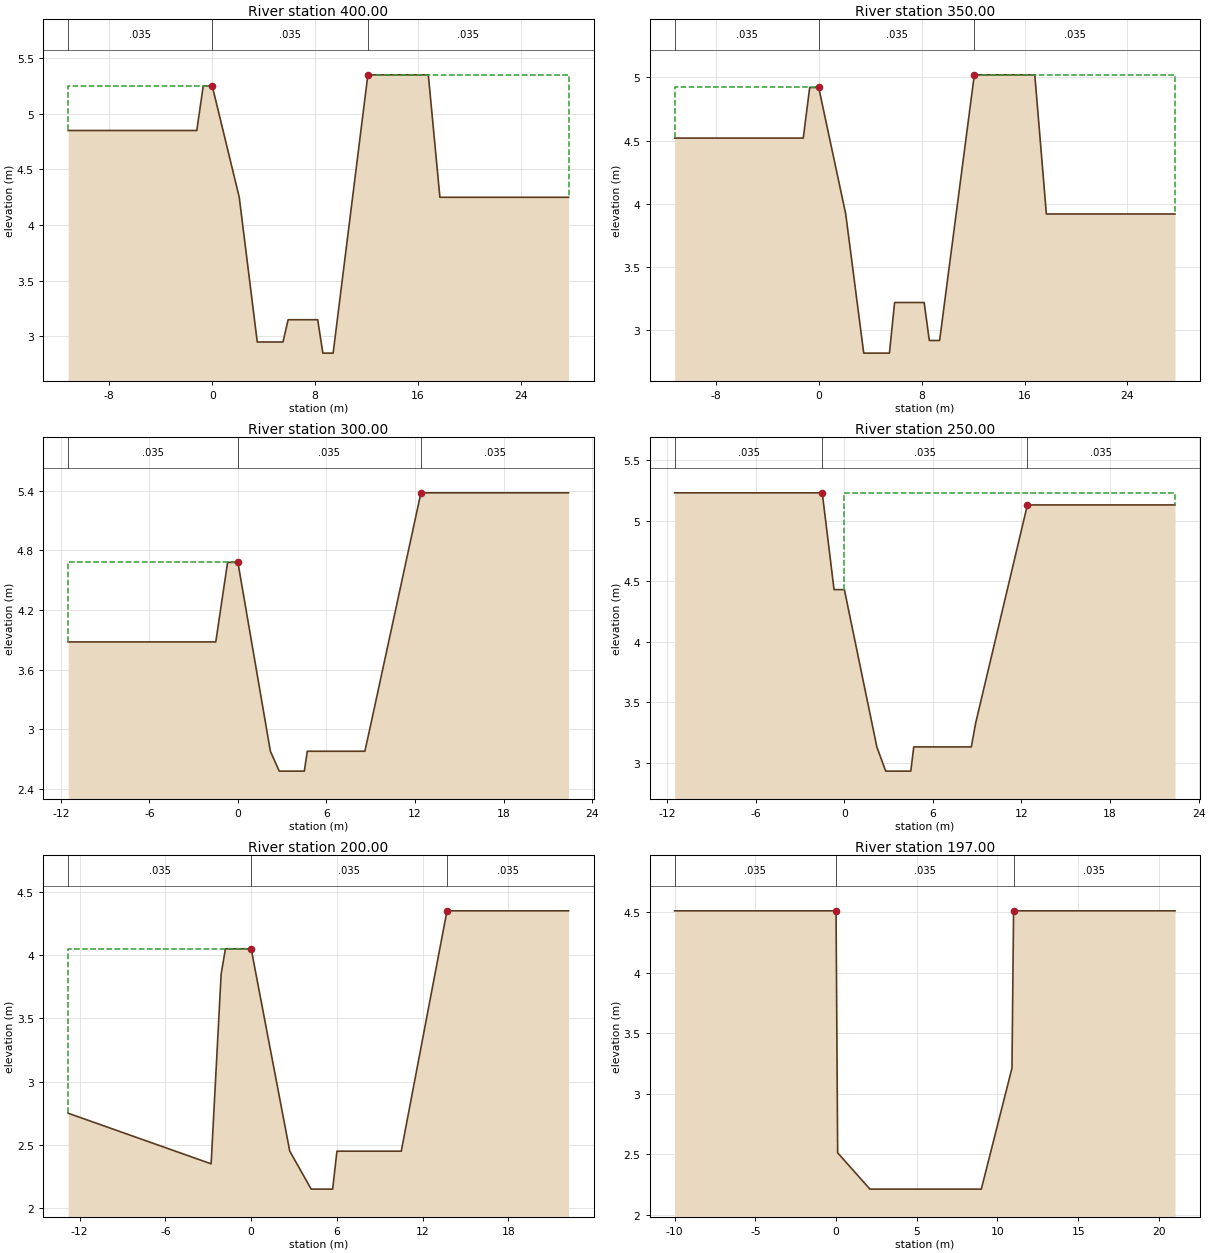
Type RM Length L Ch R = 1 ,400.00  ,50,50,50
BEGIN DESCRIPTION:
8
END DESCRIPTION:
#Sta/Elev= 17
   -11.2    4.85    -1.2    4.85     -.7    5.25       0    5.25     2.1    4.25
     3.5    2.95     5.5    2.95     5.9    3.15     8.2    3.15     8.6    2.85
     9.4    2.85    12.1    5.35      13    5.35      16    5.35    16.8    5.35
    17.7    4.25    27.7    4.25
#Mann= 3 , 0 , 0
   -11.2    .035       0       0    .035       0    12.1    .035       0
#XS Ineff= 2 , 0
               0    5.25    12.1            5.35
Permanent Ineff=
       F       F
Bank Sta=0,12.1
XS Rating Curve= 0
Exp/Cntr=.3,.1

Type RM Length L Ch R = 1 ,350.00  ,50,50,50
BEGIN DESCRIPTION:
7
END DESCRIPTION:
#Sta/Elev= 17
   -11.2    4.52    -1.2    4.52     -.7    4.92       0    4.92     2.1    3.92
     3.5    2.82     5.5    2.82     5.9    3.22     8.2    3.22     8.6    2.92
     9.4    2.92    12.1    5.02      13    5.02      16    5.02    16.8    5.02
    17.7    3.92    27.7    3.92
#Mann= 3 , 0 , 0
   -11.2    .035       0       0    .035       0    12.1    .035       0
#XS Ineff= 2 , 0
               0    4.92    12.1            5.02
Permanent Ineff=
       F       F
Bank Sta=0,12.1
XS Rating Curve= 0
Exp/Cntr=.3,.1

Type RM Length L Ch R = 1 ,300.00  ,50,50,50
BEGIN DESCRIPTION:
6
END DESCRIPTION:
#Sta/Elev= 12
   -11.5    3.88    -1.5    3.88     -.7    4.68       0    4.68     2.2    2.78
     2.8    2.58     4.5    2.58     4.7    2.78     8.6    2.78     8.9    2.98
    12.4    5.38    22.4    5.38
#Mann= 3 , 0 , 0
   -11.5    .035       0       0    .035       0    12.4    .035       0
#XS Ineff= 2 , 0
               0    4.68    12.4            5.38
Permanent Ineff=
       F       F
Bank Sta=0,12.4
XS Rating Curve= 0
Exp/Cntr=.3,.1

Type RM Length L Ch R = 1 ,250.00  ,50,50,50
BEGIN DESCRIPTION:
5
END DESCRIPTION:
#Sta/Elev= 12
   -11.5    5.23    -1.5    5.23     -.7    4.43       0    4.43     2.2    3.13
     2.8    2.93     4.5    2.93     4.7    3.13     8.6    3.13     8.9    3.33
    12.4    5.13    22.4    5.13
#Mann= 3 , 0 , 0
   -11.5    .035       0    -1.5    .035       0    12.4    .035       0
#XS Ineff= 2 , 0
       0    -1.5    5.23    12.4       0    5.13
Permanent Ineff=
       F       F
Bank Sta=-1.5,12.4
XS Rating Curve= 0
Exp/Cntr=.3,.1

Type RM Length L Ch R = 1 ,200.00  ,3,3,3
BEGIN DESCRIPTION:
4
END DESCRIPTION:
#Sta/Elev= 15
   -12.8    2.75    -7.8    2.55    -2.8    2.35    -2.1    3.85    -1.8    4.05
       0    4.05     2.7    2.45     4.2    2.15     5.7    2.15       6    2.45
    10.5    2.45    13.7    4.35   14.21    4.35    17.2    4.35    22.2    4.35
#Mann= 3 , 0 , 0
   -12.8    .035       0       0    .035       0    13.7    .035       0
#XS Ineff= 2 , 0
               0    4.05    13.7            4.35
Permanent Ineff=
       F       F
Bank Sta=0,13.7
XS Rating Curve= 0
Exp/Cntr=.3,.1

Type RM Length L Ch R = 1 ,197.00  ,3,3,3
BEGIN DESCRIPTION:
3.047
END DESCRIPTION:
#Sta/Elev= 8
     -10    4.51       0    4.51      .1    2.51     2.1    2.21       9    2.21
    10.9    3.21      11    4.51      21    4.51
#Mann= 3 , 0 , 0
     -10    .035       0       0    .035       0      11    .035       0
#XS Ineff= 2 , 0
               0    4.51      11            4.51
Permanent Ineff=
       F       F
Bank Sta=0,11
XS Rating Curve= 0
Exp/Cntr=.3,.1

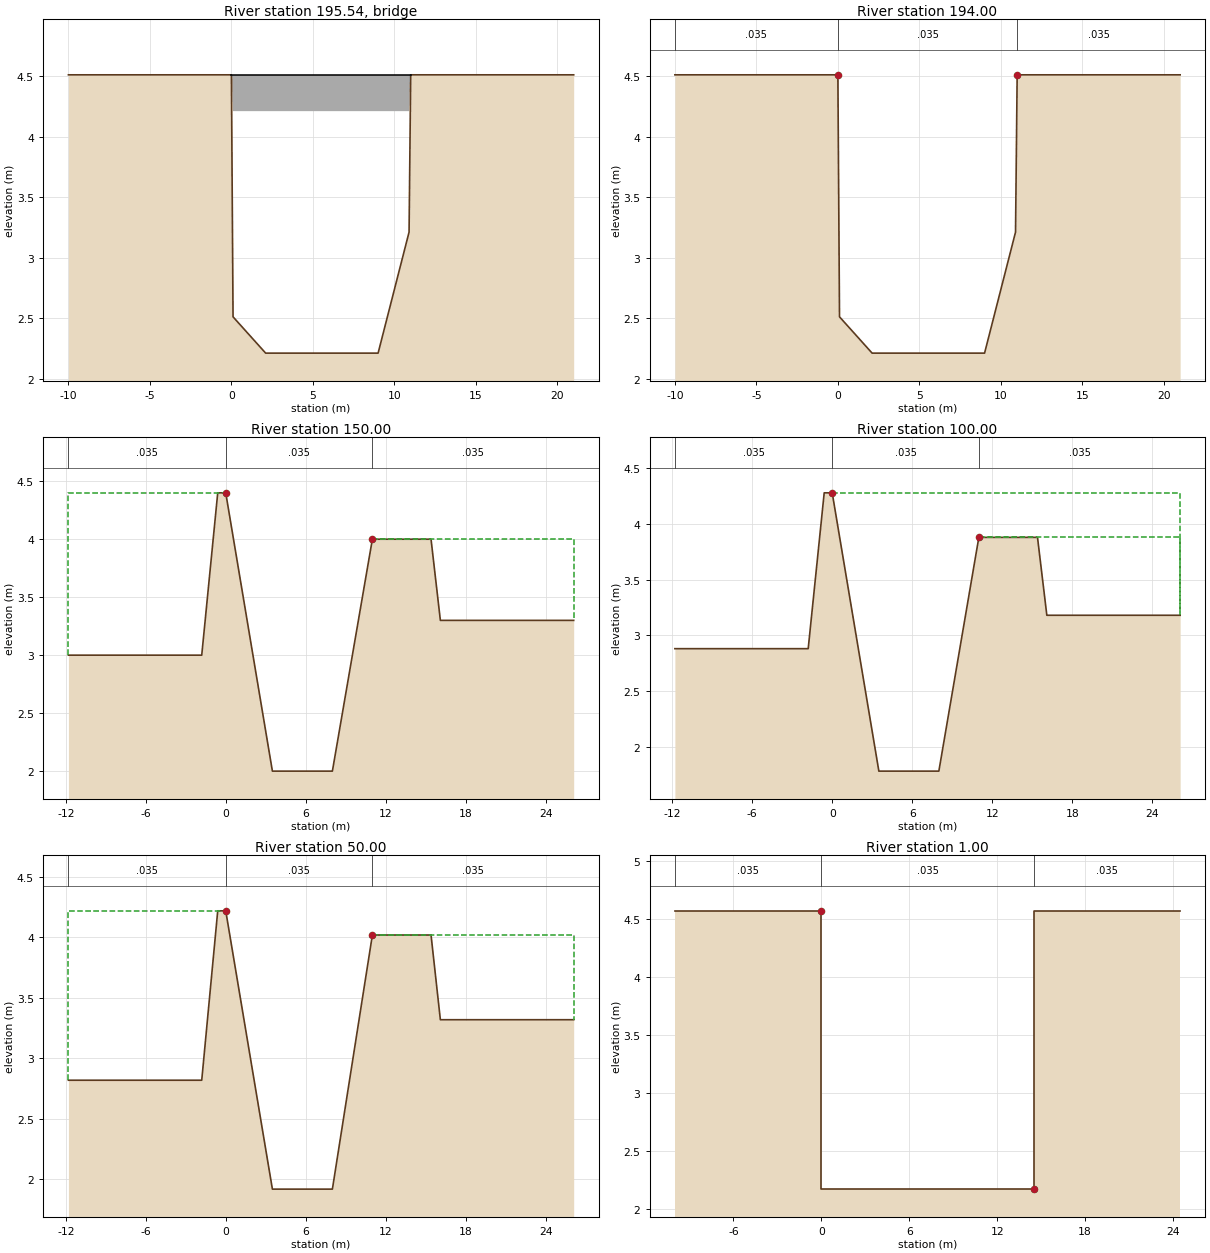
Type RM Length L Ch R = 3 ,195.54  ,,,
BEGIN DESCRIPTION:
3.0455
END DESCRIPTION:
Bridge Culvert--1,0,-1,-1, 0
Deck Dist Width WeirC Skew NumUp NumDn MinLoCord MaxHiCord MaxSubmerge Is_Ogee
.01,2.9,1.44,0, 2, 2, , , .95, 0, 0,0,,
       0      11
    4.51    4.51
    4.21    4.21
       0      11
    4.51    4.51
    4.21    4.21
BR Coef=-1 , 1 , 0 ,, 0 ,,,.8,-1,1.2,0,
WSPro=,,,, 1 ,,,, 0 ,,,, 0 ,,,,-1 ,-1 ,-1 , 0 , 0 , 0 , 0 , 0
BC Design=,, 0 ,, 0 ,,,,,,

Type RM Length L Ch R = 1 ,194.00  ,44,44,44
BEGIN DESCRIPTION:
3.044
END DESCRIPTION:
#Sta/Elev= 8
     -10    4.51       0    4.51      .1    2.51     2.1    2.21       9    2.21
    10.9    3.21      11    4.51      21    4.51
#Mann= 3 , 0 , 0
     -10    .035       0       0    .035       0      11    .035       0
#XS Ineff= 2 , 0
               0    4.51      11            4.51
Permanent Ineff=
       F       F
Bank Sta=0,11
XS Rating Curve= 0
Exp/Cntr=.3,.1

Type RM Length L Ch R = 1 ,150.00  ,50,50,50
BEGIN DESCRIPTION:
3
END DESCRIPTION:
#Sta/Elev= 12
   -11.8       3    -1.8       3     -.6     4.4       0     4.4     3.5       2
       8       2      11       4    12.2       4    15.2       4    15.4       4
    16.1     3.3    26.1     3.3
#Mann= 3 , 0 , 0
   -11.8    .035       0       0    .035       0      11    .035       0
#XS Ineff= 2 , 0
               0     4.4      11               4
Permanent Ineff=
       F       F
Bank Sta=0,11
XS Rating Curve= 0
Exp/Cntr=.3,.1

Type RM Length L Ch R = 1 ,100.00  ,50,50,50
BEGIN DESCRIPTION:
2
END DESCRIPTION:
#Sta/Elev= 12
   -11.8    2.88    -1.8    2.88     -.6    4.28       0    4.28     3.5    1.78
       8    1.78      11    3.88    12.2    3.88    15.2    3.88    15.4    3.88
    16.1    3.18    26.1    3.18
#Mann= 3 , 0 , 0
   -11.8    .035       0       0    .035       0      11    .035       0
#XS Ineff= 2 , 0
       0       0    4.28      11       0    3.88
Permanent Ineff=
       F       F
Bank Sta=0,11
XS Rating Curve= 0
Exp/Cntr=.3,.1

Type RM Length L Ch R = 1 ,50.00   ,49,49,49
BEGIN DESCRIPTION:
1
END DESCRIPTION:
#Sta/Elev= 12
   -11.8    2.82    -1.8    2.82     -.6    4.22       0    4.22     3.5    1.92
       8    1.92      11    4.02    12.3    4.02    15.2    4.02    15.4    4.02
    16.1    3.32    26.1    3.32
#Mann= 3 , 0 , 0
   -11.8    .035       0       0    .035       0      11    .035       0
#XS Ineff= 2 , 0
               0    4.22      11            4.02
Permanent Ineff=
       F       F
Bank Sta=0,11
XS Rating Curve= 0
Exp/Cntr=.3,.1

Type RM Length L Ch R = 1 ,1.00    ,1,1,1
BEGIN DESCRIPTION:
0.001
END DESCRIPTION:
#Sta/Elev= 6
     -10    4.57       0    4.57       0    2.17    14.5    2.17    14.5    4.57
    24.5    4.57
#Mann= 3 , 0 , 0
     -10    .035       0       0    .035       0    14.5    .035       0
#XS Ineff= 2 , 0
       0       0    4.57    14.5       0    2.17
Permanent Ineff=
       F       F
Bank Sta=0,14.5
XS Rating Curve= 0
Exp/Cntr=.3,.1

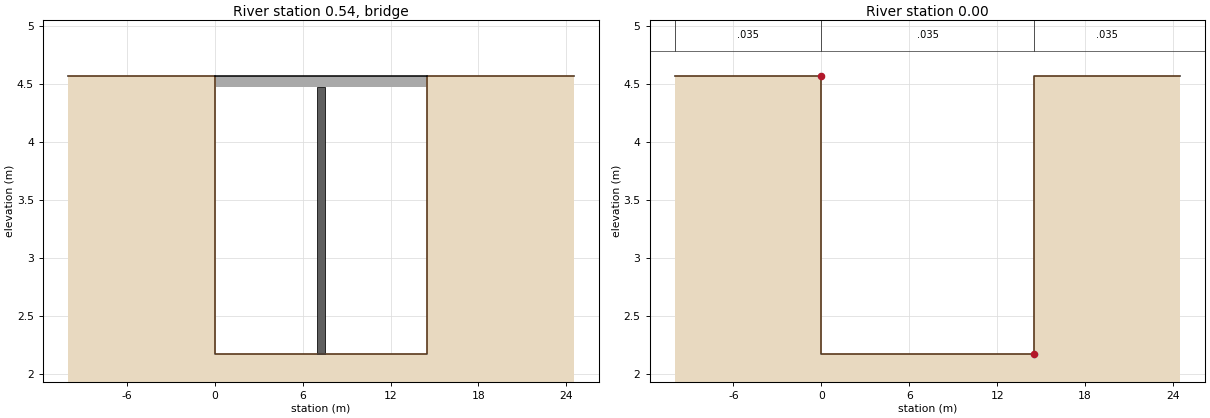
Type RM Length L Ch R = 3 ,0.54    ,,,
BEGIN DESCRIPTION:
0.0005
END DESCRIPTION:
Bridge Culvert--1,0,-1,-1, 0
Deck Dist Width WeirC Skew NumUp NumDn MinLoCord MaxHiCord MaxSubmerge Is_Ogee
.01,.9,1.44,0, 2, 2, , , .95, 0, 0,0,,
       0    14.5
    4.57    4.57
    4.47    4.47
       0    14.5
    4.57    4.57
    4.47    4.47
Pier Skew, UpSta & Num, DnSta & Num=  ,7.25, 2 ,7.25, 2 , 0 , 0 , 0 ,,
      .5      .5
    2.17    4.57
      .5      .5
    2.17    4.57
BR Coef=-1 , 1 , 1 ,.9, 0 ,,,.8,-1,1.2,0,
WSPro=,,,, 1 ,,,, 0 ,,,, 0 ,,,,-1 ,-1 ,-1 , 0 , 0 , 0 , 0 , 0
BC Design=,, 0 ,, 0 ,,,,,,

Type RM Length L Ch R = 1 ,0.00    ,0,0,0
BEGIN DESCRIPTION:
0
END DESCRIPTION:
#Sta/Elev= 6
     -10    4.57       0    4.57       0    2.17    14.5    2.17    14.5    4.57
    24.5    4.57
#Mann= 3 , 0 , 0
     -10    .035       0       0    .035       0    14.5    .035       0
#XS Ineff= 2 , 0
       0       0    4.57    14.5       0    2.17
Permanent Ineff=
       F       F
Bank Sta=0,14.5
XS Rating Curve= 0
Exp/Cntr=.3,.1

Chan Stop Cuts=-1