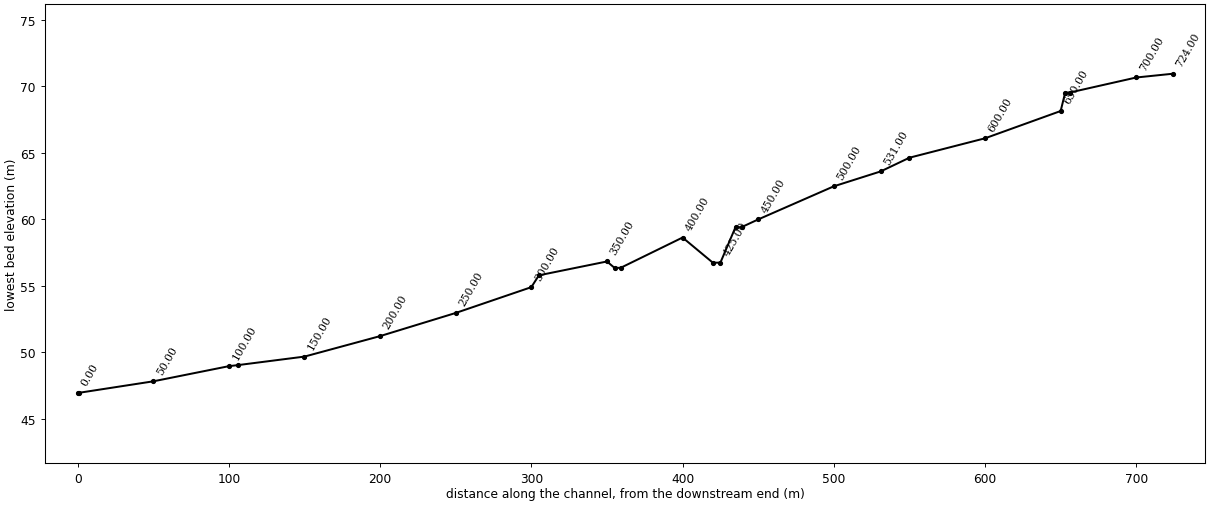
--- spc.prj (project) ---

Proj Title=sangpung-ch
Current Plan=p01
Default Exp/Contr=.3,.1
SI Units
Geom File=g01
Flow File=f01
Plan File=p01
Y Axis Title=Elevation
X Axis Title(PF)=Main Channel Distance
X Axis Title(XS)=Station
BEGIN DESCRIPTION:
           BACK WATER COMPUTATION
      APPLICATION OF HEC-2 BY Samju Construction Engineering
      »óÆòÃµ(¿ËÃµÀ¾): 30,50,80,100,150³âºóµµ °³¼öÀü
END DESCRIPTION:
DSS Export Rating Curves= 0
DSS Export Rating Curve Sorted= 0
DSS Export Volume Flow Curves= 0
DXF OffsetX= 0
DXF OffsetY= 0
DXF ScaleX= 1
DXF ScaleY= 10

--- spc.p01 (plan) ---

Plan Title=Imported Plan 01
Version=Version 3.0.1  Mar 2001
Short Identifier=Imported Pla
Geom File=g01
Flow File=f01
Subcritical Flow
K Sum by GR= 0
Std Step Tol= 0.003
Critical Tol= 0.003
Num of Std Step Trials= 20
Max Error Tol= 0.1
Flow Tol Ratio= 0.001
Split Flow NTrial= 30
Split Flow Tol= 0.02
Split Flow Ratio= 0.02
Log Output Level= 0
Friction Slope Method= 1
Unsteady Friction Slope Method= 2
Parabolic Critical Depth
Global Vel Dist= 0 , 0 , 0
Global Log Level= 0
CheckData=True
Encroach Param=-1 ,0,0, 0
Computation Interval=1HOUR
Output Interval=1HOUR
Run HTab= 0
Run UNet= 0
Run PostProcess= 0
UNET Theta= 1
UNET ZTol= 0.02
UNET ZSATol= 0.1
UNET MxIter= 20
UNET MaxInSteps= 20
UNET DtIC= 0
UNET DtMin= 0
UNET MaxCRTS= 20
UNET WFStab= 2
UNET SFStab= 1
UNET WFX= 1
UNET SFX= 1
UNET Convert EG Bridges=-1
UNET Use Existing IB Tables=-1
Instantaneous Interval=1HOUR
Write IC File= 0
Write Velocity= 0
Write Detailed= 0

--- spc.f01 (steady flow) ---

Flow Title=Imported Flow 01
Version=Version 3.0.1  Mar 2001
Number of Profiles= 5
Profile Names=10yr,20yr,30yr,50yr,80yr
River Rch & RM=RIVER-1,Reach-1         ,14.024
   26.92   29.66   31.26   33.28   35.14
River Rch & RM=sangpyung,sangpyung       ,724.00
   26.92   29.66   31.26   33.28   35.14
Boundary for River Rch & Prof#=sangpyung,sangpyung       , 1
Up Type= 0
Dn Type= 3
Dn Slope=.0342
Boundary for River Rch & Prof#=sangpyung,sangpyung       , 2
Up Type= 0
Dn Type= 3
Dn Slope=.0342
Boundary for River Rch & Prof#=sangpyung,sangpyung       , 3
Up Type= 0
Dn Type= 3
Dn Slope=.0342
Boundary for River Rch & Prof#=sangpyung,sangpyung       , 4
Up Type= 0
Dn Type= 3
Dn Slope=.0342
Boundary for River Rch & Prof#=sangpyung,sangpyung       , 5
Up Type= 0
Dn Type= 3
Dn Slope=.0342
DSS Import GetInterval= 0
DSS Import GetPeak= 0
DSS Import FillOption= 0

--- spc.g01 (geometry) ---

Geom Title=Imported Geom 01
Version=Version 3.0.1  Mar 2001

River Reach=sangpyung       ,sangpyung
Reach XY= 2
              .5             .95              .5             .05

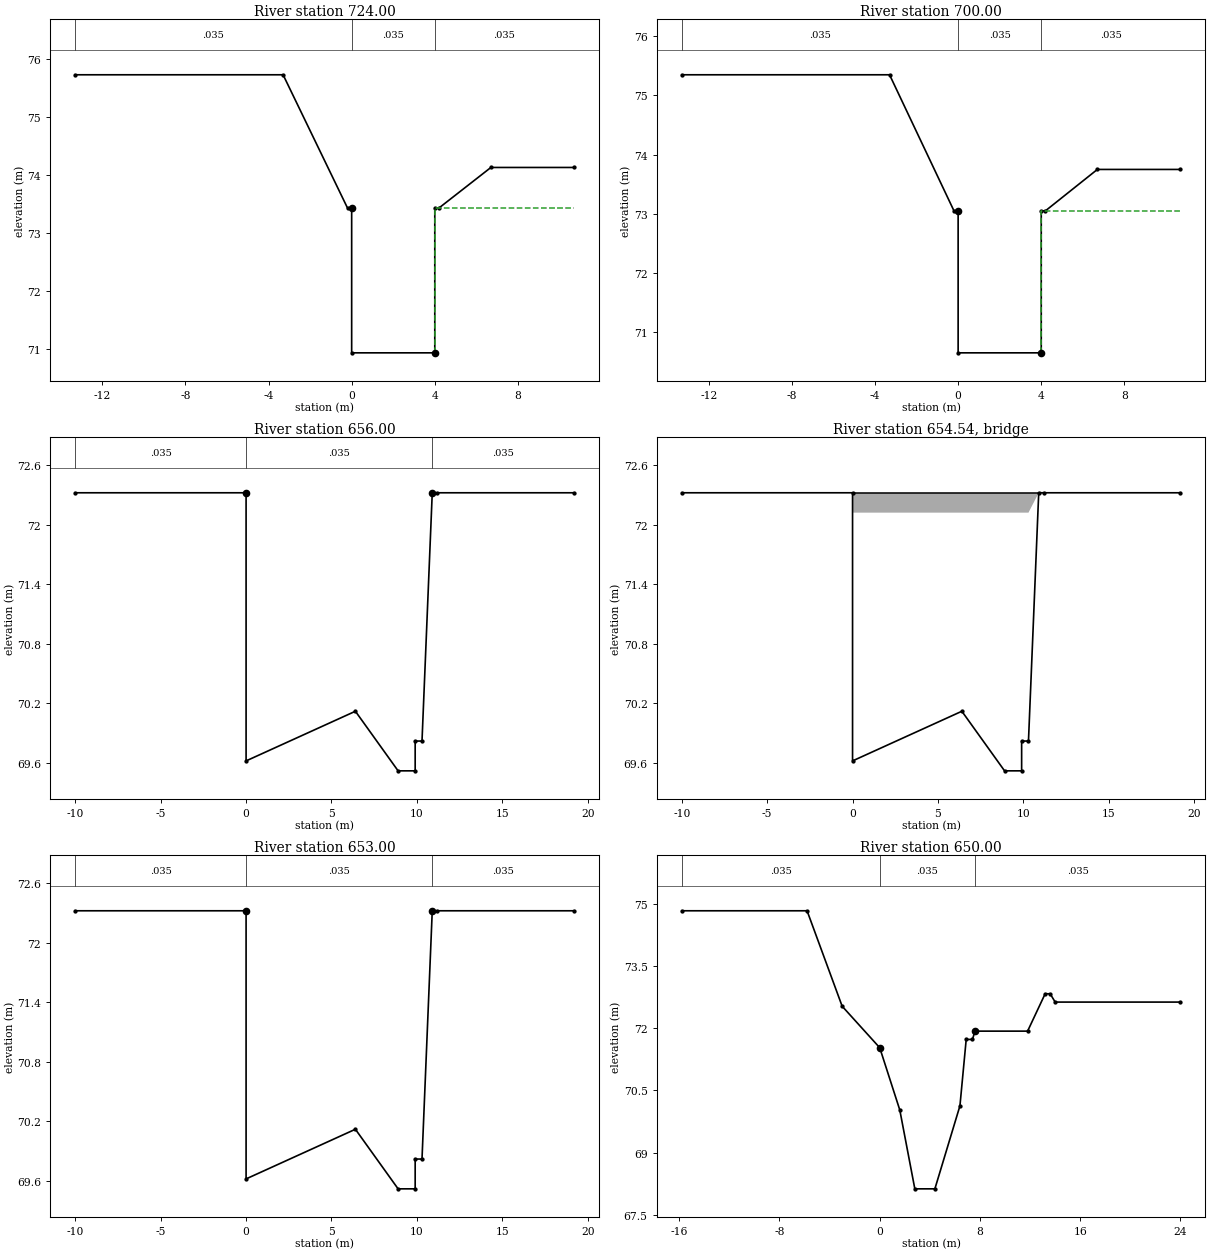
Type RM Length L Ch R = 1 ,724.00  ,24,24,24
BEGIN DESCRIPTION:
14.024
END DESCRIPTION:
#Sta/Elev= 10
   -13.3   75.73    -3.3   75.73     -.2   73.43       0   73.43       0   70.93
       4   70.93       4   73.43     4.2   73.43     6.7   74.13    10.7   74.13
#Mann= 3 , 0 , 0
   -13.3    .035       0       0    .035       0       4    .035       0
#XS Ineff= 2 , 0
               0   73.43       4           73.43
Permanent Ineff=
       F       F
Bank Sta=0,4
XS Rating Curve= 0
Exp/Cntr=.3,.1

Type RM Length L Ch R = 1 ,700.00  ,44,44,44
BEGIN DESCRIPTION:
14
END DESCRIPTION:
#Sta/Elev= 10
   -13.3   75.35    -3.3   75.35     -.2   73.05       0   73.05       0   70.65
       4   70.65       4   73.05     4.2   73.05     6.7   73.75    10.7   73.75
#Mann= 3 , 0 , 0
   -13.3    .035       0       0    .035       0       4    .035       0
#XS Ineff= 2 , 0
               0   73.05       4           73.05
Permanent Ineff=
       F       F
Bank Sta=0,4
XS Rating Curve= 0
Exp/Cntr=.3,.1

Type RM Length L Ch R = 1 ,656.00  ,3,3,3
BEGIN DESCRIPTION:
13.006
END DESCRIPTION:
#Sta/Elev= 11
     -10   72.32       0   72.32       0   69.62     6.4   70.12     8.9   69.52
     9.9   69.52     9.9   69.82    10.3   69.82    10.9   72.32    11.2   72.32
    19.2   72.32
#Mann= 3 , 0 , 0
     -10    .035       0       0    .035       0    10.9    .035       0
#XS Ineff= 2 , 0
       0       0   72.32    10.9       0   72.32
Permanent Ineff=
       F       F
Bank Sta=0,10.9
XS Rating Curve= 0
Exp/Cntr=.3,.1

Type RM Length L Ch R = 3 ,654.54  ,,,
BEGIN DESCRIPTION:
13.0045
END DESCRIPTION:
Bridge Culvert--1,0,-1,-1, 0
Deck Dist Width WeirC Skew NumUp NumDn MinLoCord MaxHiCord MaxSubmerge Is_Ogee
.01,2.9,1.44,0, 2, 2, , , .95, 0, 0,0,,
       0    10.9
   72.32   72.32
   72.12   72.12
       0    10.9
   72.32   72.32
   72.12   72.12
BR Coef=-1 , 1 , 0 ,, 0 ,,,.8,-1,1.2,0,
WSPro=,,,, 1 ,,,, 0 ,,,, 0 ,,,,-1 ,-1 ,-1 , 0 , 0 , 0 , 0 , 0
BC Design=,, 0 ,, 0 ,,,,,,

Type RM Length L Ch R = 1 ,653.00  ,3,3,3
BEGIN DESCRIPTION:
13.003
END DESCRIPTION:
#Sta/Elev= 11
     -10   72.32       0   72.32       0   69.62     6.4   70.12     8.9   69.52
     9.9   69.52     9.9   69.82    10.3   69.82    10.9   72.32    11.2   72.32
    19.2   72.32
#Mann= 3 , 0 , 0
     -10    .035       0       0    .035       0    10.9    .035       0
#XS Ineff= 2 , 0
       0       0   72.32    10.9       0   72.32
Permanent Ineff=
       F       F
Bank Sta=0,10.9
XS Rating Curve= 0
Exp/Cntr=.3,.1

Type RM Length L Ch R = 1 ,650.00  ,50,50,50
BEGIN DESCRIPTION:
13
END DESCRIPTION:
#Sta/Elev= 16
   -15.8   74.83    -5.8   74.83      -3   72.53       0   71.53     1.6   70.03
     2.8   68.13     4.4   68.13     6.4   70.13     6.9   71.73     7.4   71.73
     7.6   71.93    11.8   71.93    13.2   72.83    13.6   72.83      14   72.63
      24   72.63
#Mann= 3 , 0 , 0
   -15.8    .035       0       0    .035       0     7.6    .035       0
#XS Ineff= 2 , 0
               0   71.53     7.6           71.93
Permanent Ineff=
       F       F
Bank Sta=0,7.6
XS Rating Curve= 0
Exp/Cntr=.3,.1

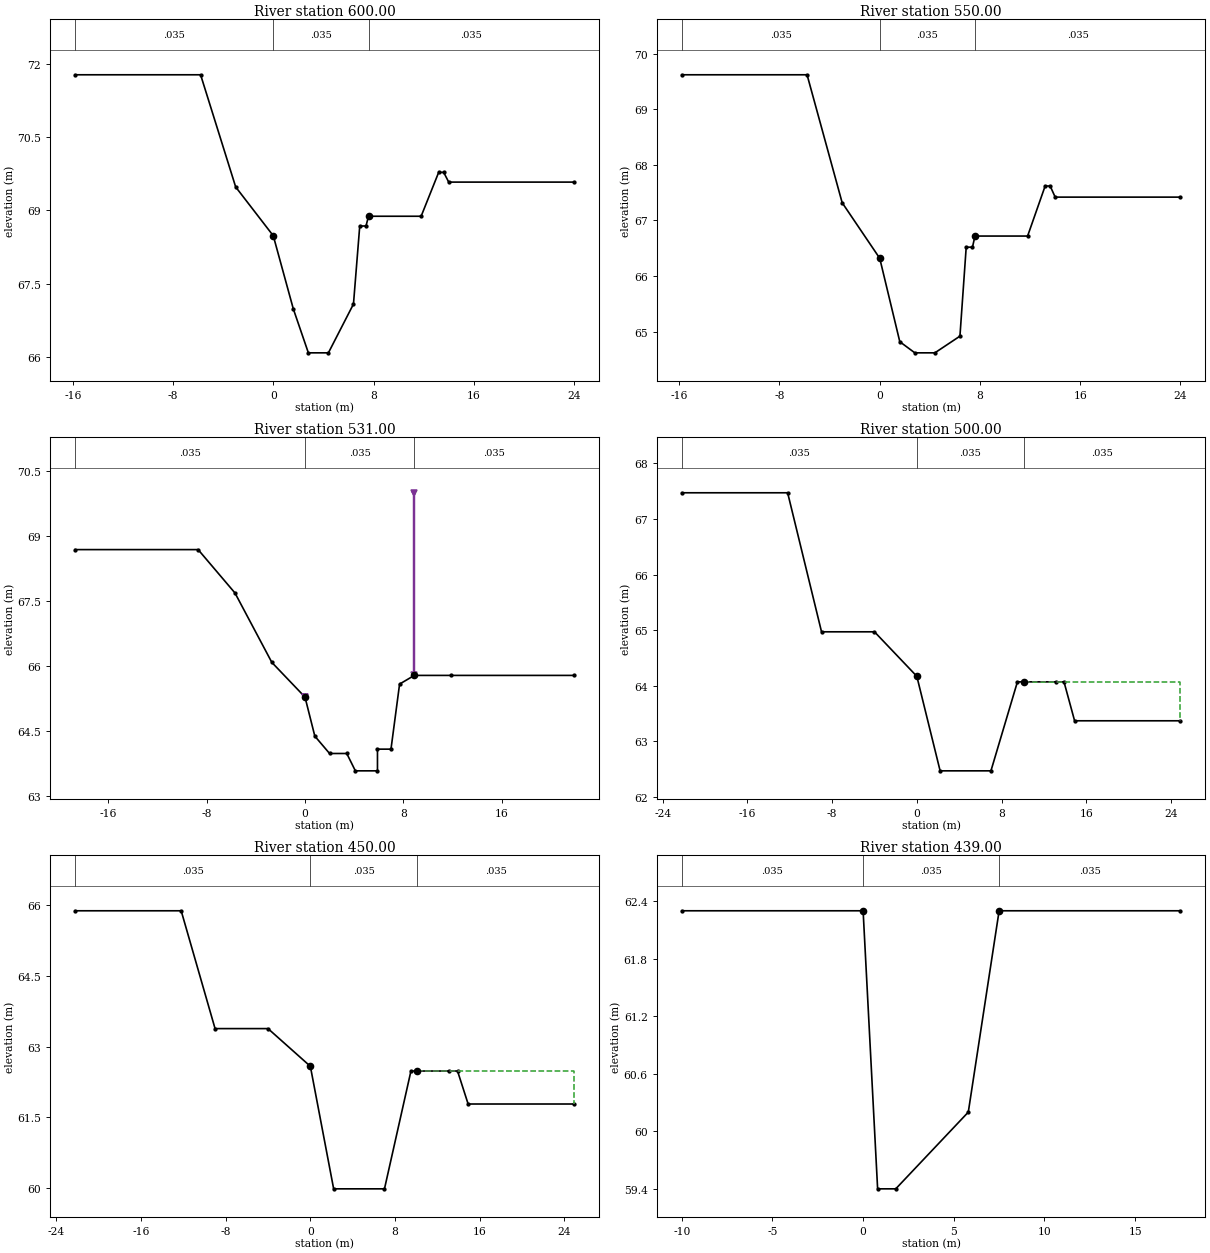
Type RM Length L Ch R = 1 ,600.00  ,50,50,50
BEGIN DESCRIPTION:
12
END DESCRIPTION:
#Sta/Elev= 16
   -15.8   71.78    -5.8   71.78      -3   69.48       0   68.48     1.6   66.98
     2.8   66.08     4.4   66.08     6.4   67.08     6.9   68.68     7.4   68.68
     7.6   68.88    11.8   68.88    13.2   69.78    13.6   69.78      14   69.58
      24   69.58
#Mann= 3 , 0 , 0
   -15.8    .035       0       0    .035       0     7.6    .035       0
#XS Ineff= 2 , 0
               0   68.48     7.6           68.88
Permanent Ineff=
       F       F
Bank Sta=0,7.6
XS Rating Curve= 0
Exp/Cntr=.3,.1

Type RM Length L Ch R = 1 ,550.00  ,19,19,19
BEGIN DESCRIPTION:
11
END DESCRIPTION:
#Sta/Elev= 16
   -15.8   69.62    -5.8   69.62      -3   67.32       0   66.32     1.6   64.82
     2.8   64.62     4.4   64.62     6.4   64.92     6.9   66.52     7.4   66.52
     7.6   66.72    11.8   66.72    13.2   67.62    13.6   67.62      14   67.42
      24   67.42
#Mann= 3 , 0 , 0
   -15.8    .035       0       0    .035       0     7.6    .035       0
#XS Ineff= 2 , 0
               0   66.32     7.6           66.72
Permanent Ineff=
       F       F
Bank Sta=0,7.6
XS Rating Curve= 0
Exp/Cntr=.3,.1

Type RM Length L Ch R = 1 ,531.00  ,31,31,31
BEGIN DESCRIPTION:
10.031
END DESCRIPTION:
#Sta/Elev= 16
   -18.7   68.69    -8.7   68.69    -5.7   67.69    -2.7   66.09       0   65.29
      .8   64.39       2   63.99     3.4   63.99     4.1   63.59     5.9   63.59
     5.9   64.09       7   64.09     7.7   65.59     8.9   65.79    11.9   65.79
    21.9   65.79
#Mann= 3 , 0 , 0
   -18.7    .035       0       0    .035       0     8.9    .035       0
Levee=-1,0,65.29,-1,8.9,70,,
#XS Ineff= 2 , 0
               0   65.29     8.9           65.79
Permanent Ineff=
       F       F
Bank Sta=0,8.9
XS Rating Curve= 0
Exp/Cntr=.3,.1

Type RM Length L Ch R = 1 ,500.00  ,50,50,50
BEGIN DESCRIPTION:
10
END DESCRIPTION:
#Sta/Elev= 13
   -22.2   67.47   -12.2   67.47      -9   64.97      -4   64.97       0   64.17
     2.2   62.47       7   62.47     9.5   64.07    10.1   64.07    13.1   64.07
    13.9   64.07    14.9   63.37    24.9   63.37
#Mann= 3 , 0 , 0
   -22.2    .035       0       0    .035       0    10.1    .035       0
#XS Ineff= 2 , 0
               0   64.17    10.1           64.07
Permanent Ineff=
       F       F
Bank Sta=0,10.1
XS Rating Curve= 0
Exp/Cntr=.3,.1

Type RM Length L Ch R = 1 ,450.00  ,11,11,11
BEGIN DESCRIPTION:
9
END DESCRIPTION:
#Sta/Elev= 13
   -22.2   65.88   -12.2   65.88      -9   63.38      -4   63.38       0   62.58
     2.2   59.98       7   59.98     9.5   62.48    10.1   62.48    13.1   62.48
    13.9   62.48    14.9   61.78    24.9   61.78
#Mann= 3 , 0 , 0
   -22.2    .035       0       0    .035       0    10.1    .035       0
#XS Ineff= 2 , 0
               0   62.58    10.1           62.48
Permanent Ineff=
       F       F
Bank Sta=0,10.1
XS Rating Curve= 0
Exp/Cntr=.3,.1

Type RM Length L Ch R = 1 ,439.00  ,4,4,4
BEGIN DESCRIPTION:
8.039
END DESCRIPTION:
#Sta/Elev= 7
     -10    62.3       0    62.3      .8    59.4     1.8    59.4     5.8    60.2
     7.5    62.3    17.5    62.3
#Mann= 3 , 0 , 0
     -10    .035       0       0    .035       0     7.5    .035       0
#XS Ineff= 2 , 0
       0       0    62.3     7.5       0    62.3
Permanent Ineff=
       F       F
Bank Sta=0,7.5
XS Rating Curve= 0
Exp/Cntr=.3,.1

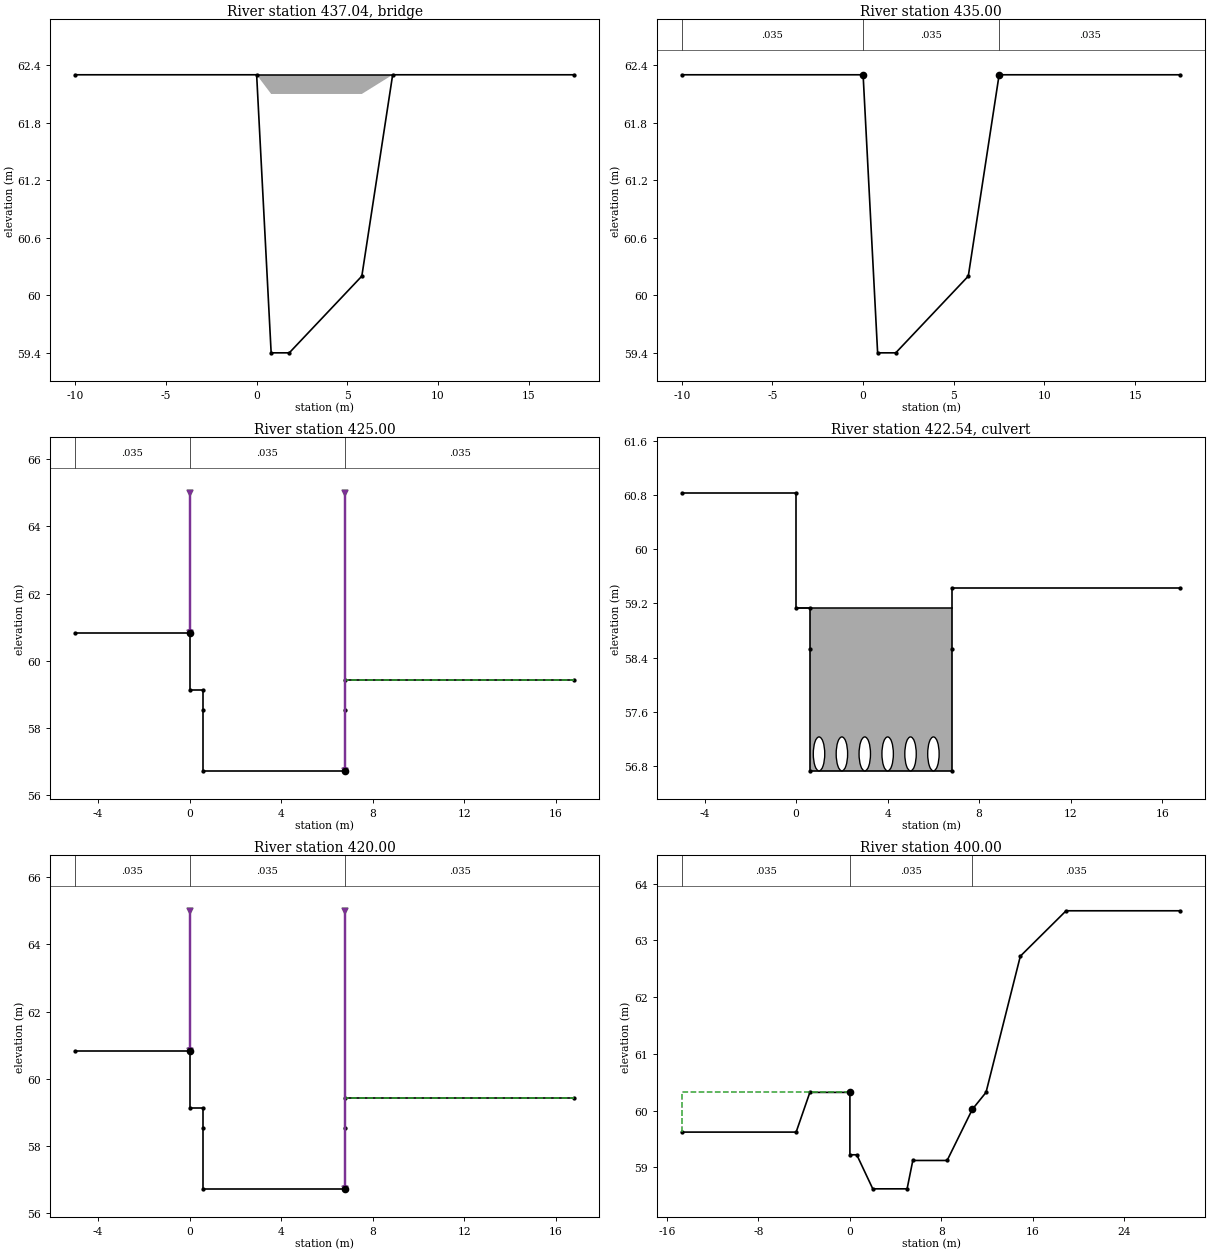
Type RM Length L Ch R = 3 ,437.04  ,,,
BEGIN DESCRIPTION:
8.037
END DESCRIPTION:
Bridge Culvert--1,0,-1,-1, 0
Deck Dist Width WeirC Skew NumUp NumDn MinLoCord MaxHiCord MaxSubmerge Is_Ogee
.01,3.9,1.44,0, 2, 2, , , .95, 0, 0,0,,
       0     7.5
    62.3    62.3
    62.1    62.1
       0     7.5
    62.3    62.3
    62.1    62.1
BR Coef=-1 , 1 , 0 ,, 0 ,,,.8,-1,1.2,0,
WSPro=,,,, 1 ,,,, 0 ,,,, 0 ,,,,-1 ,-1 ,-1 , 0 , 0 , 0 , 0 , 0
BC Design=,, 0 ,, 0 ,,,,,,

Type RM Length L Ch R = 1 ,435.00  ,10,10,10
BEGIN DESCRIPTION:
8.035
END DESCRIPTION:
#Sta/Elev= 7
     -10    62.3       0    62.3      .8    59.4     1.8    59.4     5.8    60.2
     7.5    62.3    17.5    62.3
#Mann= 3 , 0 , 0
     -10    .035       0       0    .035       0     7.5    .035       0
#XS Ineff= 2 , 0
       0       0    62.3     7.5       0    62.3
Permanent Ineff=
       F       F
Bank Sta=0,7.5
XS Rating Curve= 0
Exp/Cntr=.3,.1

Type RM Length L Ch R = 1 ,425.00  ,5,5,5
BEGIN DESCRIPTION:
8.025
END DESCRIPTION:
#Sta/Elev= 10
      -5   60.83       0   60.83       0   59.13      .6   59.13      .6   58.53
      .6   56.73     6.8   56.73     6.8   58.53     6.8   59.43    16.8   59.43
#Mann= 3 , 0 , 0
      -5    .035       0       0    .035       0     6.8    .035       0
Levee=-1,0,65,-1,6.8,65,,
#XS Ineff= 2 , 0
               0   60.83     6.8           59.43
Permanent Ineff=
       F       F
Bank Sta=0,6.8
XS Rating Curve= 0
Exp/Cntr=.3,.1

Type RM Length L Ch R = 2 ,422.54  ,,,
BEGIN DESCRIPTION:
8.0235
END DESCRIPTION:
Bridge Culvert--1,0,-1,-1, 0
Deck Dist Width WeirC Skew NumUp NumDn MinLoCord MaxHiCord MaxSubmerge Is_Ogee
.01,4.9,1.44,0, 2, 2, , , .95, 0, 0,0,,
       0     6.8
   59.13   59.13
   56.73   56.73
       0     6.8
   59.13   59.13
   56.73   56.73
BR Coef=-1 , 1 , 1 ,.9, 0 ,,,.8,-1,1.2,0,
WSPro=,,,, 1 ,,,, 0 ,,,, 0 ,,,,-1 ,-1 ,-1 , 0 , 0 , 0 , 0 , 0
Multiple Barrel Culv=1,.5,,5,.015,.2,1,1,1,56.73,56.73, 6,Culvert #1  , 0 ,0
       1       1       2       2       3       3       4       4       5       5
       6       6
Culvert Bottom n=.015
BC Design=,, 0 ,, 0 ,,,,,,

Type RM Length L Ch R = 1 ,420.00  ,20,20,20
BEGIN DESCRIPTION:
8.020
END DESCRIPTION:
#Sta/Elev= 10
      -5   60.83       0   60.83       0   59.13      .6   59.13      .6   58.53
      .6   56.73     6.8   56.73     6.8   58.53     6.8   59.43    16.8   59.43
#Mann= 3 , 0 , 0
      -5    .035       0       0    .035       0     6.8    .035       0
Levee=-1,0,65,-1,6.8,65,,
#XS Ineff= 2 , 0
               0   60.83     6.8           59.43
Permanent Ineff=
       F       F
Bank Sta=0,6.8
XS Rating Curve= 0
Exp/Cntr=.3,.1

Type RM Length L Ch R = 1 ,400.00  ,41,41,41
BEGIN DESCRIPTION:
8
END DESCRIPTION:
#Sta/Elev= 15
   -14.7   59.62    -4.7   59.62    -3.5   60.32       0   60.32       0   59.22
      .6   59.22       2   58.62       5   58.62     5.5   59.12     8.5   59.12
    10.7   60.02    11.9   60.32    14.9   62.72    18.9   63.52    28.9   63.52
#Mann= 3 , 0 , 0
   -14.7    .035       0       0    .035       0    10.7    .035       0
#XS Ineff= 2 , 0
               0   60.32    10.7           60.02
Permanent Ineff=
       F       F
Bank Sta=0,10.7
XS Rating Curve= 0
Exp/Cntr=.3,.1

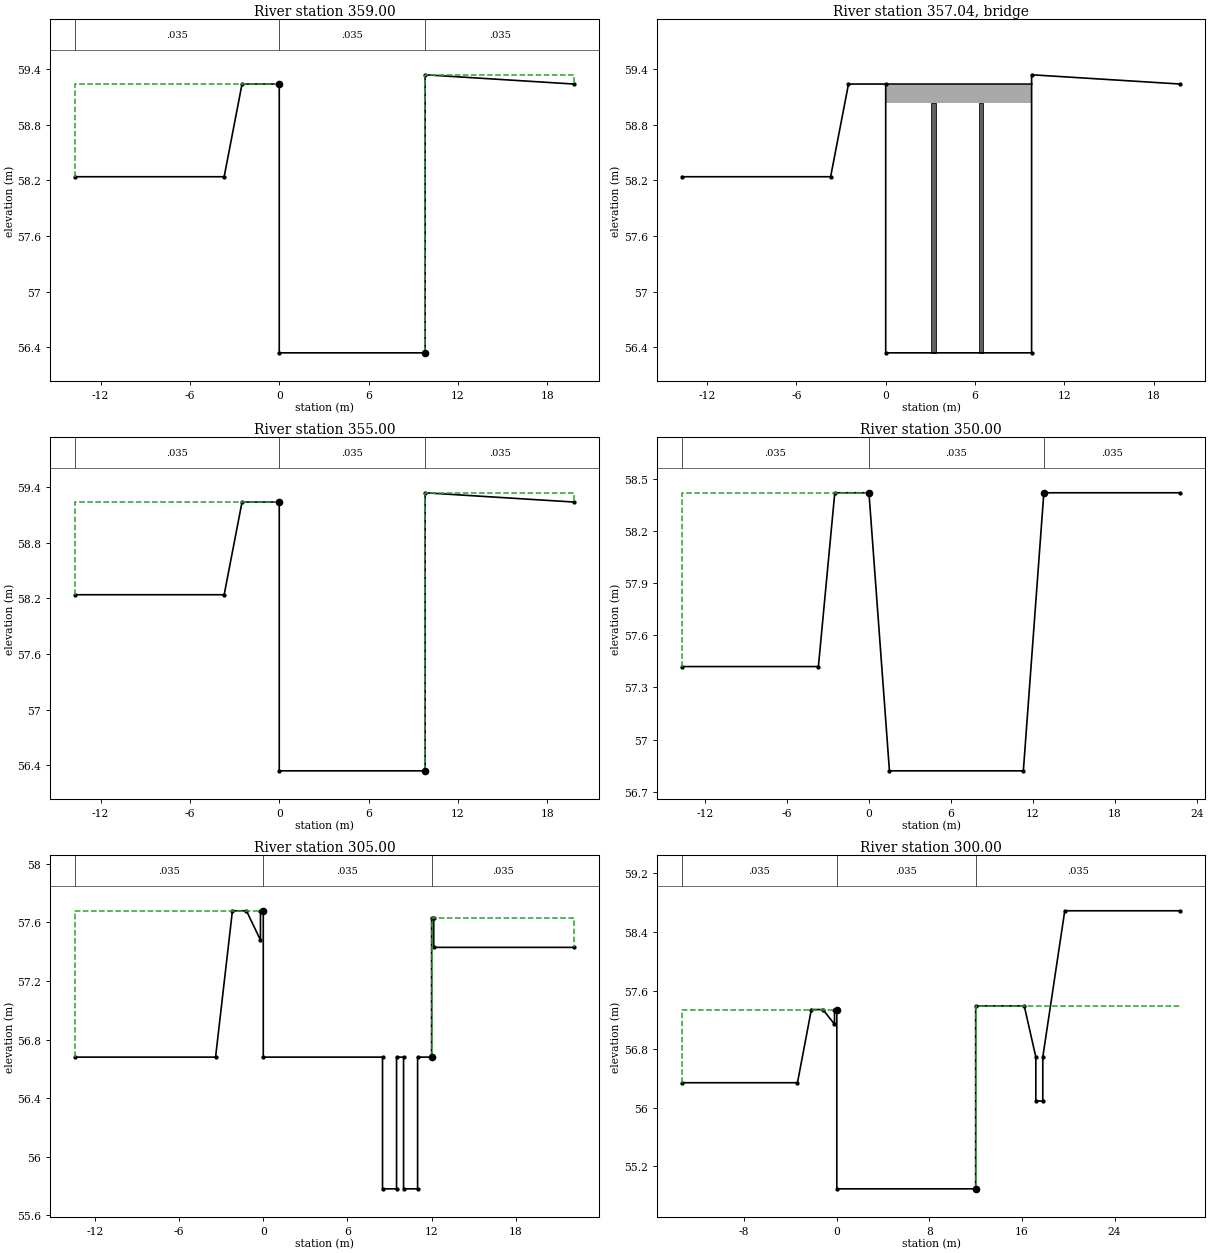
Type RM Length L Ch R = 1 ,359.00  ,4,4,4
BEGIN DESCRIPTION:
7.009
END DESCRIPTION:
#Sta/Elev= 8
   -13.7   58.24    -3.7   58.24    -2.5   59.24       0   59.24       0   56.34
     9.8   56.34     9.8   59.34    19.8   59.24
#Mann= 3 , 0 , 0
   -13.7    .035       0       0    .035       0     9.8    .035       0
#XS Ineff= 2 , 0
               0   59.24     9.8           59.34
Permanent Ineff=
       F       F
Bank Sta=0,9.8
XS Rating Curve= 0
Exp/Cntr=.3,.1

Type RM Length L Ch R = 3 ,357.04  ,,,
BEGIN DESCRIPTION:
7.007
END DESCRIPTION:
Bridge Culvert--1,0,-1,-1, 0
Deck Dist Width WeirC Skew NumUp NumDn MinLoCord MaxHiCord MaxSubmerge Is_Ogee
.01,3.9,1.44,0, 2, 2, , , .95, 0, 0,0,,
       0     9.8
   59.24   59.24
   59.04   59.04
       0     9.8
   59.24   59.24
   59.04   59.04
Pier Skew, UpSta & Num, DnSta & Num=  ,3.2, 2 ,3.2, 2 , 0 , 0 , 0 ,,
      .3      .3
   56.34   59.24
      .3      .3
   56.34   59.24
Pier Skew, UpSta & Num, DnSta & Num=  ,6.4, 2 ,6.4, 2 , 0 , 0 , 0 ,,
      .3      .3
   56.34   59.24
      .3      .3
   56.34   59.24
BR Coef=-1 , 1 , 1 ,.9, 0 ,,,.8,-1,1.2,0,
WSPro=,,,, 1 ,,,, 0 ,,,, 0 ,,,,-1 ,-1 ,-1 , 0 , 0 , 0 , 0 , 0
BC Design=,, 0 ,, 0 ,,,,,,

Type RM Length L Ch R = 1 ,355.00  ,5,5,5
BEGIN DESCRIPTION:
7.005
END DESCRIPTION:
#Sta/Elev= 8
   -13.7   58.24    -3.7   58.24    -2.5   59.24       0   59.24       0   56.34
     9.8   56.34     9.8   59.34    19.8   59.24
#Mann= 3 , 0 , 0
   -13.7    .035       0       0    .035       0     9.8    .035       0
#XS Ineff= 2 , 0
               0   59.24     9.8           59.34
Permanent Ineff=
       F       F
Bank Sta=0,9.8
XS Rating Curve= 0
Exp/Cntr=.3,.1

Type RM Length L Ch R = 1 ,350.00  ,45,45,45
BEGIN DESCRIPTION:
7
END DESCRIPTION:
#Sta/Elev= 8
   -13.7   57.42    -3.7   57.42    -2.5   58.42       0   58.42     1.5   56.82
    11.3   56.82    12.8   58.42    22.8   58.42
#Mann= 3 , 0 , 0
   -13.7    .035       0       0    .035       0    12.8    .035       0
#XS Ineff= 2 , 0
               0   58.42    12.8           58.42
Permanent Ineff=
       F       F
Bank Sta=0,12.8
XS Rating Curve= 0
Exp/Cntr=.3,.1

Type RM Length L Ch R = 1 ,305.00  ,5,5,5
BEGIN DESCRIPTION:
6.005
END DESCRIPTION:
#Sta/Elev= 21
   -13.4   56.68    -3.4   56.68    -2.2   57.68    -1.2   57.68     -.2   57.48
     -.2   57.68       0   57.68       0   56.68     8.5   56.68     8.5   55.78
     9.5   55.78     9.5   56.68      10   56.68      10   55.78      11   55.78
      11   56.68      12   56.68      12   57.63   12.15   57.63   12.15   57.43
   22.15   57.43
#Mann= 3 , 0 , 0
   -13.4    .035       0       0    .035       0      12    .035       0
#XS Ineff= 2 , 0
               0   57.68      12           57.63
Permanent Ineff=
       F       F
Bank Sta=0,12
XS Rating Curve= 0
Exp/Cntr=.3,.1

Type RM Length L Ch R = 1 ,300.00  ,50,50,50
BEGIN DESCRIPTION:
6
END DESCRIPTION:
#Sta/Elev= 17
   -13.4   56.34    -3.4   56.34    -2.2   57.34    -1.2   57.34     -.2   57.14
     -.2   57.34       0   57.34       0   54.89      12   54.89      12   57.39
    16.2   57.39    17.2   56.69    17.2   56.09    17.8   56.09    17.8   56.69
    19.7   58.69    29.7   58.69
#Mann= 3 , 0 , 0
   -13.4    .035       0       0    .035       0      12    .035       0
#XS Ineff= 2 , 0
               0   57.34      12           57.39
Permanent Ineff=
       F       F
Bank Sta=0,12
XS Rating Curve= 0
Exp/Cntr=.3,.1

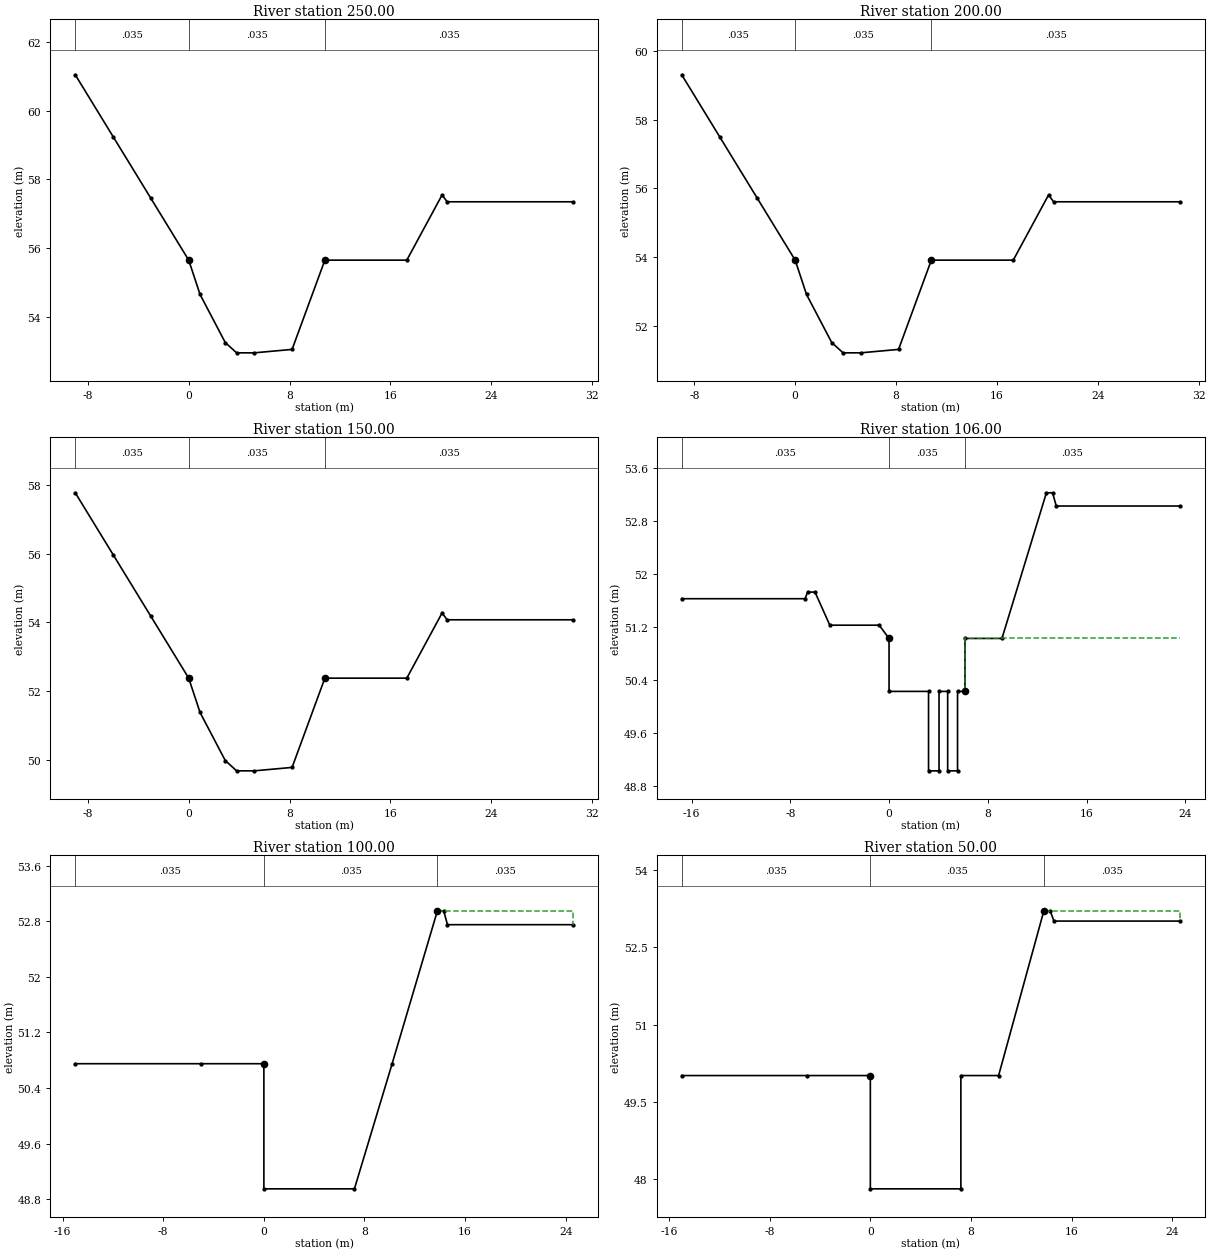
Type RM Length L Ch R = 1 ,250.00  ,50,50,50
BEGIN DESCRIPTION:
5
END DESCRIPTION:
#Sta/Elev= 14
      -9   61.05      -6   59.25      -3   57.45       0   55.65      .9   54.65
     2.9   53.25     3.8   52.95     5.2   52.95     8.2   53.05    10.8   55.65
    17.3   55.65    20.1   57.55    20.5   57.35    30.5   57.35
#Mann= 3 , 0 , 0
      -9    .035       0       0    .035       0    10.8    .035       0
#XS Ineff= 2 , 0
               0   55.65    10.8           55.65
Permanent Ineff=
       F       F
Bank Sta=0,10.8
XS Rating Curve= 0
Exp/Cntr=.3,.1

Type RM Length L Ch R = 1 ,200.00  ,50,50,50
BEGIN DESCRIPTION:
4
END DESCRIPTION:
#Sta/Elev= 14
      -9   59.31      -6   57.51      -3   55.71       0   53.91      .9   52.91
     2.9   51.51     3.8   51.21     5.2   51.21     8.2   51.31    10.8   53.91
    17.3   53.91    20.1   55.81    20.5   55.61    30.5   55.61
#Mann= 3 , 0 , 0
      -9    .035       0       0    .035       0    10.8    .035       0
#XS Ineff= 2 , 0
               0   53.91    10.8           53.91
Permanent Ineff=
       F       F
Bank Sta=0,10.8
XS Rating Curve= 0
Exp/Cntr=.3,.1

Type RM Length L Ch R = 1 ,150.00  ,44,44,44
BEGIN DESCRIPTION:
3
END DESCRIPTION:
#Sta/Elev= 14
      -9   57.77      -6   55.97      -3   54.17       0   52.37      .9   51.37
     2.9   49.97     3.8   49.67     5.2   49.67     8.2   49.77    10.8   52.37
    17.3   52.37    20.1   54.27    20.5   54.07    30.5   54.07
#Mann= 3 , 0 , 0
      -9    .035       0       0    .035       0    10.8    .035       0
#XS Ineff= 2 , 0
               0   52.37    10.8           52.37
Permanent Ineff=
       F       F
Bank Sta=0,10.8
XS Rating Curve= 0
Exp/Cntr=.3,.1

Type RM Length L Ch R = 1 ,106.00  ,6,6,6
BEGIN DESCRIPTION:
2.006
END DESCRIPTION:
#Sta/Elev= 23
   -16.8   51.63    -6.8   51.63    -6.6   51.73      -6   51.73    -4.8   51.23
     -.8   51.23       0   51.03       0   50.23     3.2   50.23     3.2   49.03
    4.05   49.03    4.05   50.23    4.75   50.23    4.75   49.03    5.55   49.03
    5.55   50.23    6.15   50.23    6.15   51.03    9.15   51.03   12.75   53.23
   13.25   53.23   13.55   53.03   23.55   53.03
#Mann= 3 , 0 , 0
   -16.8    .035       0       0    .035       0    6.15    .035       0
#XS Ineff= 2 , 0
               0   51.03    6.15           51.03
Permanent Ineff=
       F       F
Bank Sta=0,6.15
XS Rating Curve= 0
Exp/Cntr=.3,.1

Type RM Length L Ch R = 1 ,100.00  ,50,50,50
BEGIN DESCRIPTION:
2
END DESCRIPTION:
#Sta/Elev= 10
     -15   50.75      -5   50.75       0   50.75       0   48.95     7.2   48.95
    10.2   50.75    13.8   52.95    14.3   52.95    14.6   52.75    24.6   52.75
#Mann= 3 , 0 , 0
     -15    .035       0       0    .035       0    13.8    .035       0
#XS Ineff= 2 , 0
       0       0   50.75    13.8       0   52.95
Permanent Ineff=
       F       F
Bank Sta=0,13.8
XS Rating Curve= 0
Exp/Cntr=.3,.1

Type RM Length L Ch R = 1 ,50.00   ,49,49,49
BEGIN DESCRIPTION:
1
END DESCRIPTION:
#Sta/Elev= 11
     -15   50.01      -5   50.01       0   50.01       0   47.81     7.2   47.81
     7.2   50.01    10.2   50.01    13.8   53.21    14.3   53.21    14.6   53.01
    24.6   53.01
#Mann= 3 , 0 , 0
     -15    .035       0       0    .035       0    13.8    .035       0
#XS Ineff= 2 , 0
               0   50.01    13.8           53.21
Permanent Ineff=
       F       F
Bank Sta=0,13.8
XS Rating Curve= 0
Exp/Cntr=.3,.1

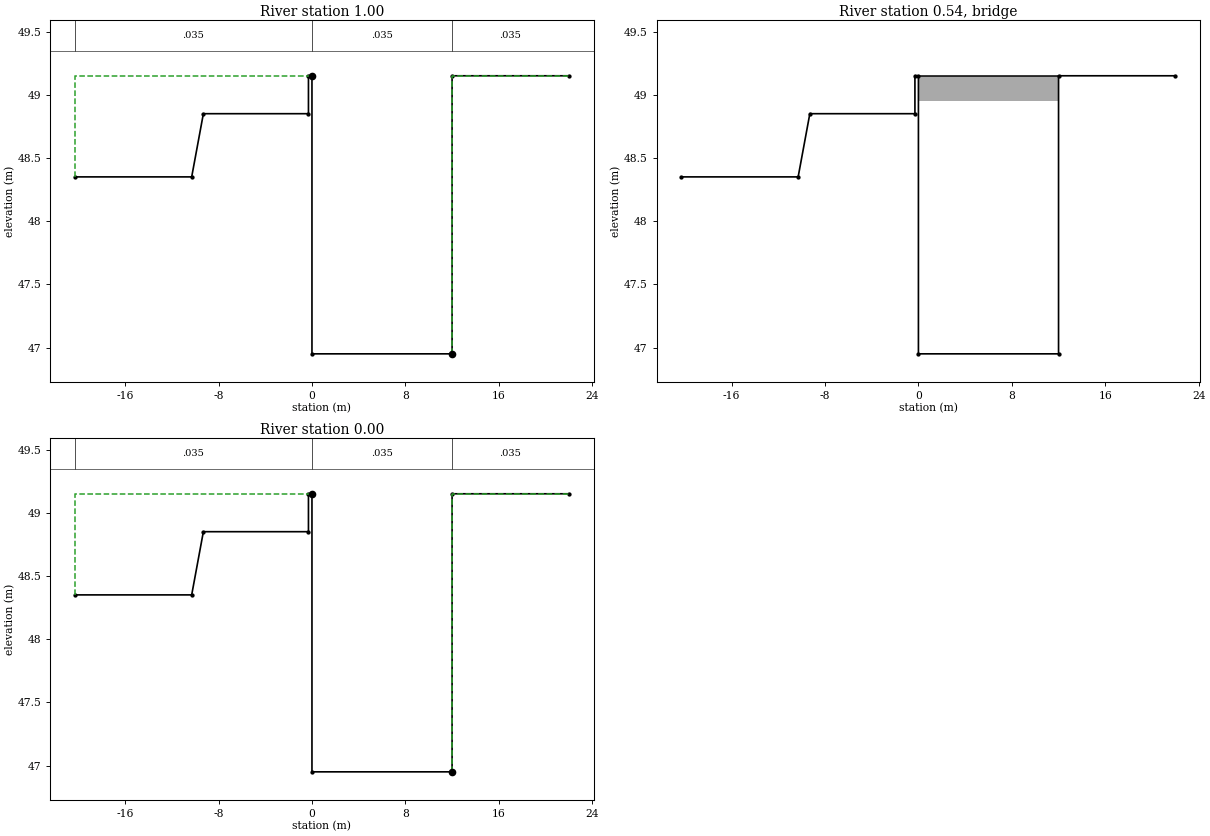
Type RM Length L Ch R = 1 ,1.00    ,1,1,1
BEGIN DESCRIPTION:
0.001
END DESCRIPTION:
#Sta/Elev= 10
   -20.3   48.35   -10.3   48.35    -9.3   48.85     -.3   48.85     -.3   49.15
       0   49.15       0   46.95      12   46.95      12   49.15      22   49.15
#Mann= 3 , 0 , 0
   -20.3    .035       0       0    .035       0      12    .035       0
#XS Ineff= 2 , 0
               0   49.15      12           49.15
Permanent Ineff=
       F       F
Bank Sta=0,12
XS Rating Curve= 0
Exp/Cntr=.3,.1

Type RM Length L Ch R = 3 ,0.54    ,,,
BEGIN DESCRIPTION:
0.0005
END DESCRIPTION:
Bridge Culvert--1,0,-1,-1, 0
Deck Dist Width WeirC Skew NumUp NumDn MinLoCord MaxHiCord MaxSubmerge Is_Ogee
.01,.9,1.44,0, 2, 2, , , .95, 0, 0,0,,
       0      12
   49.15   49.15
   48.95   48.95
       0      12
   49.15   49.15
   48.95   48.95
BR Coef=-1 , 1 , 0 ,, 0 ,,,.8,-1,1.2,0,
WSPro=,,,, 1 ,,,, 0 ,,,, 0 ,,,,-1 ,-1 ,-1 , 0 , 0 , 0 , 0 , 0
BC Design=,, 0 ,, 0 ,,,,,,

Type RM Length L Ch R = 1 ,0.00    ,0,0,0
BEGIN DESCRIPTION:
0
END DESCRIPTION:
#Sta/Elev= 10
   -20.3   48.35   -10.3   48.35    -9.3   48.85     -.3   48.85     -.3   49.15
       0   49.15       0   46.95      12   46.95      12   49.15      22   49.15
#Mann= 3 , 0 , 0
   -20.3    .035       0       0    .035       0      12    .035       0
#XS Ineff= 2 , 0
               0   49.15      12           49.15
Permanent Ineff=
       F       F
Bank Sta=0,12
XS Rating Curve= 0
Exp/Cntr=.3,.1

Chan Stop Cuts=-1