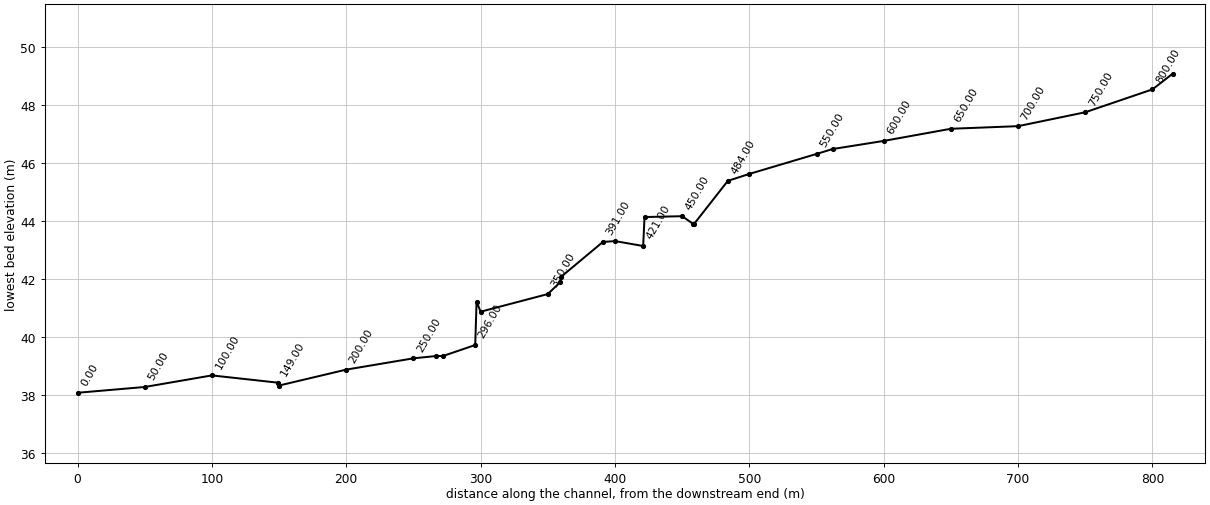
--- hmc.prj (project) ---

Proj Title=hwamang
Current Plan=p01
Default Exp/Contr=.3,.1
SI Units
Geom File=g01
Flow File=f01
Plan File=p01
Y Axis Title=Elevation
X Axis Title(PF)=Main Channel Distance
X Axis Title(XS)=Station
BEGIN DESCRIPTION:
           BACK WATER COMPUTATION
      APPLICATION OF HEC-2 BY Samju Construction Engineering
      È­¸ÁÃµ(¿ËÃµÀ¾): 30,50,80,100,150³âºóµµ °³¼öÀü
END DESCRIPTION:
DSS Export Rating Curves= 0
DSS Export Rating Curve Sorted= 0
DSS Export Volume Flow Curves= 0
DXF OffsetX= 0
DXF OffsetY= 0
DXF ScaleX= 1
DXF ScaleY= 10

--- hmc.p01 (plan) ---

Plan Title=Imported Plan 01
Version=Version 3.0.1  Mar 2001
Short Identifier=Imported Pla
Geom File=g01
Flow File=f01
Subcritical Flow
K Sum by GR= 0
Std Step Tol= 0.003
Critical Tol= 0.003
Num of Std Step Trials= 20
Max Error Tol= 0.1
Flow Tol Ratio= 0.001
Split Flow NTrial= 30
Split Flow Tol= 0.02
Split Flow Ratio= 0.02
Log Output Level= 0
Friction Slope Method= 1
Unsteady Friction Slope Method= 2
Parabolic Critical Depth
Global Vel Dist= 0 , 0 , 0
Global Log Level= 0
CheckData=True
Encroach Param=-1 ,0,0, 0
Computation Interval=1HOUR
Output Interval=1HOUR
Run HTab= 0
Run UNet= 0
Run PostProcess= 0
UNET Theta= 1
UNET ZTol= 0.02
UNET ZSATol= 0.1
UNET MxIter= 20
UNET MaxInSteps= 20
UNET DtIC= 0
UNET DtMin= 0
UNET MaxCRTS= 20
UNET WFStab= 2
UNET SFStab= 1
UNET WFX= 1
UNET SFX= 1
UNET Convert EG Bridges=-1
UNET Use Existing IB Tables=-1
Instantaneous Interval=1HOUR
Write IC File= 0
Write Velocity= 0
Write Detailed= 0

--- hmc.f01 (steady flow) ---

Flow Title=Imported Flow 01
Version=Version 3.0.1  Mar 2001
Number of Profiles= 5
Profile Names=10yr,20yr,30yr,50yr,80yr
River Rch & RM=RIVER-1,Reach-1         ,16.015
   11.45   12.62    13.3   14.16   14.95
River Rch & RM=hwamang,hwamang         ,815.00
   11.45   12.62    13.3   14.16   14.95
Boundary for River Rch & Prof#=hwamang,hwamang         , 1
Up Type= 0
Dn Type= 3
Dn Slope=.0137
Boundary for River Rch & Prof#=hwamang,hwamang         , 2
Up Type= 0
Dn Type= 3
Dn Slope=.0137
Boundary for River Rch & Prof#=hwamang,hwamang         , 3
Up Type= 0
Dn Type= 3
Dn Slope=.0137
Boundary for River Rch & Prof#=hwamang,hwamang         , 4
Up Type= 0
Dn Type= 3
Dn Slope=.0137
Boundary for River Rch & Prof#=hwamang,hwamang         , 5
Up Type= 0
Dn Type= 3
Dn Slope=.0137
DSS Import GetInterval= 0
DSS Import GetPeak= 0
DSS Import FillOption= 0

--- hmc.g01 (geometry) ---

Geom Title=Imported Geom 01
Version=Version 3.0.1  Mar 2001

River Reach=hwamang         ,hwamang
Reach XY= 2
              .5             .95              .5             .05

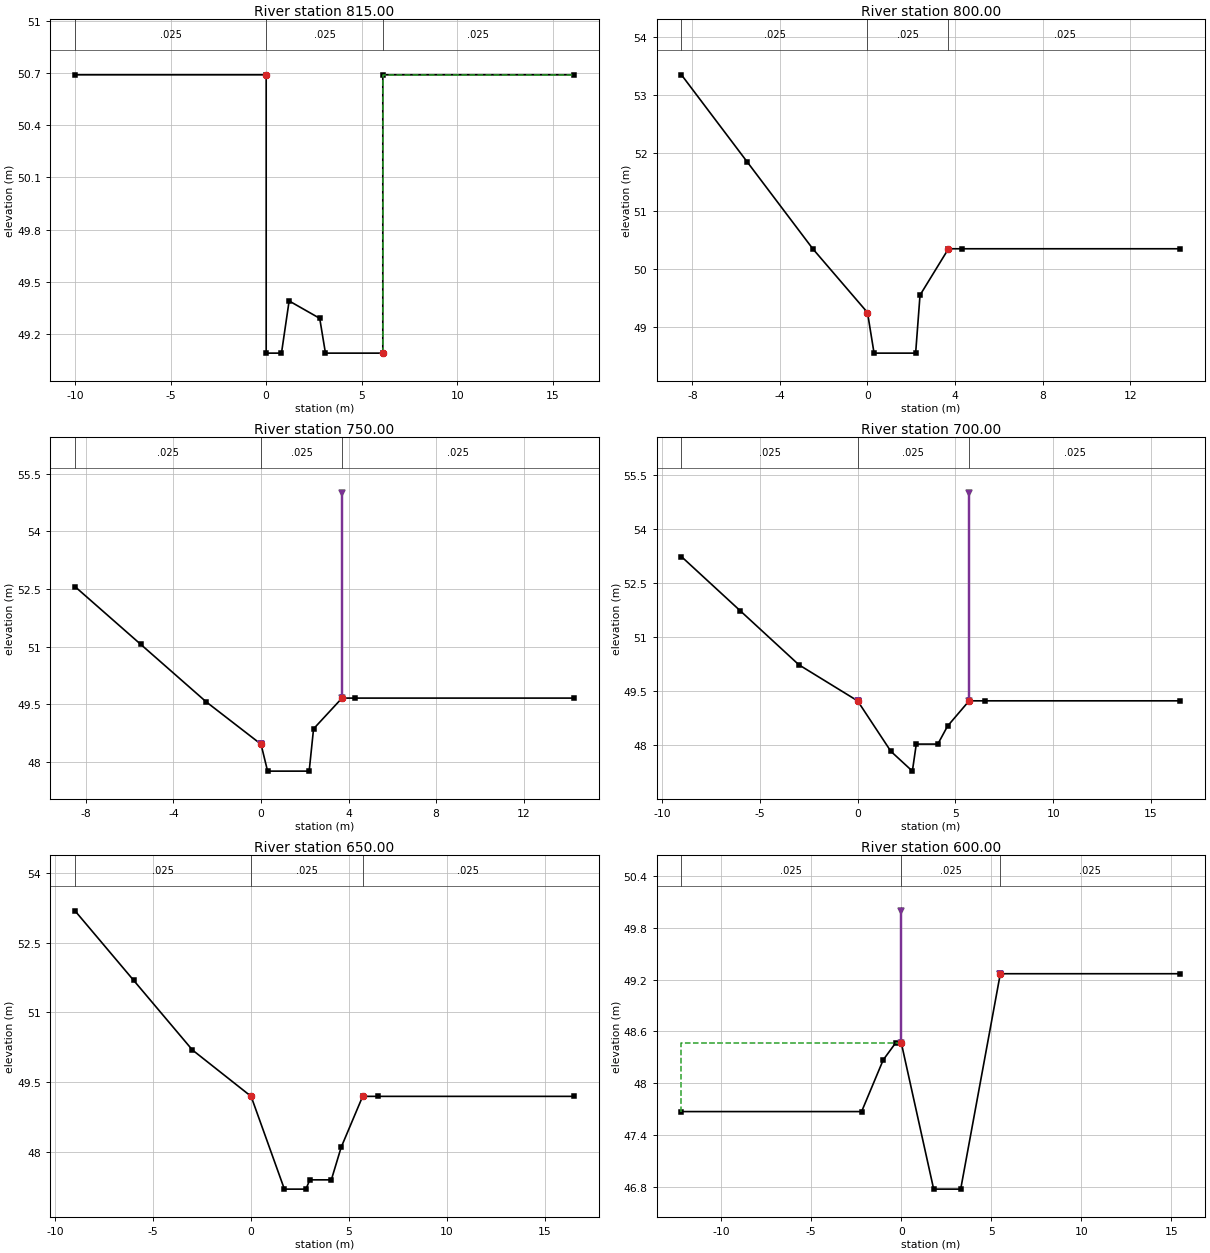
Type RM Length L Ch R = 1 ,815.00  ,15,15,15
BEGIN DESCRIPTION:
16.015
END DESCRIPTION:
#Sta/Elev= 10
     -10   50.69       0   50.69       0   49.09      .8   49.09     1.2   49.39
     2.8   49.29     3.1   49.09     6.1   49.09     6.1   50.69    16.1   50.69
#Mann= 3 , 0 , 0
     -10    .025       0       0    .025       0     6.1    .025       0
#XS Ineff= 2 , 0
               0   50.69     6.1           50.69
Permanent Ineff=
       F       F
Bank Sta=0,6.1
XS Rating Curve= 0
Exp/Cntr=.3,.1

Type RM Length L Ch R = 1 ,800.00  ,50,50,50
BEGIN DESCRIPTION:
16
END DESCRIPTION:
#Sta/Elev= 10
    -8.5   53.35    -5.5   51.85    -2.5   50.35       0   49.25      .3   48.55
     2.2   48.55     2.4   49.55     3.7   50.35     4.3   50.35    14.3   50.35
#Mann= 3 , 0 , 0
    -8.5    .025       0       0    .025       0     3.7    .025       0
#XS Ineff= 2 , 0
               0   49.25     3.7           50.35
Permanent Ineff=
       F       F
Bank Sta=0,3.7
XS Rating Curve= 0
Exp/Cntr=.3,.1

Type RM Length L Ch R = 1 ,750.00  ,50,50,50
BEGIN DESCRIPTION:
15
END DESCRIPTION:
#Sta/Elev= 10
    -8.5   52.56    -5.5   51.06    -2.5   49.56       0   48.46      .3   47.76
     2.2   47.76     2.4   48.86     3.7   49.66     4.3   49.66    14.3   49.66
#Mann= 3 , 0 , 0
    -8.5    .025       0       0    .025       0     3.7    .025       0
Levee=-1,0,48.46,-1,3.7,55,,
#XS Ineff= 2 , 0
               0   48.46     3.7           49.66
Permanent Ineff=
       F       F
Bank Sta=0,3.7
XS Rating Curve= 0
Exp/Cntr=.3,.1

Type RM Length L Ch R = 1 ,700.00  ,50,50,50
BEGIN DESCRIPTION:
14
END DESCRIPTION:
#Sta/Elev= 12
      -9   53.23      -6   51.73      -3   50.23       0   49.23     1.7   47.83
     2.8   47.28       3   48.03     4.1   48.03     4.6   48.53     5.7   49.23
     6.5   49.23    16.5   49.23
#Mann= 3 , 0 , 0
      -9    .025       0       0    .025       0     5.7    .025       0
Levee=-1,0,49.23,-1,5.7,55,,
#XS Ineff= 2 , 0
               0   49.23     5.7           49.23
Permanent Ineff=
       F       F
Bank Sta=0,5.7
XS Rating Curve= 0
Exp/Cntr=.3,.1

Type RM Length L Ch R = 1 ,650.00  ,50,50,50
BEGIN DESCRIPTION:
13
END DESCRIPTION:
#Sta/Elev= 12
      -9   53.19      -6   51.69      -3   50.19       0   49.19     1.7   47.19
     2.8   47.19       3   47.39     4.1   47.39     4.6   48.09     5.7   49.19
     6.5   49.19    16.5   49.19
#Mann= 3 , 0 , 0
      -9    .025       0       0    .025       0     5.7    .025       0
#XS Ineff= 2 , 0
               0   49.19     5.7           49.19
Permanent Ineff=
       F       F
Bank Sta=0,5.7
XS Rating Curve= 0
Exp/Cntr=.3,.1

Type RM Length L Ch R = 1 ,600.00  ,38,38,38
BEGIN DESCRIPTION:
12
END DESCRIPTION:
#Sta/Elev= 9
   -12.2   47.67    -2.2   47.67      -1   48.27     -.3   48.47       0   48.47
     1.8   46.77     3.3   46.77     5.5   49.27    15.5   49.27
#Mann= 3 , 0 , 0
   -12.2    .025       0       0    .025       0     5.5    .025       0
Levee=-1,0,50,-1,5.5,49.27,,
#XS Ineff= 2 , 0
               0   48.47     5.5           49.27
Permanent Ineff=
       F       F
Bank Sta=0,5.5
XS Rating Curve= 0
Exp/Cntr=.3,.1

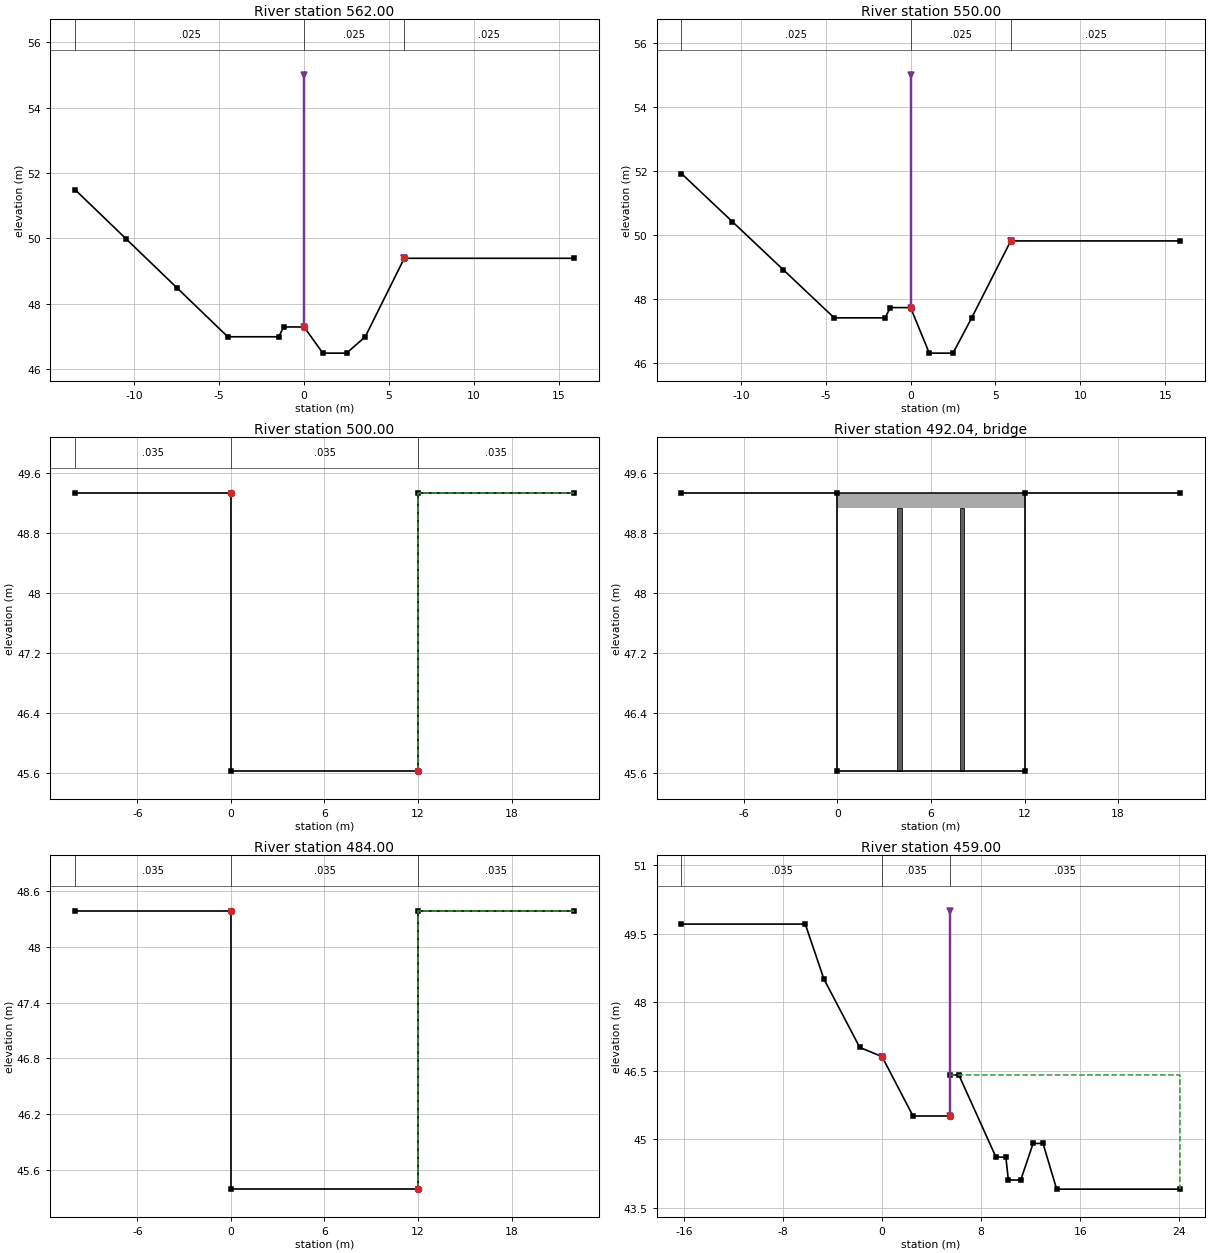
Type RM Length L Ch R = 1 ,562.00  ,12,12,12
BEGIN DESCRIPTION:
11.012
END DESCRIPTION:
#Sta/Elev= 12
   -13.5   51.49   -10.5   49.99    -7.5   48.49    -4.5   46.99    -1.5   46.99
    -1.2   47.29       0   47.29     1.1   46.49     2.5   46.49     3.6   46.99
     5.9   49.39    15.9   49.39
#Mann= 3 , 0 , 0
   -13.5    .025       0       0    .025       0     5.9    .025       0
Levee=-1,0,55,-1,5.9,49.39,,
#XS Ineff= 2 , 0
               0   47.29     5.9           49.39
Permanent Ineff=
       F       F
Bank Sta=0,5.9
XS Rating Curve= 0
Exp/Cntr=.3,.1

Type RM Length L Ch R = 1 ,550.00  ,50,50,50
BEGIN DESCRIPTION:
11
END DESCRIPTION:
#Sta/Elev= 12
   -13.5   51.92   -10.5   50.42    -7.5   48.92    -4.5   47.42    -1.5   47.42
    -1.2   47.74       0   47.74     1.1   46.32     2.5   46.32     3.6   47.42
     5.9   49.82    15.9   49.82
#Mann= 3 , 0 , 0
   -13.5    .025       0       0    .025       0     5.9    .025       0
Levee=-1,0,55,-1,5.9,49.82,,
#XS Ineff= 2 , 0
               0   47.74     5.9           49.82
Permanent Ineff=
       F       F
Bank Sta=0,5.9
XS Rating Curve= 0
Exp/Cntr=.3,.1

Type RM Length L Ch R = 1 ,500.00  ,16,16,16
BEGIN DESCRIPTION:
10
END DESCRIPTION:
#Sta/Elev= 6
     -10   49.33       0   49.33       0   45.63      12   45.63      12   49.33
      22   49.33
#Mann= 3 , 0 , 0
     -10    .035       0       0    .035       0      12    .035       0
#XS Ineff= 2 , 0
               0   49.33      12           49.33
Permanent Ineff=
       F       F
Bank Sta=0,12
XS Rating Curve= 0
Exp/Cntr=.3,.1

Type RM Length L Ch R = 3 ,492.04  ,,,
BEGIN DESCRIPTION:
9.042
END DESCRIPTION:
Bridge Culvert--1,0,-1,-1, 0
Deck Dist Width WeirC Skew NumUp NumDn MinLoCord MaxHiCord MaxSubmerge Is_Ogee
.01,15.9,1.44,0, 2, 2, , , .95, 0, 0,0,,
       0      12
   49.33   49.33
   49.13   49.13
       0      12
   48.39   48.39
   48.19   48.19
Pier Skew, UpSta & Num, DnSta & Num=  ,4, 2 ,4, 2 , 0 , 0 , 0 ,,
      .3      .3
   45.63   49.33
      .3      .3
   45.39   58.39
Pier Skew, UpSta & Num, DnSta & Num=  ,8, 2 ,8, 2 , 0 , 0 , 0 ,,
      .3      .3
   45.63   49.33
      .3      .3
   45.39   58.39
BR Coef=-1 , 1 , 1 ,.9, 0 ,,,.8,-1,1.2,0,
WSPro=,,,, 1 ,,,, 0 ,,,, 0 ,,,,-1 ,-1 ,-1 , 0 , 0 , 0 , 0 , 0
BC Design=,, 0 ,, 0 ,,,,,,

Type RM Length L Ch R = 1 ,484.00  ,25,25,25
BEGIN DESCRIPTION:
9.034
END DESCRIPTION:
#Sta/Elev= 6
     -10   48.39       0   48.39       0   45.39      12   45.39      12   48.39
      22   48.39
#Mann= 3 , 0 , 0
     -10    .035       0       0    .035       0      12    .035       0
#XS Ineff= 2 , 0
               0   48.39      12           48.39
Permanent Ineff=
       F       F
Bank Sta=0,12
XS Rating Curve= 0
Exp/Cntr=.3,.1

Type RM Length L Ch R = 1 ,459.00  ,1,1,1
BEGIN DESCRIPTION:
9.009
END DESCRIPTION:
#Sta/Elev= 17
   -16.2   49.71    -6.2   49.71    -4.7   48.51    -1.8   47.01       0   46.81
     2.5   45.51     5.5   45.51     5.5   46.41     6.2   46.41     9.2   44.61
      10   44.61    10.2   44.11    11.2   44.11    12.2   44.91      13   44.91
    14.1   43.91    24.1   43.91
#Mann= 3 , 0 , 0
   -16.2    .035       0       0    .035       0     5.5    .035       0
Levee=-1,0,46.81,-1,5.5,50,,
#XS Ineff= 2 , 0
               0   46.81     5.5           46.41
Permanent Ineff=
       F       F
Bank Sta=0,5.5
XS Rating Curve= 0
Exp/Cntr=.3,.1

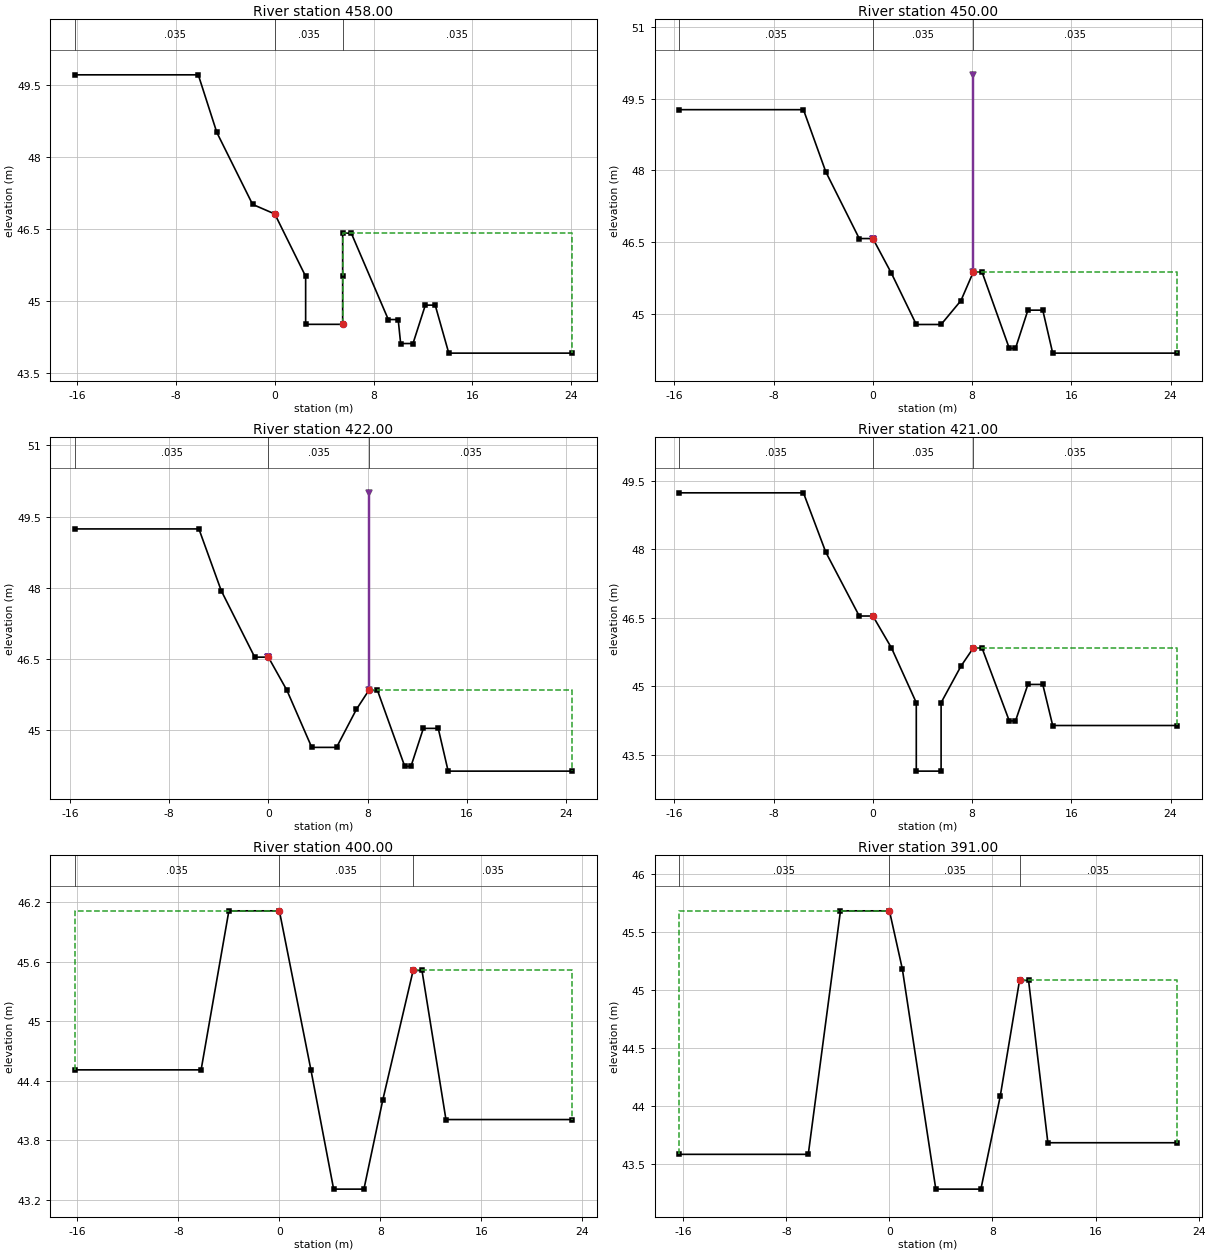
Type RM Length L Ch R = 1 ,458.00  ,8,8,8
BEGIN DESCRIPTION:
9.008
END DESCRIPTION:
#Sta/Elev= 19
   -16.2   49.71    -6.2   49.71    -4.7   48.51    -1.8   47.01       0   46.81
     2.5   45.51     2.5   44.51     5.5   44.51     5.5   45.51     5.5   46.41
     6.2   46.41     9.2   44.61      10   44.61    10.2   44.11    11.2   44.11
    12.2   44.91      13   44.91    14.1   43.91    24.1   43.91
#Mann= 3 , 0 , 0
   -16.2    .035       0       0    .035       0     5.5    .035       0
#XS Ineff= 2 , 0
               0   46.81     5.5           46.41
Permanent Ineff=
       F       F
Bank Sta=0,5.5
XS Rating Curve= 0
Exp/Cntr=.3,.1

Type RM Length L Ch R = 1 ,450.00  ,28,28,28
BEGIN DESCRIPTION:
9
END DESCRIPTION:
#Sta/Elev= 17
   -15.6   49.27    -5.6   49.27    -3.8   47.97    -1.1   46.57       0   46.57
     1.5   45.84     3.5   44.77     5.5   44.77     7.1   45.27     8.1   45.87
     8.8   45.87      11   44.27    11.5   44.27    12.5   45.07    13.7   45.07
    14.5   44.17    24.5   44.17
#Mann= 3 , 0 , 0
   -15.6    .035       0       0    .035       0     8.1    .035       0
Levee=-1,0,46.57,-1,8.1,50,,
#XS Ineff= 2 , 0
               0   46.57     8.1           45.87
Permanent Ineff=
       F       F
Bank Sta=0,8.1
XS Rating Curve= 0
Exp/Cntr=.3,.1

Type RM Length L Ch R = 1 ,422.00  ,1,1,1
BEGIN DESCRIPTION:
8.022
END DESCRIPTION:
#Sta/Elev= 17
   -15.6   49.24    -5.6   49.24    -3.8   47.94    -1.1   46.54       0   46.54
     1.5   45.84     3.5   44.64     5.5   44.64     7.1   45.44     8.1   45.84
     8.8   45.84      11   44.24    11.5   44.24    12.5   45.04    13.7   45.04
    14.5   44.14    24.5   44.14
#Mann= 3 , 0 , 0
   -15.6    .035       0       0    .035       0     8.1    .035       0
Levee=-1,0,46.54,-1,8.1,50,,
#XS Ineff= 2 , 0
               0   46.54     8.1           45.84
Permanent Ineff=
       F       F
Bank Sta=0,8.1
XS Rating Curve= 0
Exp/Cntr=.3,.1

Type RM Length L Ch R = 1 ,421.00  ,21,21,21
BEGIN DESCRIPTION:
8.021
END DESCRIPTION:
#Sta/Elev= 19
   -15.6   49.24    -5.6   49.24    -3.8   47.94    -1.1   46.54       0   46.54
     1.5   45.84     3.5   44.64     3.5   43.14     5.5   43.14     5.5   44.64
     7.1   45.44     8.1   45.84     8.8   45.84      11   44.24    11.5   44.24
    12.5   45.04    13.7   45.04    14.5   44.14    24.5   44.14
#Mann= 3 , 0 , 0
   -15.6    .035       0       0    .035       0     8.1    .035       0
#XS Ineff= 2 , 0
               0   46.54     8.1           45.84
Permanent Ineff=
       F       F
Bank Sta=0,8.1
XS Rating Curve= 0
Exp/Cntr=.3,.1

Type RM Length L Ch R = 1 ,400.00  ,9,9,9
BEGIN DESCRIPTION:
8
END DESCRIPTION:
#Sta/Elev= 12
   -16.2   44.51    -6.2   44.51      -4   46.11       0   46.11     2.5   44.51
     4.3   43.31     6.7   43.31     8.2   44.21    10.6   45.51    11.3   45.51
    13.2   44.01    23.2   44.01
#Mann= 3 , 0 , 0
   -16.2    .035       0       0    .035       0    10.6    .035       0
#XS Ineff= 2 , 0
               0   46.11    10.6           45.51
Permanent Ineff=
       F       F
Bank Sta=0,10.6
XS Rating Curve= 0
Exp/Cntr=.3,.1

Type RM Length L Ch R = 1 ,391.00  ,31,31,31
BEGIN DESCRIPTION:
7.041
END DESCRIPTION:
#Sta/Elev= 12
   -16.3   43.58    -6.3   43.58    -3.8   45.68       0   45.68       1   45.18
     3.6   43.28     7.1   43.28     8.6   44.08    10.1   45.08    10.8   45.08
    12.3   43.68    22.3   43.68
#Mann= 3 , 0 , 0
   -16.3    .035       0       0    .035       0    10.1    .035       0
#XS Ineff= 2 , 0
               0   45.68    10.1           45.08
Permanent Ineff=
       F       F
Bank Sta=0,10.1
XS Rating Curve= 0
Exp/Cntr=.3,.1

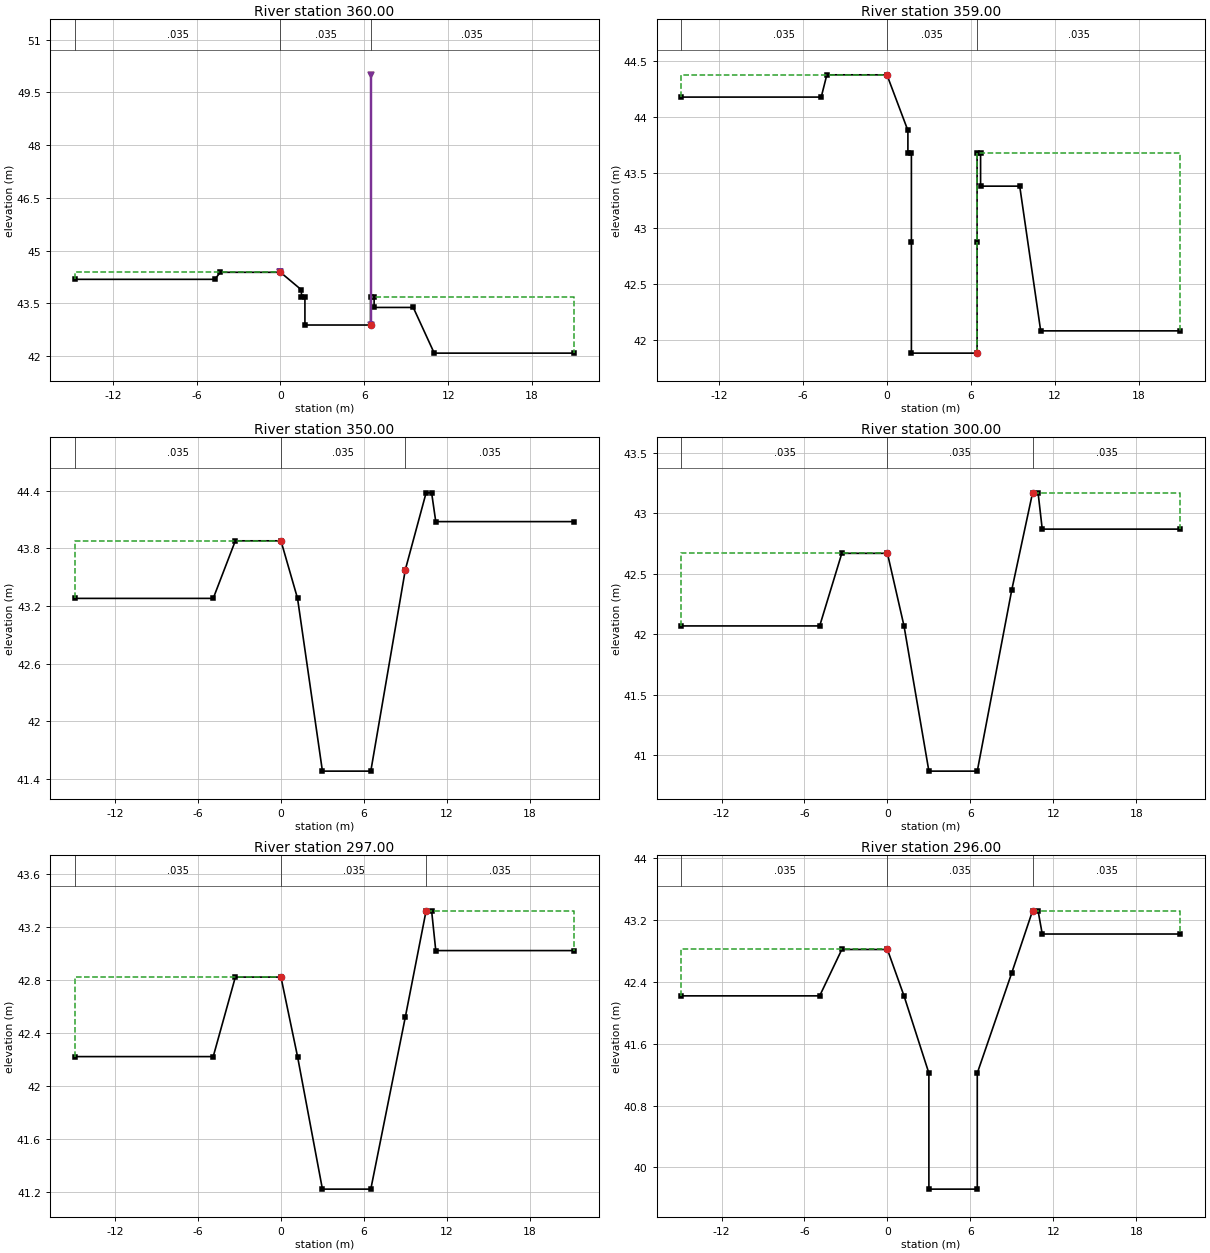
Type RM Length L Ch R = 1 ,360.00  ,1,1,1
BEGIN DESCRIPTION:
7.01
END DESCRIPTION:
#Sta/Elev= 15
   -14.7   44.18    -4.7   44.18    -4.3   44.38       0   44.38     1.5   43.88
     1.5   43.68    1.75   43.68    1.75   42.88    6.45   42.88    6.45   43.68
     6.7   43.68     6.7   43.38     9.5   43.38      11   42.08      21   42.08
#Mann= 3 , 0 , 0
   -14.7    .035       0       0    .035       0    6.45    .035       0
Levee=-1,0,44.38,-1,6.45,50,,
#XS Ineff= 2 , 0
               0   44.38    6.45           43.68
Permanent Ineff=
       F       F
Bank Sta=0,6.45
XS Rating Curve= 0
Exp/Cntr=.3,.1

Type RM Length L Ch R = 1 ,359.00  ,9,9,9
BEGIN DESCRIPTION:
7.009
END DESCRIPTION:
#Sta/Elev= 17
   -14.7   44.18    -4.7   44.18    -4.3   44.38       0   44.38     1.5   43.88
     1.5   43.68    1.75   43.68    1.75   42.88    1.75   41.88    6.45   41.88
    6.45   42.88    6.45   43.68     6.7   43.68     6.7   43.38     9.5   43.38
      11   42.08      21   42.08
#Mann= 3 , 0 , 0
   -14.7    .035       0       0    .035       0    6.45    .035       0
#XS Ineff= 2 , 0
               0   44.38    6.45           43.68
Permanent Ineff=
       F       F
Bank Sta=0,6.45
XS Rating Curve= 0
Exp/Cntr=.3,.1

Type RM Length L Ch R = 1 ,350.00  ,50,50,50
BEGIN DESCRIPTION:
7
END DESCRIPTION:
#Sta/Elev= 12
   -14.9   43.28    -4.9   43.28    -3.3   43.88       0   43.88     1.2   43.28
       3   41.48     6.5   41.48       9   43.58    10.5   44.38    10.9   44.38
    11.2   44.08    21.2   44.08
#Mann= 3 , 0 , 0
   -14.9    .035       0       0    .035       0       9    .035       0
#XS Ineff= 2 , 0
               0   43.88       9           43.58
Permanent Ineff=
       F       F
Bank Sta=0,9
XS Rating Curve= 0
Exp/Cntr=.3,.1

Type RM Length L Ch R = 1 ,300.00  ,3,3,3
BEGIN DESCRIPTION:
6
END DESCRIPTION:
#Sta/Elev= 12
   -14.9   42.07    -4.9   42.07    -3.3   42.67       0   42.67     1.2   42.07
       3   40.87     6.5   40.87       9   42.37    10.5   43.17    10.9   43.17
    11.2   42.87    21.2   42.87
#Mann= 3 , 0 , 0
   -14.9    .035       0       0    .035       0    10.5    .035       0
#XS Ineff= 2 , 0
               0   42.67    10.5           43.17
Permanent Ineff=
       F       F
Bank Sta=0,10.5
XS Rating Curve= 0
Exp/Cntr=.3,.1

Type RM Length L Ch R = 1 ,297.00  ,1,1,1
BEGIN DESCRIPTION:
5.047
END DESCRIPTION:
#Sta/Elev= 12
   -14.9   42.22    -4.9   42.22    -3.3   42.82       0   42.82     1.2   42.22
       3   41.22     6.5   41.22       9   42.52    10.5   43.32    10.9   43.32
    11.2   43.02    21.2   43.02
#Mann= 3 , 0 , 0
   -14.9    .035       0       0    .035       0    10.5    .035       0
#XS Ineff= 2 , 0
               0   42.82    10.5           43.32
Permanent Ineff=
       F       F
Bank Sta=0,10.5
XS Rating Curve= 0
Exp/Cntr=.3,.1

Type RM Length L Ch R = 1 ,296.00  ,24,24,24
BEGIN DESCRIPTION:
5.046
END DESCRIPTION:
#Sta/Elev= 14
   -14.9   42.22    -4.9   42.22    -3.3   42.82       0   42.82     1.2   42.22
       3   41.22       3   39.72     6.5   39.72     6.5   41.22       9   42.52
    10.5   43.32    10.9   43.32    11.2   43.02    21.2   43.02
#Mann= 3 , 0 , 0
   -14.9    .035       0       0    .035       0    10.5    .035       0
#XS Ineff= 2 , 0
               0   42.82    10.5           43.32
Permanent Ineff=
       F       F
Bank Sta=0,10.5
XS Rating Curve= 0
Exp/Cntr=.3,.1

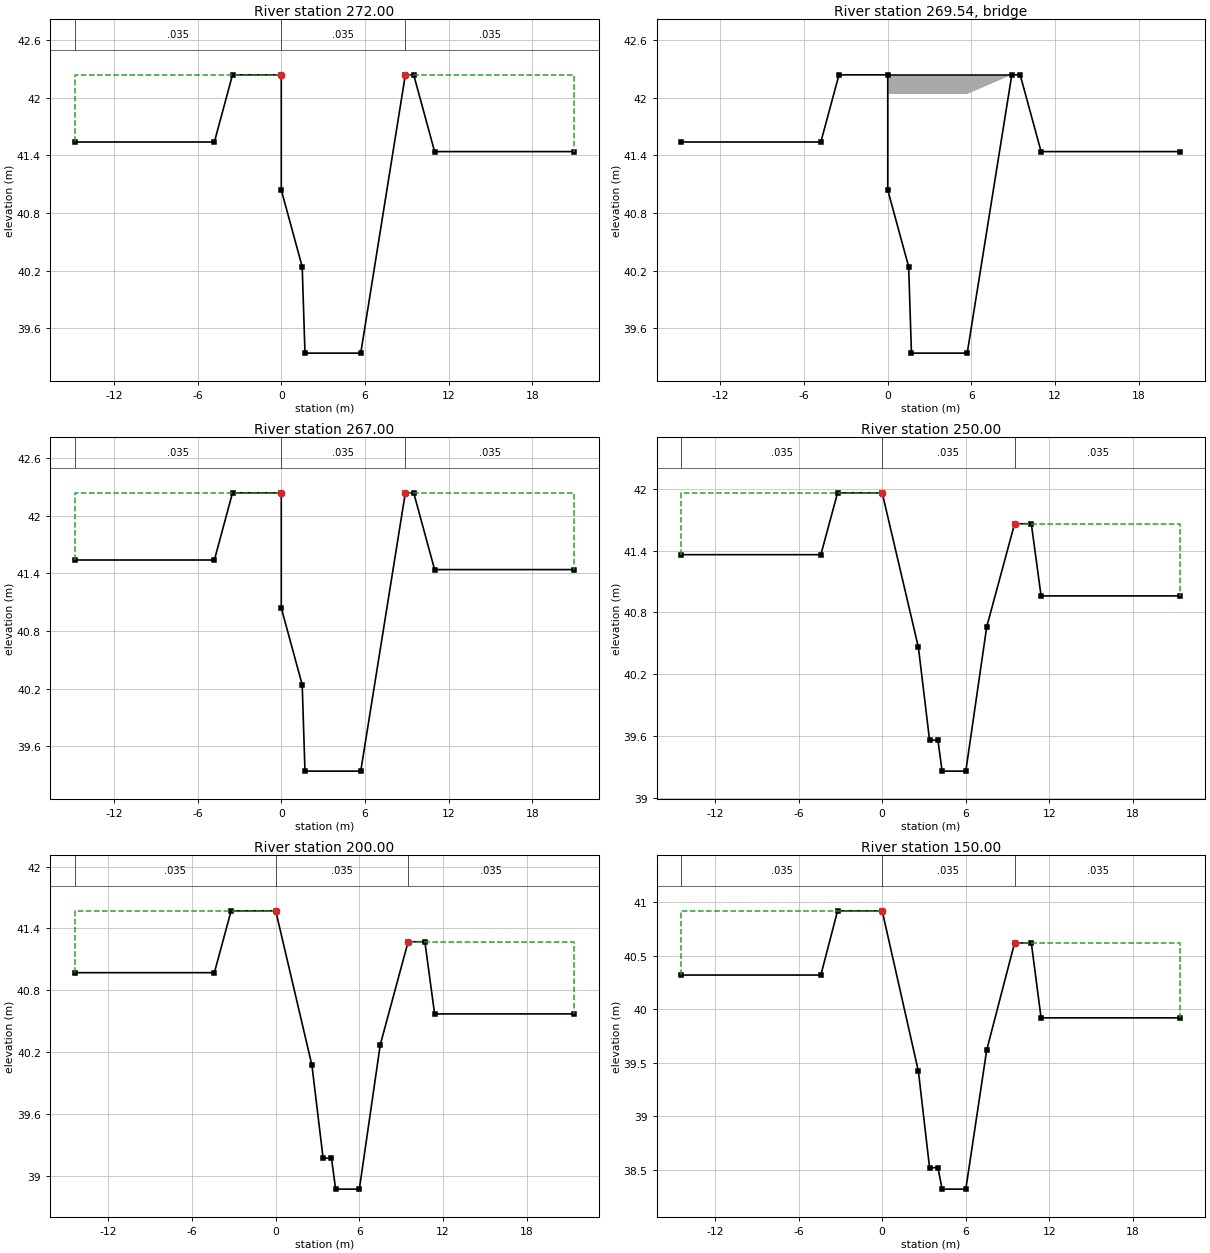
Type RM Length L Ch R = 1 ,272.00  ,5,5,5
BEGIN DESCRIPTION:
5.022
END DESCRIPTION:
#Sta/Elev= 12
   -14.8   41.54    -4.8   41.54    -3.5   42.24       0   42.24       0   41.04
     1.5   40.24     1.7   39.34     5.7   39.34     8.9   42.24     9.5   42.24
      11   41.44      21   41.44
#Mann= 3 , 0 , 0
   -14.8    .035       0       0    .035       0     8.9    .035       0
#XS Ineff= 2 , 0
               0   42.24     8.9           42.24
Permanent Ineff=
       F       F
Bank Sta=0,8.9
XS Rating Curve= 0
Exp/Cntr=.3,.1

Type RM Length L Ch R = 3 ,269.54  ,,,
BEGIN DESCRIPTION:
5.0195
END DESCRIPTION:
Bridge Culvert--1,0,-1,-1, 0
Deck Dist Width WeirC Skew NumUp NumDn MinLoCord MaxHiCord MaxSubmerge Is_Ogee
.01,4.9,1.44,0, 2, 2, , , .95, 0, 0,0,,
       0     8.9
   42.24   42.24
   42.04   42.04
       0     8.9
   42.24   42.24
   42.04   42.04
BR Coef=-1 , 1 , 0 ,, 0 ,,,.8,-1,1.2,0,
WSPro=,,,, 1 ,,,, 0 ,,,, 0 ,,,,-1 ,-1 ,-1 , 0 , 0 , 0 , 0 , 0
BC Design=,, 0 ,, 0 ,,,,,,

Type RM Length L Ch R = 1 ,267.00  ,17,17,17
BEGIN DESCRIPTION:
5.017
END DESCRIPTION:
#Sta/Elev= 12
   -14.8   41.54    -4.8   41.54    -3.5   42.24       0   42.24       0   41.04
     1.5   40.24     1.7   39.34     5.7   39.34     8.9   42.24     9.5   42.24
      11   41.44      21   41.44
#Mann= 3 , 0 , 0
   -14.8    .035       0       0    .035       0     8.9    .035       0
#XS Ineff= 2 , 0
               0   42.24     8.9           42.24
Permanent Ineff=
       F       F
Bank Sta=0,8.9
XS Rating Curve= 0
Exp/Cntr=.3,.1

Type RM Length L Ch R = 1 ,250.00  ,50,50,50
BEGIN DESCRIPTION:
5
END DESCRIPTION:
#Sta/Elev= 14
   -14.4   41.36    -4.4   41.36    -3.2   41.96       0   41.96     2.6   40.46
     3.4   39.56       4   39.56     4.3   39.26       6   39.26     7.5   40.66
     9.5   41.66    10.7   41.66    11.4   40.96    21.4   40.96
#Mann= 3 , 0 , 0
   -14.4    .035       0       0    .035       0     9.5    .035       0
#XS Ineff= 2 , 0
               0   41.96     9.5           41.66
Permanent Ineff=
       F       F
Bank Sta=0,9.5
XS Rating Curve= 0
Exp/Cntr=.3,.1

Type RM Length L Ch R = 1 ,200.00  ,50,50,50
BEGIN DESCRIPTION:
4
END DESCRIPTION:
#Sta/Elev= 14
   -14.4   40.97    -4.4   40.97    -3.2   41.57       0   41.57     2.6   40.07
     3.4   39.17       4   39.17     4.3   38.87       6   38.87     7.5   40.27
     9.5   41.27    10.7   41.27    11.4   40.57    21.4   40.57
#Mann= 3 , 0 , 0
   -14.4    .035       0       0    .035       0     9.5    .035       0
#XS Ineff= 2 , 0
               0   41.57     9.5           41.27
Permanent Ineff=
       F       F
Bank Sta=0,9.5
XS Rating Curve= 0
Exp/Cntr=.3,.1

Type RM Length L Ch R = 1 ,150.00  ,1,1,1
BEGIN DESCRIPTION:
3
END DESCRIPTION:
#Sta/Elev= 14
   -14.4   40.32    -4.4   40.32    -3.2   40.92       0   40.92     2.6   39.42
     3.4   38.52       4   38.52     4.3   38.32       6   38.32     7.5   39.62
     9.5   40.62    10.7   40.62    11.4   39.92    21.4   39.92
#Mann= 3 , 0 , 0
   -14.4    .035       0       0    .035       0     9.5    .035       0
#XS Ineff= 2 , 0
               0   40.92     9.5           40.62
Permanent Ineff=
       F       F
Bank Sta=0,9.5
XS Rating Curve= 0
Exp/Cntr=.3,.1

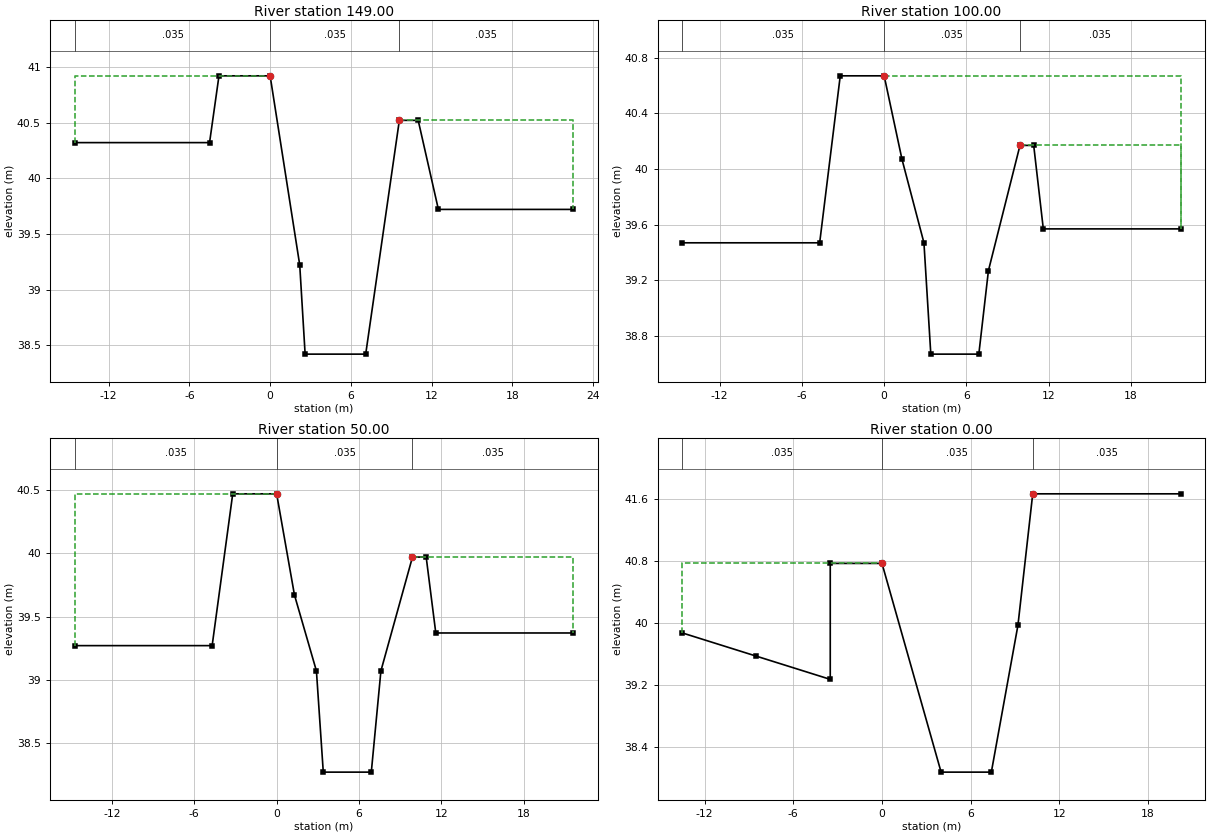
Type RM Length L Ch R = 1 ,149.00  ,49,49,49
BEGIN DESCRIPTION:
2.049
END DESCRIPTION:
#Sta/Elev= 11
   -14.5   40.32    -4.5   40.32    -3.8   40.92       0   40.92     2.2   39.22
     2.6   38.42     7.1   38.42     9.6   40.52      11   40.52    12.5   39.72
    22.5   39.72
#Mann= 3 , 0 , 0
   -14.5    .035       0       0    .035       0     9.6    .035       0
#XS Ineff= 2 , 0
               0   40.92     9.6           40.52
Permanent Ineff=
       F       F
Bank Sta=0,9.6
XS Rating Curve= 0
Exp/Cntr=.3,.1

Type RM Length L Ch R = 1 ,100.00  ,50,50,50
BEGIN DESCRIPTION:
2
END DESCRIPTION:
#Sta/Elev= 13
   -14.7   39.47    -4.7   39.47    -3.2   40.67       0   40.67     1.3   40.07
     2.9   39.47     3.4   38.67     6.9   38.67     7.6   39.27     9.9   40.17
    10.9   40.17    11.6   39.57    21.6   39.57
#Mann= 3 , 0 , 0
   -14.7    .035       0       0    .035       0     9.9    .035       0
#XS Ineff= 2 , 0
       0       0   40.67     9.9       0   40.17
Permanent Ineff=
       F       F
Bank Sta=0,9.9
XS Rating Curve= 0
Exp/Cntr=.3,.1

Type RM Length L Ch R = 1 ,50.00   ,50,50,50
BEGIN DESCRIPTION:
1
END DESCRIPTION:
#Sta/Elev= 13
   -14.7   39.27    -4.7   39.27    -3.2   40.47       0   40.47     1.3   39.67
     2.9   39.07     3.4   38.27     6.9   38.27     7.6   39.07     9.9   39.97
    10.9   39.97    11.6   39.37    21.6   39.37
#Mann= 3 , 0 , 0
   -14.7    .035       0       0    .035       0     9.9    .035       0
#XS Ineff= 2 , 0
               0   40.47     9.9           39.97
Permanent Ineff=
       F       F
Bank Sta=0,9.9
XS Rating Curve= 0
Exp/Cntr=.3,.1

Type RM Length L Ch R = 1 ,0.00    ,0,0,0
BEGIN DESCRIPTION:
0
END DESCRIPTION:
#Sta/Elev= 10
   -13.5   39.87    -8.5   39.57    -3.5   39.27    -3.5   40.77       0   40.77
       4   38.07     7.4   38.07     9.2   39.97    10.2   41.67    20.2   41.67
#Mann= 3 , 0 , 0
   -13.5    .035       0       0    .035       0    10.2    .035       0
#XS Ineff= 2 , 0
               0   40.77    10.2           41.67
Permanent Ineff=
       F       F
Bank Sta=0,10.2
XS Rating Curve= 0
Exp/Cntr=.3,.1

Chan Stop Cuts=-1