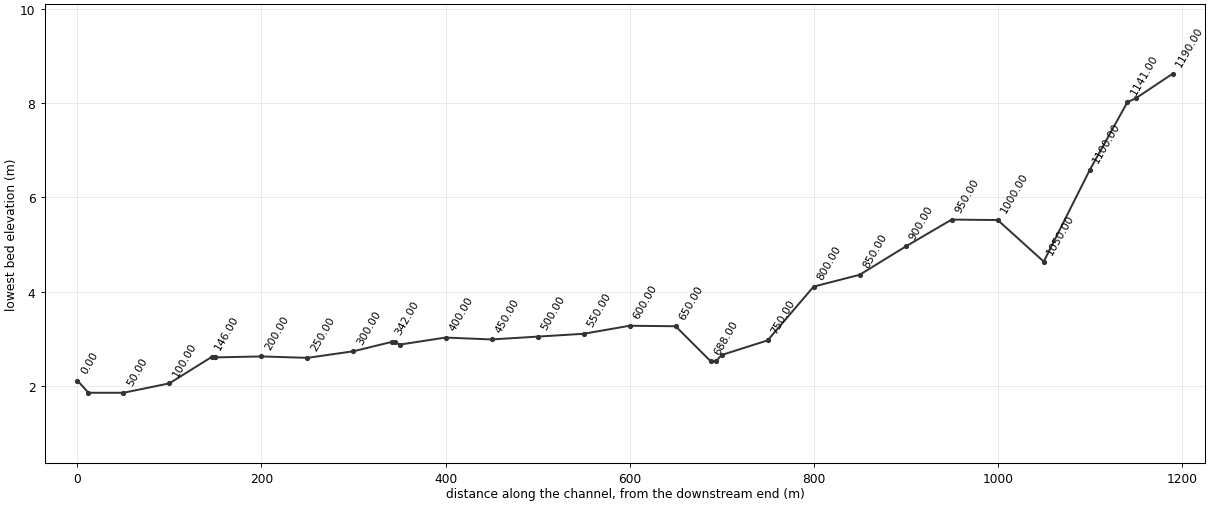
HEC-RAS study mcc.prj: MCW

--- mcc.g01 (geometry) --- (continued)

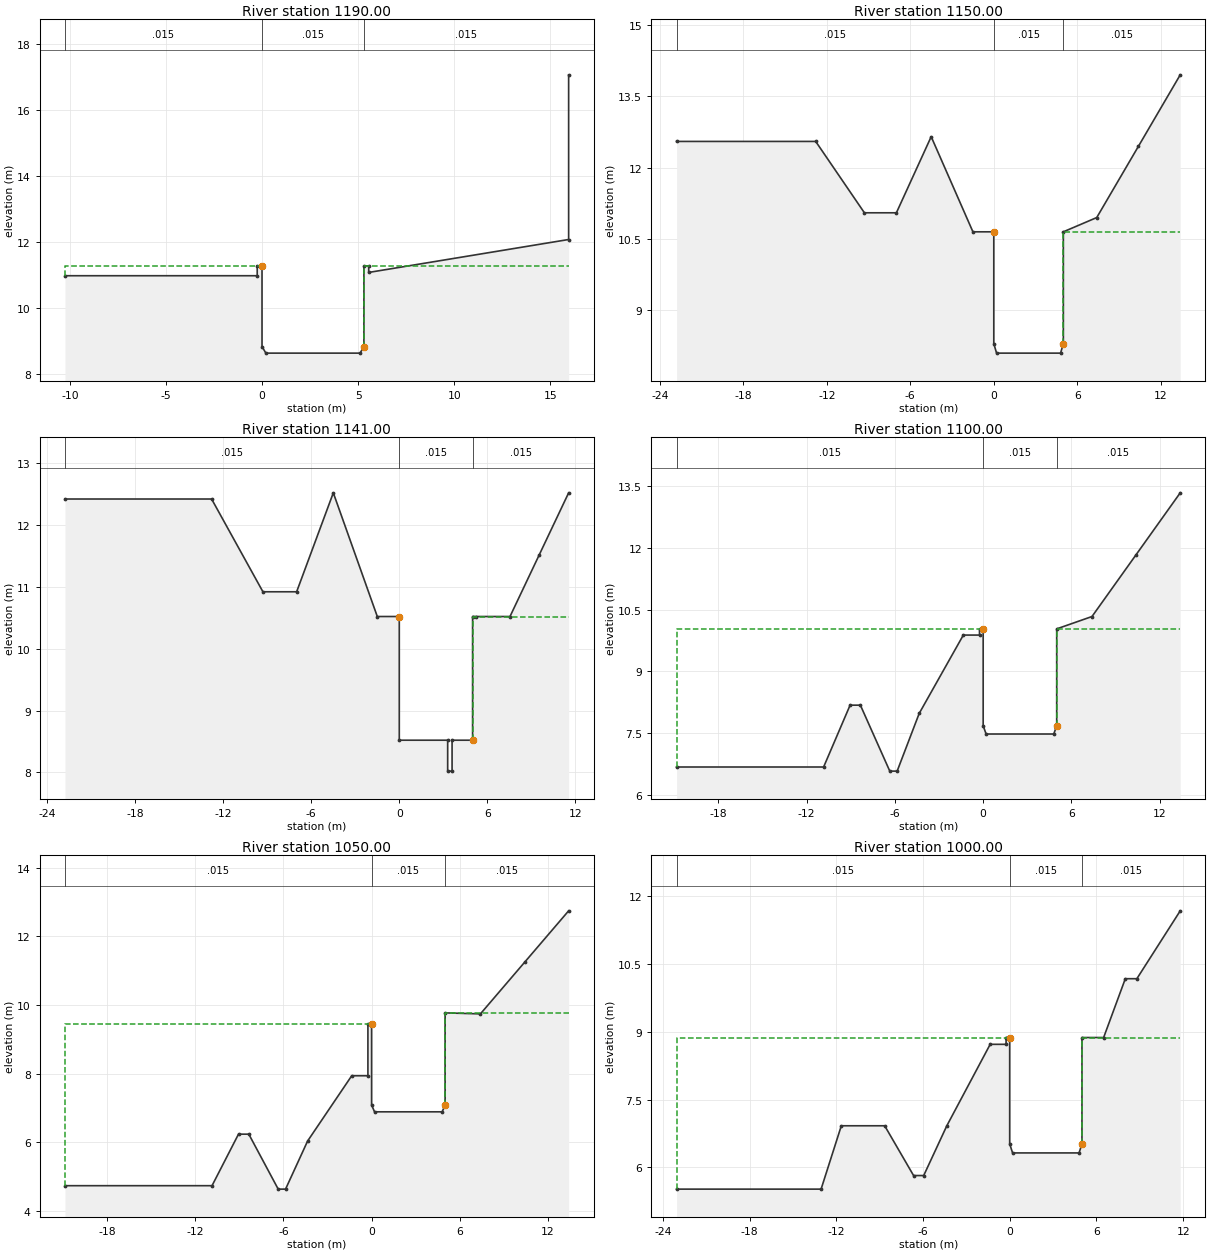
Type RM Length L Ch R = 1 ,1190.00 ,40,40,40
BEGIN DESCRIPTION:
23.040
END DESCRIPTION:
#Sta/Elev= 13
  -10.25   10.97    -.25   10.97    -.25   11.27       0   11.27       0    8.82
      .2    8.62     5.1    8.62     5.3    8.82     5.3   11.27    5.55   11.27
    5.55   11.07   15.95   12.07   15.95   17.07
#Mann= 3 , 0 , 0
  -10.25    .015       0       0    .015       0     5.3    .015       0
#XS Ineff= 2 , 0
               0   11.27     5.3           11.27
Permanent Ineff=
       F       F
Bank Sta=0,5.3
XS Rating Curve= 0
Exp/Cntr=.3,.1

Type RM Length L Ch R = 1 ,1150.00 ,9,9,9
BEGIN DESCRIPTION:
23
END DESCRIPTION:
#Sta/Elev= 15
   -22.8   12.55   -12.8   12.55    -9.3   11.05      -7   11.05    -4.5   12.65
    -1.5   10.65       0   10.65       0     8.3      .2     8.1     4.8     8.1
       5     8.3       5   10.65     7.4   10.95    10.4   12.45    13.4   13.95
#Mann= 3 , 0 , 0
   -22.8    .015       0       0    .015       0       5    .015       0
#XS Ineff= 2 , 0
               0   10.65       5           10.65
Permanent Ineff=
       F       F
Bank Sta=0,5
XS Rating Curve= 0
Exp/Cntr=.3,.1

Type RM Length L Ch R = 1 ,1141.00 ,41,41,41
BEGIN DESCRIPTION:
22.041
END DESCRIPTION:
#Sta/Elev= 18
   -22.8   12.42   -12.8   12.42    -9.3   10.92      -7   10.92    -4.5   12.52
    -1.5   10.52       0   10.52       0    8.52     3.3    8.52     3.3    8.02
     3.6    8.02     3.6    8.52       5    8.52       5   10.52    5.25   10.52
    7.55   10.52    9.55   11.52   11.55   12.52
#Mann= 3 , 0 , 0
   -22.8    .015       0       0    .015       0       5    .015       0
#XS Ineff= 2 , 0
               0   10.52       5           10.52
Permanent Ineff=
       F       F
Bank Sta=0,5
XS Rating Curve= 0
Exp/Cntr=.3,.1

Type RM Length L Ch R = 1 ,1100.00 ,50,50,50
BEGIN DESCRIPTION:
22
END DESCRIPTION:
#Sta/Elev= 19
  -20.85    6.68  -10.85    6.68   -9.05    8.18   -8.35    8.18   -6.35    6.58
   -5.85    6.58   -4.35    7.98   -1.35    9.88    -.25    9.88    -.25   10.03
       0   10.03       0    7.68      .2    7.48     4.8    7.48       5    7.68
       5   10.03     7.4   10.33    10.4   11.83    13.4   13.33
#Mann= 3 , 0 , 0
  -20.85    .015       0       0    .015       0       5    .015       0
#XS Ineff= 2 , 0
               0   10.03       5           10.03
Permanent Ineff=
       F       F
Bank Sta=0,5
XS Rating Curve= 0
Exp/Cntr=.3,.1

Type RM Length L Ch R = 1 ,1050.00 ,50,50,50
BEGIN DESCRIPTION:
21
END DESCRIPTION:
#Sta/Elev= 19
  -20.85    4.74  -10.85    4.74   -9.05    6.24   -8.35    6.24   -6.35    4.64
   -5.85    4.64   -4.35    6.04   -1.35    7.94    -.25    7.94    -.25    9.44
       0    9.44       0    7.09      .2    6.89     4.8    6.89       5    7.09
       5    9.77     7.4    9.74    10.4   11.24    13.4   12.74
#Mann= 3 , 0 , 0
  -20.85    .015       0       0    .015       0       5    .015       0
#XS Ineff= 2 , 0
               0    9.44       5            9.77
Permanent Ineff=
       F       F
Bank Sta=0,5
XS Rating Curve= 0
Exp/Cntr=.3,.1

Type RM Length L Ch R = 1 ,1000.00 ,50,50,50
BEGIN DESCRIPTION:
20
END DESCRIPTION:
#Sta/Elev= 20
  -23.05    5.52  -13.05    5.52  -11.65    6.92   -8.65    6.92   -6.65    5.82
   -5.95    5.82   -4.35    6.92   -1.35    8.72    -.25    8.72    -.25    8.87
       0    8.87       0    6.52      .2    6.32     4.8    6.32       5    6.52
       5    8.87     6.5    8.87       8   10.17     8.8   10.17    11.8   11.67
#Mann= 3 , 0 , 0
  -23.05    .015       0       0    .015       0       5    .015       0
#XS Ineff= 2 , 0
               0    8.87       5            8.87
Permanent Ineff=
       F       F
Bank Sta=0,5
XS Rating Curve= 0
Exp/Cntr=.3,.1

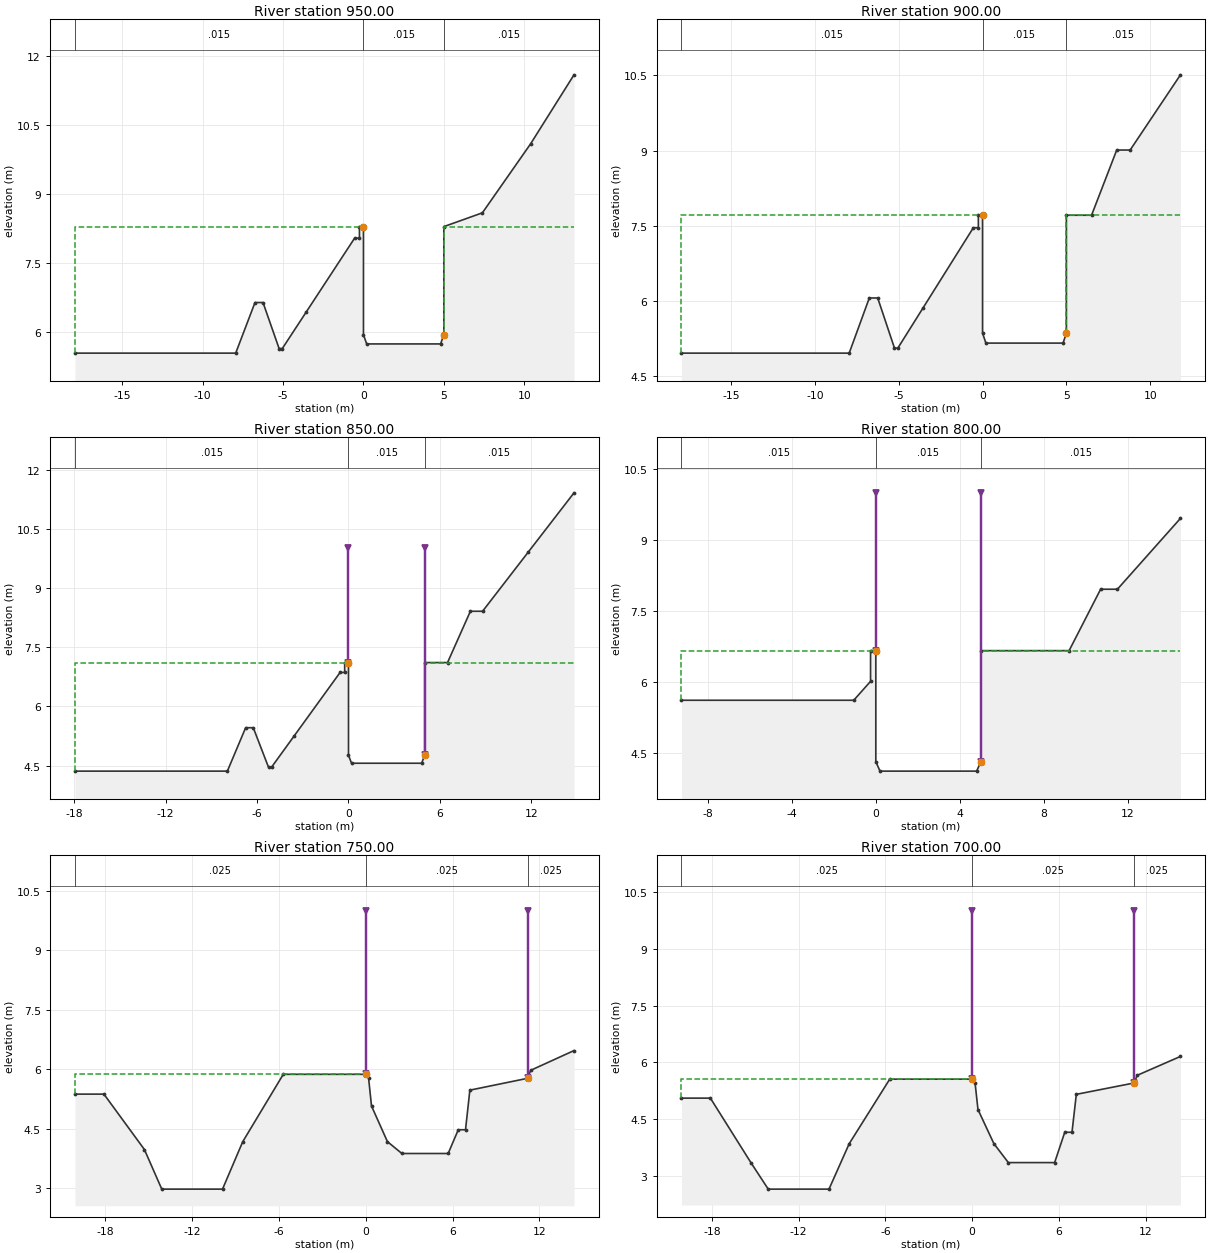
Type RM Length L Ch R = 1 ,950.00  ,50,50,50
BEGIN DESCRIPTION:
19
END DESCRIPTION:
#Sta/Elev= 19
  -17.95    5.53   -7.95    5.53   -6.75    6.63   -6.25    6.63   -5.25    5.63
   -5.05    5.63   -3.55    6.43    -.55    8.03    -.25    8.03    -.25    8.28
       0    8.28       0    5.93      .2    5.73     4.8    5.73       5    5.93
       5    8.28     7.4    8.58    10.4   10.08    13.1   11.58
#Mann= 3 , 0 , 0
  -17.95    .015       0       0    .015       0       5    .015       0
#XS Ineff= 2 , 0
               0    8.28       5            8.28
Permanent Ineff=
       F       F
Bank Sta=0,5
XS Rating Curve= 0
Exp/Cntr=.3,.1

Type RM Length L Ch R = 1 ,900.00  ,50,50,50
BEGIN DESCRIPTION:
18
END DESCRIPTION:
#Sta/Elev= 20
  -17.95    4.96   -7.95    4.96   -6.75    6.06   -6.25    6.06   -5.25    5.06
   -5.05    5.06   -3.55    5.86    -.55    7.46    -.25    7.46    -.25    7.71
       0    7.71       0    5.36      .2    5.16     4.8    5.16       5    5.36
       5    7.71     6.5    7.71       8    9.01     8.8    9.01    11.8   10.51
#Mann= 3 , 0 , 0
  -17.95    .015       0       0    .015       0       5    .015       0
#XS Ineff= 2 , 0
               0    7.71       5            7.71
Permanent Ineff=
       F       F
Bank Sta=0,5
XS Rating Curve= 0
Exp/Cntr=.3,.1

Type RM Length L Ch R = 1 ,850.00  ,50,50,50
BEGIN DESCRIPTION:
17
END DESCRIPTION:
#Sta/Elev= 21
  -17.95    4.36   -7.95    4.36   -6.75    5.46   -6.25    5.46   -5.25    4.46
   -5.05    4.46   -3.55    5.26    -.55    6.86    -.25    6.86    -.25    7.11
       0    7.11       0    4.76      .2    4.56     4.8    4.56       5    4.76
       5    7.11     6.5    7.11       8    8.41     8.8    8.41    11.8    9.91
    14.8   11.41
#Mann= 3 , 0 , 0
  -17.95    .015       0       0    .015       0       5    .015       0
Levee=-1,0,10,-1,5,10,,
#XS Ineff= 2 , 0
               0    7.11       5            7.11
Permanent Ineff=
       F       F
Bank Sta=0,5
XS Rating Curve= 0
Exp/Cntr=.3,.1

Type RM Length L Ch R = 1 ,800.00  ,50,50,50
BEGIN DESCRIPTION:
16
END DESCRIPTION:
#Sta/Elev= 14
   -9.25    5.61   -1.05    5.61    -.25    6.01    -.25    6.66       0    6.66
       0    4.31      .2    4.11     4.8    4.11       5    4.31       5    6.66
     9.2    6.66    10.7    7.96    11.5    7.96    14.5    9.46
#Mann= 3 , 0 , 0
   -9.25    .015       0       0    .015       0       5    .015       0
Levee=-1,0,10,-1,5,10,,
#XS Ineff= 2 , 0
               0    6.66       5            6.66
Permanent Ineff=
       F       F
Bank Sta=0,5
XS Rating Curve= 0
Exp/Cntr=.3,.1

Type RM Length L Ch R = 1 ,750.00  ,50,50,50
BEGIN DESCRIPTION:
15
END DESCRIPTION:
#Sta/Elev= 19
   -20.1    5.37   -18.1    5.37   -15.3    3.97   -14.1    2.97    -9.9    2.97
    -8.5    4.17    -5.7    5.87       0    5.87      .2    5.77      .4    5.07
     1.5    4.17     2.5    3.87     5.7    3.87     6.4    4.47     6.9    4.47
     7.2    5.47    11.2    5.77    11.4    5.97    14.4    6.47
#Mann= 3 , 0 , 0
   -20.1    .025       0       0    .025       0    11.2    .025       0
Levee=-1,0,10,-1,11.2,10,,
#XS Ineff= 2 , 0
               0    5.87    11.2            5.77
Permanent Ineff=
       F       F
Bank Sta=0,11.2
XS Rating Curve= 0
Exp/Cntr=.3,.1

Type RM Length L Ch R = 1 ,700.00  ,6,6,6
BEGIN DESCRIPTION:
14
END DESCRIPTION:
#Sta/Elev= 19
   -20.1    5.06   -18.1    5.06   -15.3    3.36   -14.1    2.66    -9.9    2.66
    -8.5    3.86    -5.7    5.56       0    5.56      .2    5.46      .4    4.76
     1.5    3.86     2.5    3.36     5.7    3.36     6.4    4.16     6.9    4.16
     7.2    5.16    11.2    5.46    11.4    5.66    14.4    6.16
#Mann= 3 , 0 , 0
   -20.1    .025       0       0    .025       0    11.2    .025       0
Levee=-1,0,10,-1,11.2,10,,
#XS Ineff= 2 , 0
               0    5.56    11.2            5.46
Permanent Ineff=
       F       F
Bank Sta=0,11.2
XS Rating Curve= 0
Exp/Cntr=.3,.1

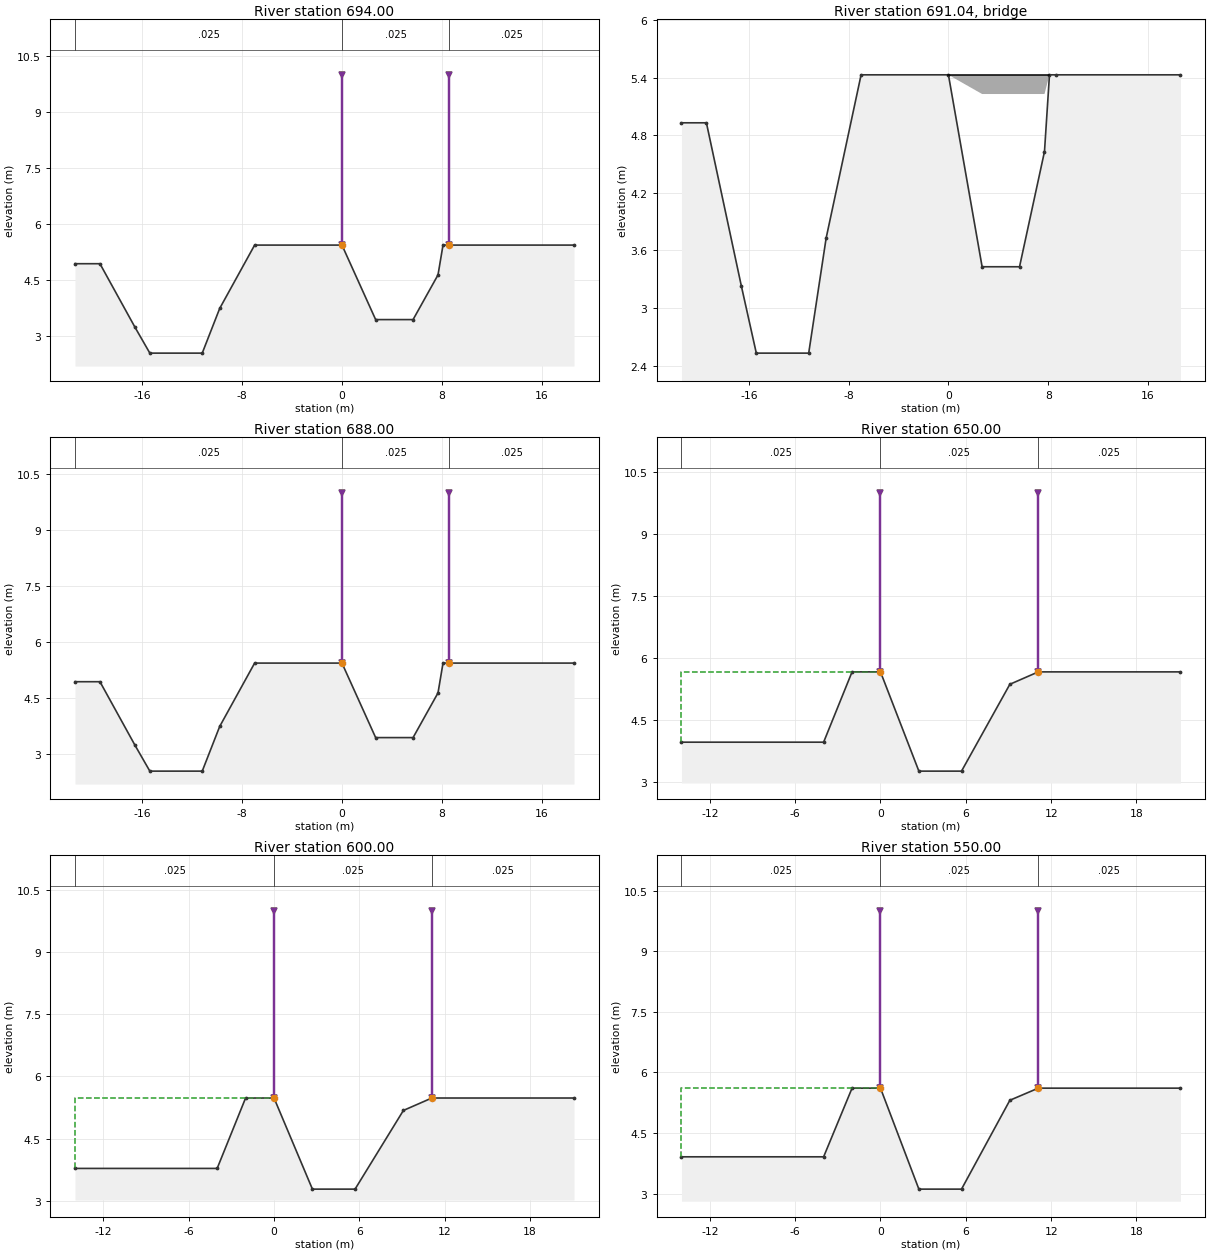
Type RM Length L Ch R = 1 ,694.00  ,6,6,6
BEGIN DESCRIPTION:
13.044
END DESCRIPTION:
#Sta/Elev= 14
   -21.4    4.93   -19.4    4.93   -16.6    3.23   -15.4    2.53   -11.2    2.53
    -9.8    3.73      -7    5.43       0    5.43     2.7    3.43     5.7    3.43
     7.7    4.63     8.1    5.43     8.6    5.43    18.6    5.43
#Mann= 3 , 0 , 0
   -21.4    .025       0       0    .025       0     8.6    .025       0
Levee=-1,0,10,-1,8.6,10,,
#XS Ineff= 2 , 0
       0       0    5.43     8.6       0    5.43
Permanent Ineff=
       F       F
Bank Sta=0,8.6
XS Rating Curve= 0
Exp/Cntr=.3,.1

Type RM Length L Ch R = 3 ,691.04  ,,,
BEGIN DESCRIPTION:
13.041
END DESCRIPTION:
Bridge Culvert--1,0,-1,-1, 0
Deck Dist Width WeirC Skew NumUp NumDn MinLoCord MaxHiCord MaxSubmerge Is_Ogee
.01,5.9,1.44,0, 2, 2, , , .95, 0, 0,0,,
       0     8.1
    5.43    5.43
    5.23    5.23
       0     8.1
    5.43    5.43
    5.23    5.23
BR Coef=-1 , 1 , 0 ,, 0 ,,,.8,-1,1.2,0,
WSPro=,,,, 1 ,,,, 0 ,,,, 0 ,,,,-1 ,-1 ,-1 , 0 , 0 , 0 , 0 , 0
BC Design=,, 0 ,, 0 ,,,,,,

Type RM Length L Ch R = 1 ,688.00  ,38,38,38
BEGIN DESCRIPTION:
13.038
END DESCRIPTION:
#Sta/Elev= 14
   -21.4    4.93   -19.4    4.93   -16.6    3.23   -15.4    2.53   -11.2    2.53
    -9.8    3.73      -7    5.43       0    5.43     2.7    3.43     5.7    3.43
     7.7    4.63     8.1    5.43     8.6    5.43    18.6    5.43
#Mann= 3 , 0 , 0
   -21.4    .025       0       0    .025       0     8.6    .025       0
Levee=-1,0,10,-1,8.6,10,,
#XS Ineff= 2 , 0
       0       0    5.43     8.6       0    5.43
Permanent Ineff=
       F       F
Bank Sta=0,8.6
XS Rating Curve= 0
Exp/Cntr=.3,.1

Type RM Length L Ch R = 1 ,650.00  ,50,50,50
BEGIN DESCRIPTION:
13
END DESCRIPTION:
#Sta/Elev= 9
     -14    3.97      -4    3.97      -2    5.67       0    5.67     2.7    3.27
     5.7    3.27     9.1    5.37    11.1    5.67    21.1    5.67
#Mann= 3 , 0 , 0
     -14    .025       0       0    .025       0    11.1    .025       0
Levee=-1,0,10,-1,11.1,10,,
#XS Ineff= 2 , 0
               0    5.67    11.1            5.67
Permanent Ineff=
       F       F
Bank Sta=0,11.1
XS Rating Curve= 0
Exp/Cntr=.3,.1

Type RM Length L Ch R = 1 ,600.00  ,50,50,50
BEGIN DESCRIPTION:
12
END DESCRIPTION:
#Sta/Elev= 9
     -14    3.78      -4    3.78      -2    5.48       0    5.48     2.7    3.28
     5.7    3.28     9.1    5.18    11.1    5.48    21.1    5.48
#Mann= 3 , 0 , 0
     -14    .025       0       0    .025       0    11.1    .025       0
Levee=-1,0,10,-1,11.1,10,,
#XS Ineff= 2 , 0
               0    5.48    11.1            5.48
Permanent Ineff=
       F       F
Bank Sta=0,11.1
XS Rating Curve= 0
Exp/Cntr=.3,.1

Type RM Length L Ch R = 1 ,550.00  ,50,50,50
BEGIN DESCRIPTION:
11
END DESCRIPTION:
#Sta/Elev= 9
     -14    3.91      -4    3.91      -2    5.61       0    5.61     2.7    3.11
     5.7    3.11     9.1    5.31    11.1    5.61    21.1    5.61
#Mann= 3 , 0 , 0
     -14    .025       0       0    .025       0    11.1    .025       0
Levee=-1,0,10,-1,11.1,10,,
#XS Ineff= 2 , 0
               0    5.61    11.1            5.61
Permanent Ineff=
       F       F
Bank Sta=0,11.1
XS Rating Curve= 0
Exp/Cntr=.3,.1

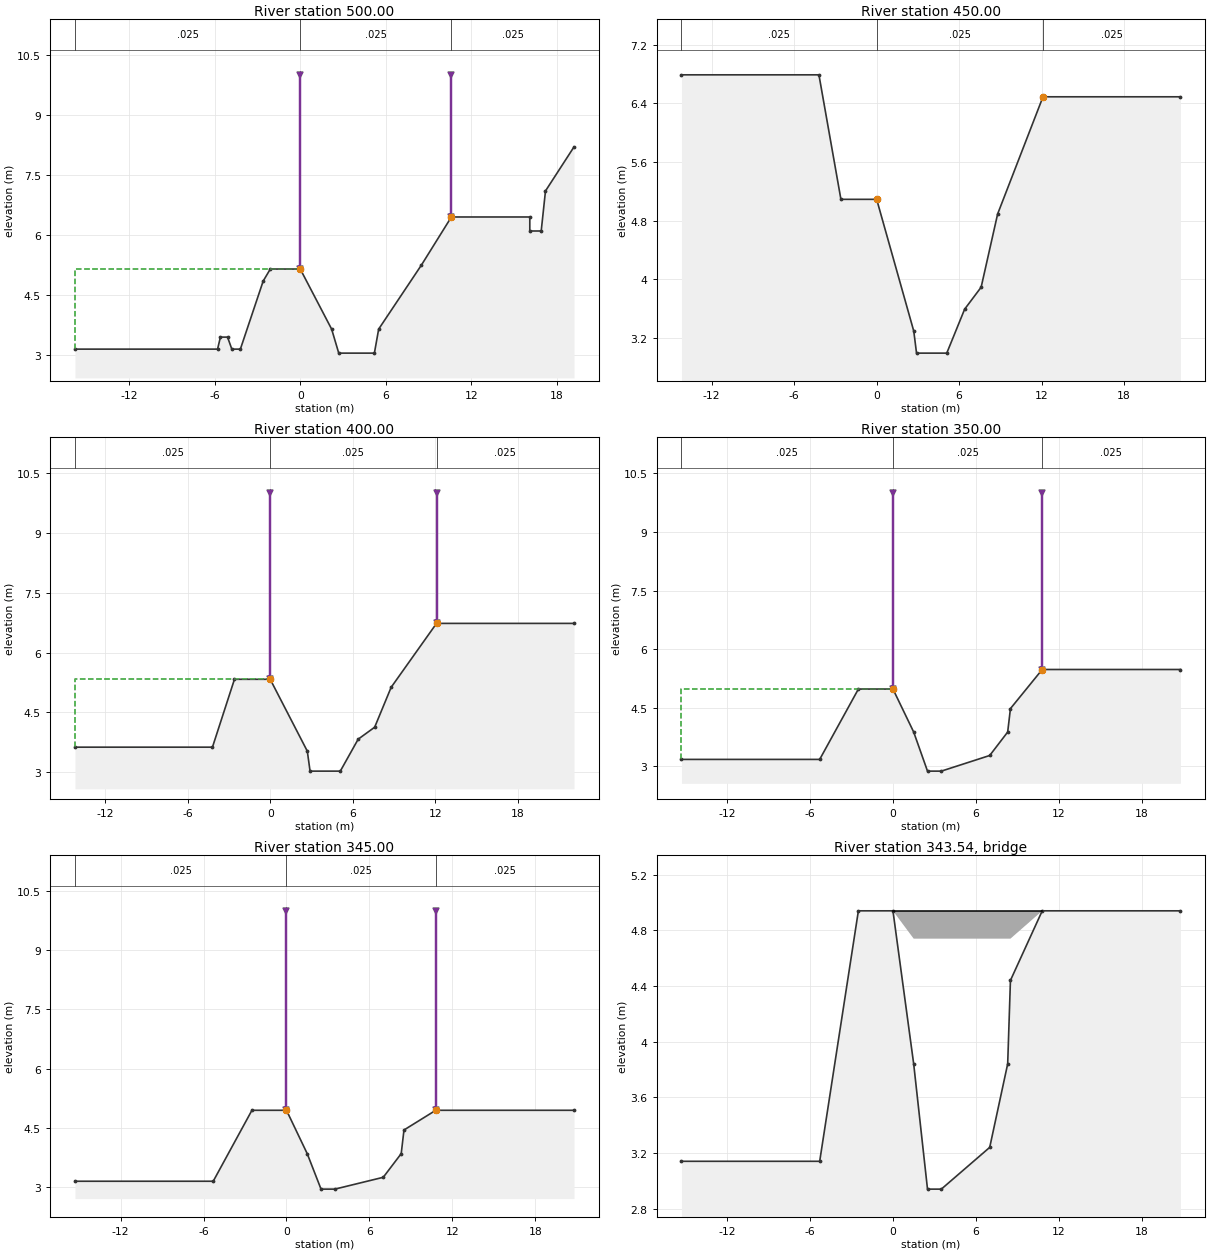
Type RM Length L Ch R = 1 ,500.00  ,50,50,50
BEGIN DESCRIPTION:
10
END DESCRIPTION:
#Sta/Elev= 20
   -15.8    3.15    -5.8    3.15    -5.6    3.45    -5.1    3.45    -4.8    3.15
    -4.2    3.15    -2.6    4.85    -2.1    5.15       0    5.15     2.2    3.65
     2.7    3.05     5.2    3.05     5.5    3.65     8.5    5.25    10.6    6.45
    16.1    6.45    16.1     6.1    16.9     6.1    17.2     7.1    19.2     8.2
#Mann= 3 , 0 , 0
   -15.8    .025       0       0    .025       0    10.6    .025       0
Levee=-1,0,10,-1,10.6,10,,
#XS Ineff= 2 , 0
               0    5.15    10.6            6.45
Permanent Ineff=
       F       F
Bank Sta=0,10.6
XS Rating Curve= 0
Exp/Cntr=.3,.1

Type RM Length L Ch R = 1 ,450.00  ,50,50,50
BEGIN DESCRIPTION:
9
END DESCRIPTION:
#Sta/Elev= 12
   -14.2    6.79    -4.2    6.79    -2.6    5.09       0    5.09     2.7    3.29
     2.9    2.99     5.1    2.99     6.4    3.59     7.6    3.89     8.8    4.89
    12.1    6.49    22.1    6.49
#Mann= 3 , 0 , 0
   -14.2    .025       0       0    .025       0    12.1    .025       0
#XS Ineff= 2 , 0
               0    5.09    12.1            6.49
Permanent Ineff=
       F       F
Bank Sta=0,12.1
XS Rating Curve= 0
Exp/Cntr=.3,.1

Type RM Length L Ch R = 1 ,400.00  ,50,50,50
BEGIN DESCRIPTION:
8
END DESCRIPTION:
#Sta/Elev= 12
   -14.2    3.63    -4.2    3.63    -2.6    5.33       0    5.33     2.7    3.53
     2.9    3.03     5.1    3.03     6.4    3.83     7.6    4.13     8.8    5.13
    12.1    6.73    22.1    6.73
#Mann= 3 , 0 , 0
   -14.2    .025       0       0    .025       0    12.1    .025       0
Levee=-1,0,10,-1,12.1,10,,
#XS Ineff= 2 , 0
               0    5.33    12.1            6.73
Permanent Ineff=
       F       F
Bank Sta=0,12.1
XS Rating Curve= 0
Exp/Cntr=.3,.1

Type RM Length L Ch R = 1 ,350.00  ,5,5,5
BEGIN DESCRIPTION:
7
END DESCRIPTION:
#Sta/Elev= 12
   -15.3    3.18    -5.3    3.18    -2.5    4.98       0    4.98     1.5    3.88
     2.5    2.88     3.5    2.88       7    3.28     8.3    3.88     8.5    4.48
    10.8    5.48    20.8    5.48
#Mann= 3 , 0 , 0
   -15.3    .025       0       0    .025       0    10.8    .025       0
Levee=-1,0,10,-1,10.8,10,,
#XS Ineff= 2 , 0
               0    4.98    10.8            5.48
Permanent Ineff=
       F       F
Bank Sta=0,10.8
XS Rating Curve= 0
Exp/Cntr=.3,.1

Type RM Length L Ch R = 1 ,345.00  ,3,3,3
BEGIN DESCRIPTION:
6.045
END DESCRIPTION:
#Sta/Elev= 12
   -15.3    3.14    -5.3    3.14    -2.5    4.94       0    4.94     1.5    3.84
     2.5    2.94     3.5    2.94       7    3.24     8.3    3.84     8.5    4.44
    10.8    4.94    20.8    4.94
#Mann= 3 , 0 , 0
   -15.3    .025       0       0    .025       0    10.8    .025       0
Levee=-1,0,10,-1,10.8,10,,
#XS Ineff= 2 , 0
       0       0    4.94    10.8       0    4.94
Permanent Ineff=
       F       F
Bank Sta=0,10.8
XS Rating Curve= 0
Exp/Cntr=.3,.1

Type RM Length L Ch R = 3 ,343.54  ,,,
BEGIN DESCRIPTION:
6.0435
END DESCRIPTION:
Bridge Culvert--1,0,-1,-1, 0
Deck Dist Width WeirC Skew NumUp NumDn MinLoCord MaxHiCord MaxSubmerge Is_Ogee
.01,2.9,1.44,0, 2, 2, , , .95, 0, 0,0,,
       0    10.8
    4.94    4.94
    4.74    4.74
       0    10.8
    4.94    4.94
    4.74    4.74
BR Coef=-1 , 1 , 0 ,, 0 ,,,.8,-1,1.2,0,
WSPro=,,,, 1 ,,,, 0 ,,,, 0 ,,,,-1 ,-1 ,-1 , 0 , 0 , 0 , 0 , 0
BC Design=,, 0 ,, 0 ,,,,,,

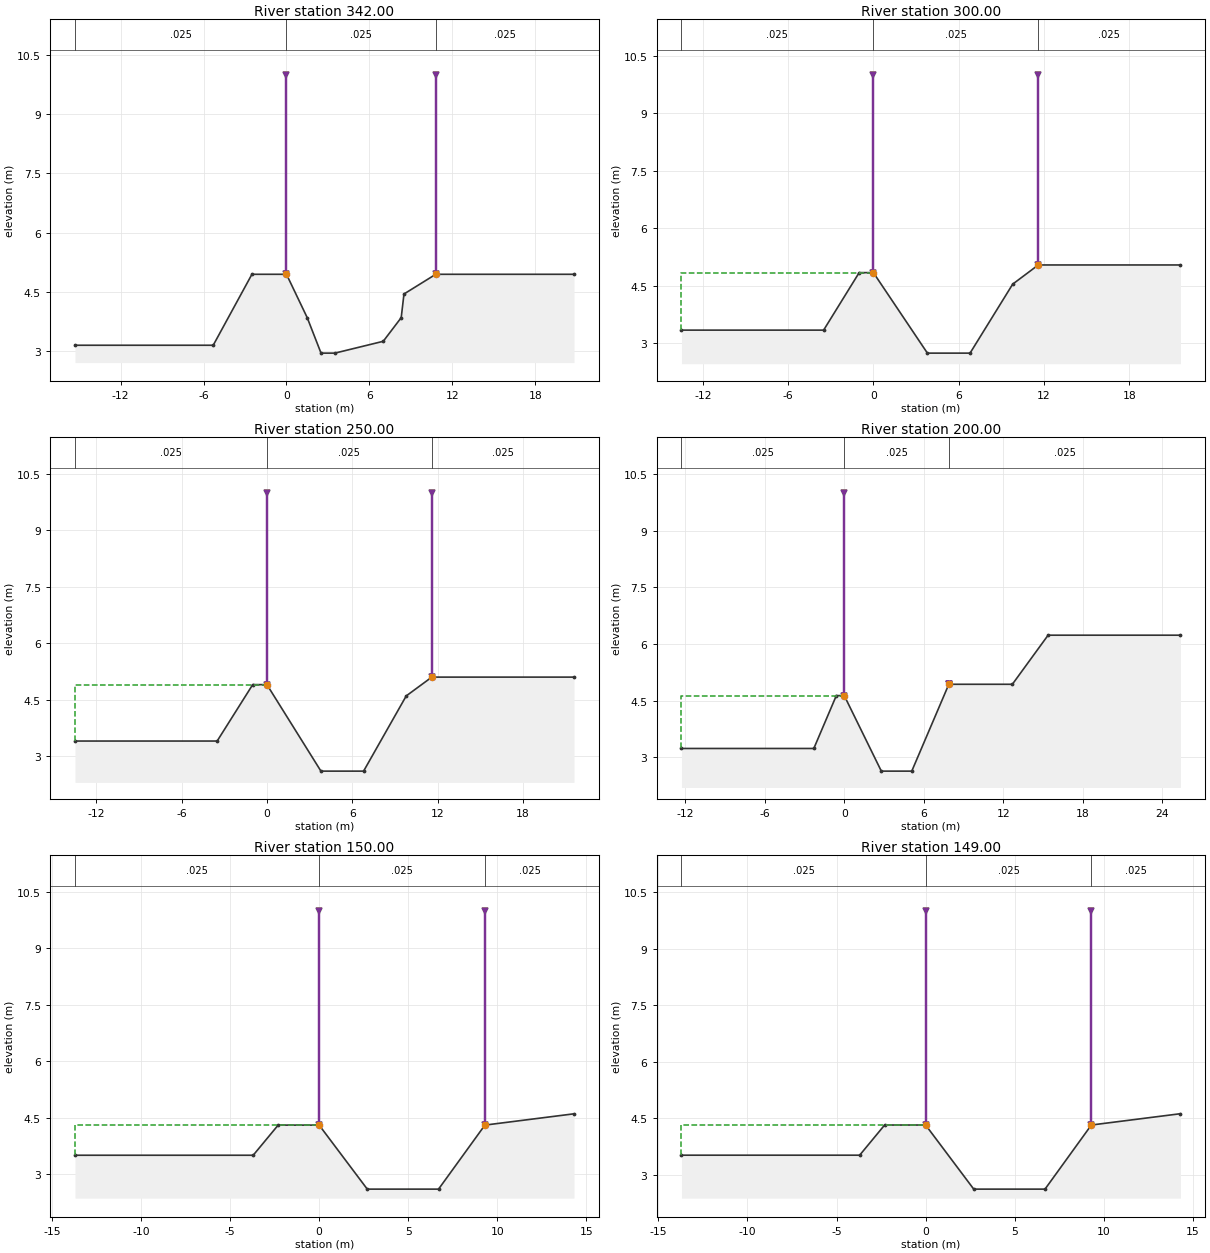
Type RM Length L Ch R = 1 ,342.00  ,42,42,42
BEGIN DESCRIPTION:
6.042
END DESCRIPTION:
#Sta/Elev= 12
   -15.3    3.14    -5.3    3.14    -2.5    4.94       0    4.94     1.5    3.84
     2.5    2.94     3.5    2.94       7    3.24     8.3    3.84     8.5    4.44
    10.8    4.94    20.8    4.94
#Mann= 3 , 0 , 0
   -15.3    .025       0       0    .025       0    10.8    .025       0
Levee=-1,0,10,-1,10.8,10,,
#XS Ineff= 2 , 0
       0       0    4.94    10.8       0    4.94
Permanent Ineff=
       F       F
Bank Sta=0,10.8
XS Rating Curve= 0
Exp/Cntr=.3,.1

Type RM Length L Ch R = 1 ,300.00  ,50,50,50
BEGIN DESCRIPTION:
6
END DESCRIPTION:
#Sta/Elev= 9
   -13.5    3.34    -3.5    3.34      -1    4.84       0    4.84     3.8    2.74
     6.8    2.74     9.8    4.54    11.6    5.04    21.6    5.04
#Mann= 3 , 0 , 0
   -13.5    .025       0       0    .025       0    11.6    .025       0
Levee=-1,0,10,-1,11.6,10,,
#XS Ineff= 2 , 0
               0    4.84    11.6            5.04
Permanent Ineff=
       F       F
Bank Sta=0,11.6
XS Rating Curve= 0
Exp/Cntr=.3,.1

Type RM Length L Ch R = 1 ,250.00  ,50,50,50
BEGIN DESCRIPTION:
5
END DESCRIPTION:
#Sta/Elev= 9
   -13.5     3.4    -3.5     3.4      -1     4.9       0     4.9     3.8     2.6
     6.8     2.6     9.8     4.6    11.6     5.1    21.6     5.1
#Mann= 3 , 0 , 0
   -13.5    .025       0       0    .025       0    11.6    .025       0
Levee=-1,0,10,-1,11.6,10,,
#XS Ineff= 2 , 0
               0     4.9    11.6             5.1
Permanent Ineff=
       F       F
Bank Sta=0,11.6
XS Rating Curve= 0
Exp/Cntr=.3,.1

Type RM Length L Ch R = 1 ,200.00  ,50,50,50
BEGIN DESCRIPTION:
4
END DESCRIPTION:
#Sta/Elev= 10
   -12.3    3.23    -2.3    3.23     -.6    4.63       0    4.63     2.8    2.63
     5.1    2.63     7.9    4.93    12.7    4.93    15.4    6.23    25.4    6.23
#Mann= 3 , 0 , 0
   -12.3    .025       0       0    .025       0     7.9    .025       0
Levee=-1,0,10,-1,7.9,4.93,,
#XS Ineff= 2 , 0
               0    4.63     7.9            4.93
Permanent Ineff=
       F       F
Bank Sta=0,7.9
XS Rating Curve= 0
Exp/Cntr=.3,.1

Type RM Length L Ch R = 1 ,150.00  ,1,1,1
BEGIN DESCRIPTION:
3
END DESCRIPTION:
#Sta/Elev= 8
   -13.7    3.51    -3.7    3.51    -2.3    4.31       0    4.31     2.7    2.61
     6.7    2.61     9.3    4.31    14.3    4.61
#Mann= 3 , 0 , 0
   -13.7    .025       0       0    .025       0     9.3    .025       0
Levee=-1,0,10,-1,9.3,10,,
#XS Ineff= 2 , 0
               0    4.31     9.3            4.31
Permanent Ineff=
       F       F
Bank Sta=0,9.3
XS Rating Curve= 0
Exp/Cntr=.3,.1

Type RM Length L Ch R = 1 ,149.00  ,3,3,3
BEGIN DESCRIPTION:
2.049
END DESCRIPTION:
#Sta/Elev= 8
   -13.7    3.52    -3.7    3.52    -2.3    4.32       0    4.32     2.7    2.62
     6.7    2.62     9.3    4.32    14.3    4.62
#Mann= 3 , 0 , 0
   -13.7    .025       0       0    .025       0     9.3    .025       0
Levee=-1,0,10,-1,9.3,10,,
#XS Ineff= 2 , 0
               0    4.32     9.3            4.32
Permanent Ineff=
       F       F
Bank Sta=0,9.3
XS Rating Curve= 0
Exp/Cntr=.3,.1

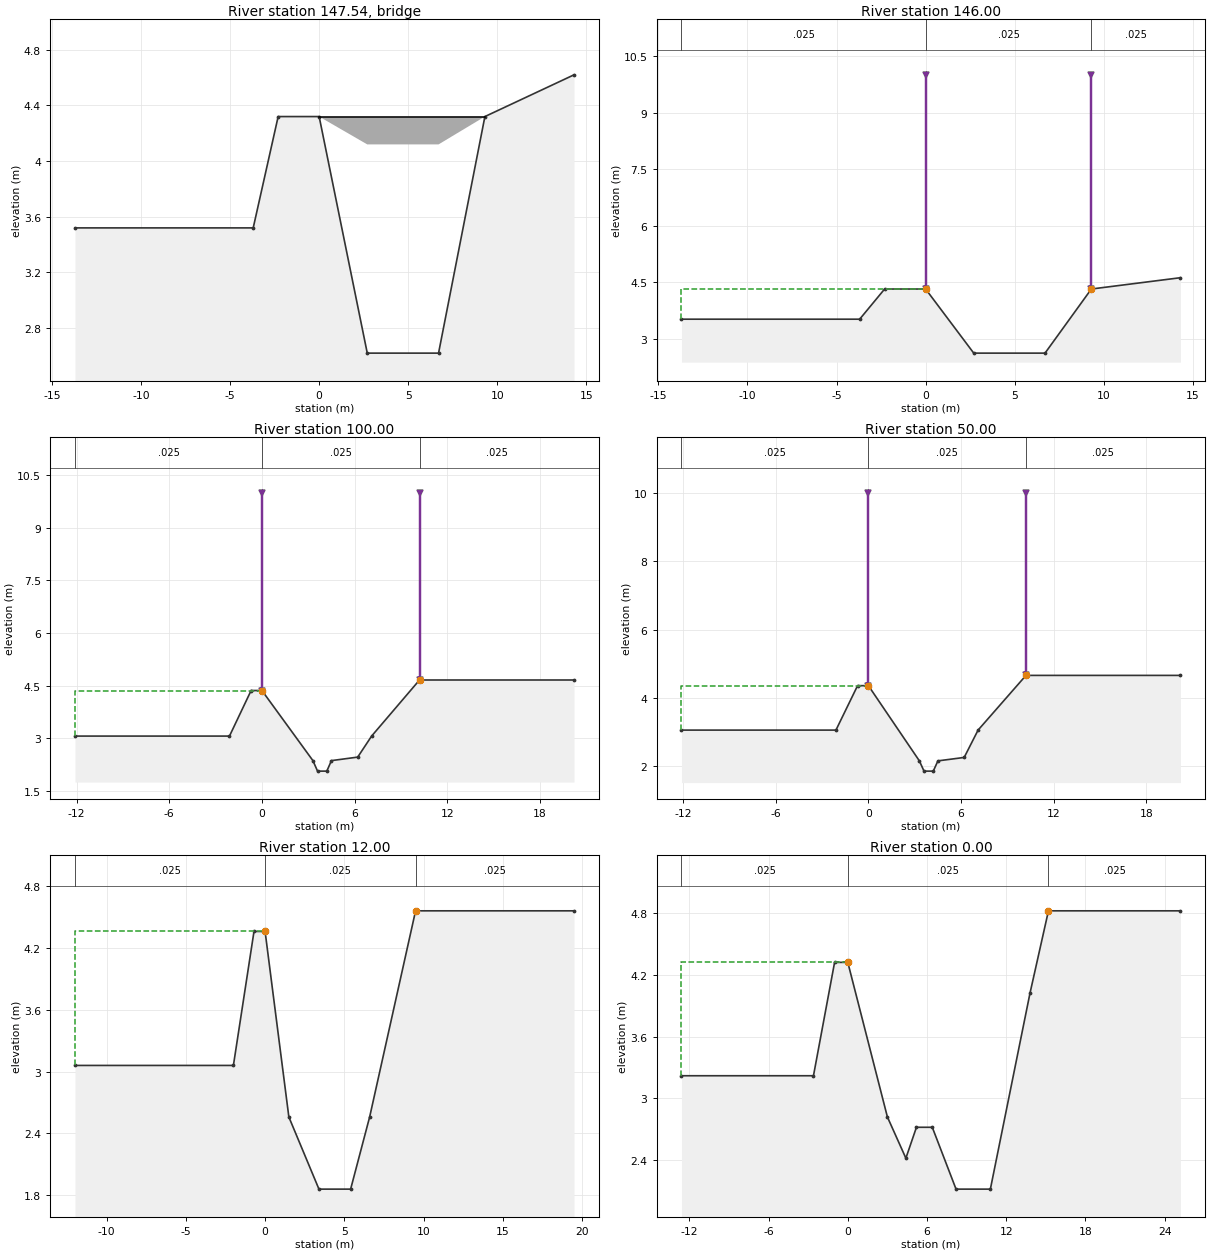
Type RM Length L Ch R = 3 ,147.54  ,,,
BEGIN DESCRIPTION:
2.0475
END DESCRIPTION:
Bridge Culvert--1,0,-1,-1, 0
Deck Dist Width WeirC Skew NumUp NumDn MinLoCord MaxHiCord MaxSubmerge Is_Ogee
.01,2.9,1.44,0, 2, 2, , , .95, 0, 0,0,,
       0     9.3
    4.32    4.32
    4.12    4.12
       0     9.3
    4.32    4.32
    4.12    4.12
BR Coef=-1 , 1 , 0 ,, 0 ,,,.8,-1,1.2,0,
WSPro=,,,, 1 ,,,, 0 ,,,, 0 ,,,,-1 ,-1 ,-1 , 0 , 0 , 0 , 0 , 0
BC Design=,, 0 ,, 0 ,,,,,,

Type RM Length L Ch R = 1 ,146.00  ,46,46,46
BEGIN DESCRIPTION:
2.046
END DESCRIPTION:
#Sta/Elev= 8
   -13.7    3.52    -3.7    3.52    -2.3    4.32       0    4.32     2.7    2.62
     6.7    2.62     9.3    4.32    14.3    4.62
#Mann= 3 , 0 , 0
   -13.7    .025       0       0    .025       0     9.3    .025       0
Levee=-1,0,10,-1,9.3,10,,
#XS Ineff= 2 , 0
               0    4.32     9.3            4.32
Permanent Ineff=
       F       F
Bank Sta=0,9.3
XS Rating Curve= 0
Exp/Cntr=.3,.1

Type RM Length L Ch R = 1 ,100.00  ,50,50,50
BEGIN DESCRIPTION:
2
END DESCRIPTION:
#Sta/Elev= 12
   -12.1    3.06    -2.1    3.06     -.7    4.36       0    4.36     3.3    2.36
     3.6    2.06     4.2    2.06     4.5    2.36     6.2    2.46     7.1    3.06
    10.2    4.66    20.2    4.66
#Mann= 3 , 0 , 0
   -12.1    .025       0       0    .025       0    10.2    .025       0
Levee=-1,0,10,-1,10.2,10,,
#XS Ineff= 2 , 0
               0    4.36    10.2            4.66
Permanent Ineff=
       F       F
Bank Sta=0,10.2
XS Rating Curve= 0
Exp/Cntr=.3,.1

Type RM Length L Ch R = 1 ,50.00   ,38,38,38
BEGIN DESCRIPTION:
1
END DESCRIPTION:
#Sta/Elev= 12
   -12.1    3.06    -2.1    3.06     -.7    4.36       0    4.36     3.3    2.16
     3.6    1.86     4.2    1.86     4.5    2.16     6.2    2.26     7.1    3.06
    10.2    4.66    20.2    4.66
#Mann= 3 , 0 , 0
   -12.1    .025       0       0    .025       0    10.2    .025       0
Levee=-1,0,10,-1,10.2,10,,
#XS Ineff= 2 , 0
               0    4.36    10.2            4.66
Permanent Ineff=
       F       F
Bank Sta=0,10.2
XS Rating Curve= 0
Exp/Cntr=.3,.1

Type RM Length L Ch R = 1 ,12.00   ,12,12,12
BEGIN DESCRIPTION:
0.012
END DESCRIPTION:
#Sta/Elev= 10
     -12    3.06      -2    3.06     -.7    4.36       0    4.36     1.5    2.56
     3.4    1.86     5.4    1.86     6.6    2.56     9.5    4.56    19.5    4.56
#Mann= 3 , 0 , 0
     -12    .025       0       0    .025       0     9.5    .025       0
#XS Ineff= 2 , 0
               0    4.36     9.5            4.56
Permanent Ineff=
       F       F
Bank Sta=0,9.5
XS Rating Curve= 0
Exp/Cntr=.3,.1

Type RM Length L Ch R = 1 ,0.00    ,0,0,0
BEGIN DESCRIPTION:
0
END DESCRIPTION:
#Sta/Elev= 13
   -12.6    3.22    -2.6    3.22      -1    4.32       0    4.32       3    2.82
     4.4    2.42     5.2    2.72     6.4    2.72     8.2    2.12    10.8    2.12
    13.8    4.02    15.2    4.82    25.2    4.82
#Mann= 3 , 0 , 0
   -12.6    .025       0       0    .025       0    15.2    .025       0
#XS Ineff= 2 , 0
               0    4.32    15.2            4.82
Permanent Ineff=
       F       F
Bank Sta=0,15.2
XS Rating Curve= 0
Exp/Cntr=.3,.1

Chan Stop Cuts=-1