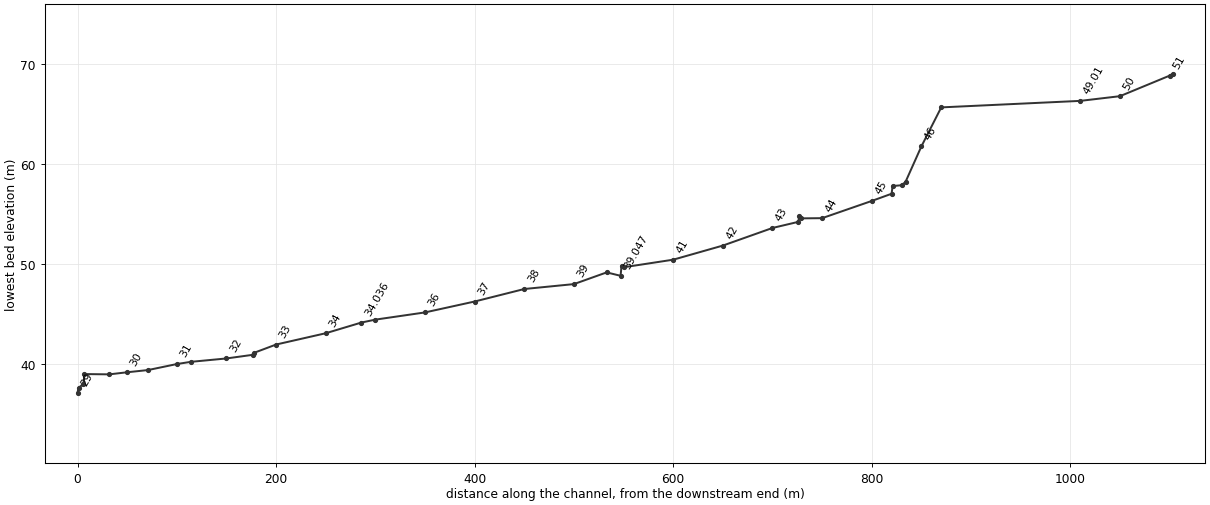
--- bbc.prj (project) ---

Proj Title=bobong-ch
Current Plan=p01
Default Exp/Contr=.3,.1
SI Units
Geom File=g01
Flow File=f01
Plan File=p01
Y Axis Title=Elevation
X Axis Title(PF)=Main Channel Distance
X Axis Title(XS)=Station
BEGIN DESCRIPTION:
           BACK WATER COMPUTATION
      APPLICATION OF HEC-2 BY Samju Construction Engineering
      bobong-ch: 10,20,30,50,80 yr
END DESCRIPTION:
DSS Export Rating Curves= 0
DSS Export Rating Curve Sorted= 0
DSS Export Volume Flow Curves= 0
DXF OffsetX= 0
DXF OffsetY= 0
DXF ScaleX= 1
DXF ScaleY= 10

--- bbc.p01 (plan) ---

Plan Title=Imported Plan 01
Version=Version 3.0.1  Mar 2001
Short Identifier=Imported Pla
Geom File=g01
Flow File=f01
Subcritical Flow
K Sum by GR= 0
Std Step Tol= 0.003
Critical Tol= 0.003
Num of Std Step Trials= 20
Max Error Tol= 0.1
Flow Tol Ratio= 0.001
Split Flow NTrial= 30
Split Flow Tol= 0.02
Split Flow Ratio= 0.02
Log Output Level= 0
Friction Slope Method= 1
Unsteady Friction Slope Method= 2
Parabolic Critical Depth
Global Vel Dist= 0 , 0 , 0
Global Log Level= 0
CheckData=True
Encroach Param=-1 ,0,0, 0
Computation Interval=1HOUR
Output Interval=1HOUR
Run HTab= 0
Run UNet= 0
Run PostProcess= 0
UNET Theta= 1
UNET ZTol= 0.02
UNET ZSATol= 0.1
UNET MxIter= 20
UNET MaxInSteps= 20
UNET DtIC= 0
UNET DtMin= 0
UNET MaxCRTS= 20
UNET WFStab= 2
UNET SFStab= 1
UNET WFX= 1
UNET SFX= 1
UNET Convert EG Bridges=-1
UNET Use Existing IB Tables=-1
Instantaneous Interval=1HOUR
Write IC File= 0
Write Velocity= 0
Write Detailed= 0

--- bbc.f01 (steady flow) ---

Flow Title=Imported Flow 01
Version=Version 3.0.1  Mar 2001
Number of Profiles= 5
Profile Names=10yr,20yr,30y,50yr,80yr
River Rch & RM=RIVER-1,Reach-1         ,51.003
   25.18   27.74   29.24   31.13   32.87
River Rch & RM=RIVER-1,Reach-1         ,26
   37.23   41.04   43.27   46.08   48.66
Boundary for River Rch & Prof#=RIVER-1,Reach-1         , 1
Up Type= 0
Dn Type= 3
Dn Slope=.02
Boundary for River Rch & Prof#=RIVER-1,Reach-1         , 2
Up Type= 0
Dn Type= 3
Dn Slope=.02
Boundary for River Rch & Prof#=RIVER-1,Reach-1         , 3
Up Type= 0
Dn Type= 3
Dn Slope=.02
Boundary for River Rch & Prof#=RIVER-1,Reach-1         , 4
Up Type= 0
Dn Type= 3
Dn Slope=.02
Boundary for River Rch & Prof#=RIVER-1,Reach-1         , 5
Up Type= 0
Dn Type= 3
Dn Slope=.02
DSS Import GetInterval= 0
DSS Import GetPeak= 0
DSS Import FillOption= 0

--- bbc.g01 (geometry) ---

Geom Title=Imported Geom 01
Version=Version 3.0.1  Mar 2001

River Reach=RIVER-1         ,Reach-1
Reach XY= 2
              .5             .95              .5             .05

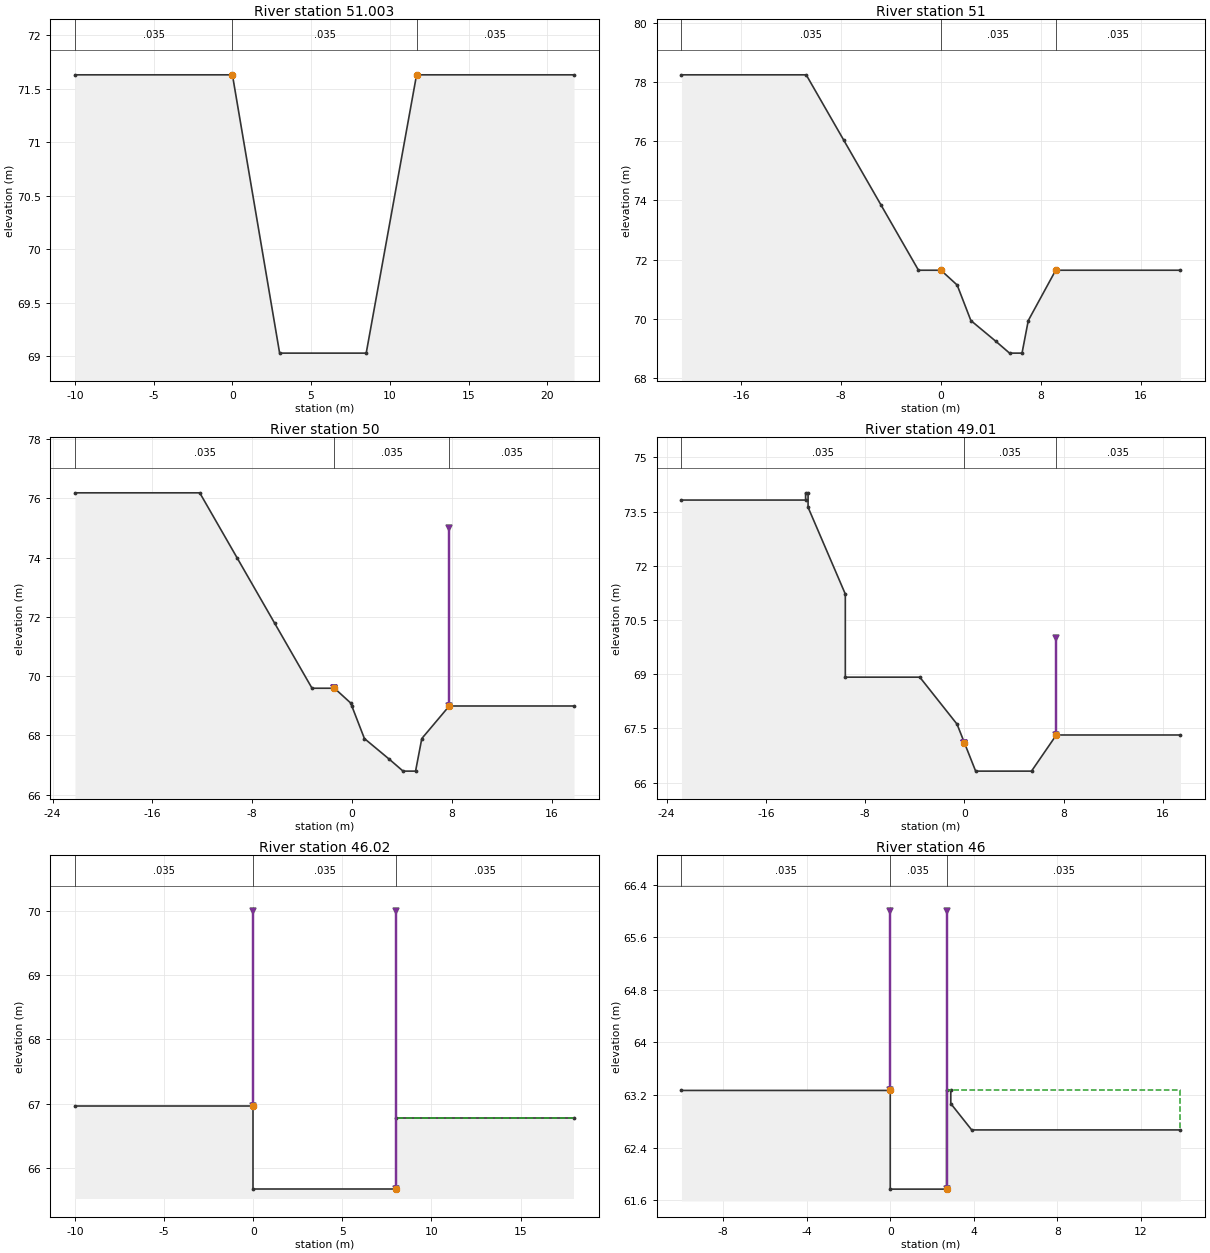
Type RM Length L Ch R = 1 ,51.003  ,3,3,3
#Sta/Elev= 6
     -10   71.63       0   71.63       3   69.03     8.5   69.03    11.7   71.63
    21.7   71.63
#Mann= 3 , 0 , 0
     -10    .035       0       0    .035       0    11.7    .035       0
#XS Ineff= 2 , 0
               0   71.63    11.7           71.63
Permanent Ineff=
       F       F
Bank Sta=0,11.7
XS Rating Curve= 0
Exp/Cntr=.3,.1

Type RM Length L Ch R = 1 ,51      ,50,50,50
#Sta/Elev= 14
   -20.8   78.24   -10.8   78.24    -7.8   76.04    -4.8   73.84    -1.8   71.64
       0   71.64     1.3   71.14     2.4   69.94     4.4   69.24     5.5   68.84
     6.5   68.84       7   69.94     9.2   71.64    19.2   71.64
#Mann= 3 , 0 , 0
   -20.8    .035       0       0    .035       0     9.2    .035       0
#XS Ineff= 2 , 0
               0   71.64     9.2           71.64
Permanent Ineff=
       F       F
Bank Sta=0,9.2
XS Rating Curve= 0
Exp/Cntr=.3,.1

Type RM Length L Ch R = 1 ,50      ,40,40,40
#Sta/Elev= 15
   -22.2   76.19   -12.2   76.19    -9.2   73.99    -6.2   71.79    -3.2   69.59
    -1.4   69.59     -.1   69.09       0   68.98       1   67.89       3   67.19
     4.1   66.79     5.1   66.79     5.6   67.89     7.8   68.99    17.8   68.99
#Mann= 3 , 0 , 0
   -22.2    .035       0    -1.4    .035       0     7.8    .035       0
Levee=-1,-1.4,69.59,-1,7.8,75,,
#XS Ineff= 2 , 0
            -1.4   69.59     7.8           68.99
Permanent Ineff=
       F       F
Bank Sta=-1.4,7.8
XS Rating Curve= 0
Exp/Cntr=.3,.1

Type RM Length L Ch R = 1 ,49.01   ,140,140,140
#Sta/Elev= 14
   -22.8   73.82   -12.8   73.82   -12.8   74.02   -12.6   74.02   -12.6   73.62
    -9.6   71.22    -9.6   68.92    -3.6   68.92     -.6   67.62       0    67.1
      .9   66.32     5.4   66.32     7.4   67.32    17.4   67.32
#Mann= 3 , 0 , 0
   -22.8    .035       0       0    .035       0     7.4    .035       0
Levee=-1,0,67.1,-1,7.4,70,,
#XS Ineff= 2 , 0
               0    67.1     7.4           67.32
Permanent Ineff=
       F       F
Bank Sta=0,7.4
XS Rating Curve= 0
Exp/Cntr=.3,.1

Type RM Length L Ch R = 1 ,46.02   ,20,20,20
#Sta/Elev= 6
     -10   66.97       0   66.97       0   65.67       8   65.67       8   66.77
      18   66.77
#Mann= 3 , 0 , 0
     -10    .035       0       0    .035       0       8    .035       0
Levee=-1,0,70,-1,8,70,,
#XS Ineff= 2 , 0
               0   66.97       8           66.77
Permanent Ineff=
       F       F
Bank Sta=0,8
XS Rating Curve= 0
Exp/Cntr=.3,.1

Type RM Length L Ch R = 1 ,46      ,16,16,16
#Sta/Elev= 9
     -10   63.27       0   63.27       0   61.77     2.7   61.77     2.7   63.27
     2.9   63.27     2.9   63.07     3.9   62.67    13.9   62.67
#Mann= 3 , 0 , 0
     -10    .035       0       0    .035       0     2.7    .035       0
Levee=-1,0,66,-1,2.7,66,,
#XS Ineff= 2 , 0
               0   63.27     2.7           63.27
Permanent Ineff=
       F       F
Bank Sta=0,2.7
XS Rating Curve= 0
Exp/Cntr=.3,.1

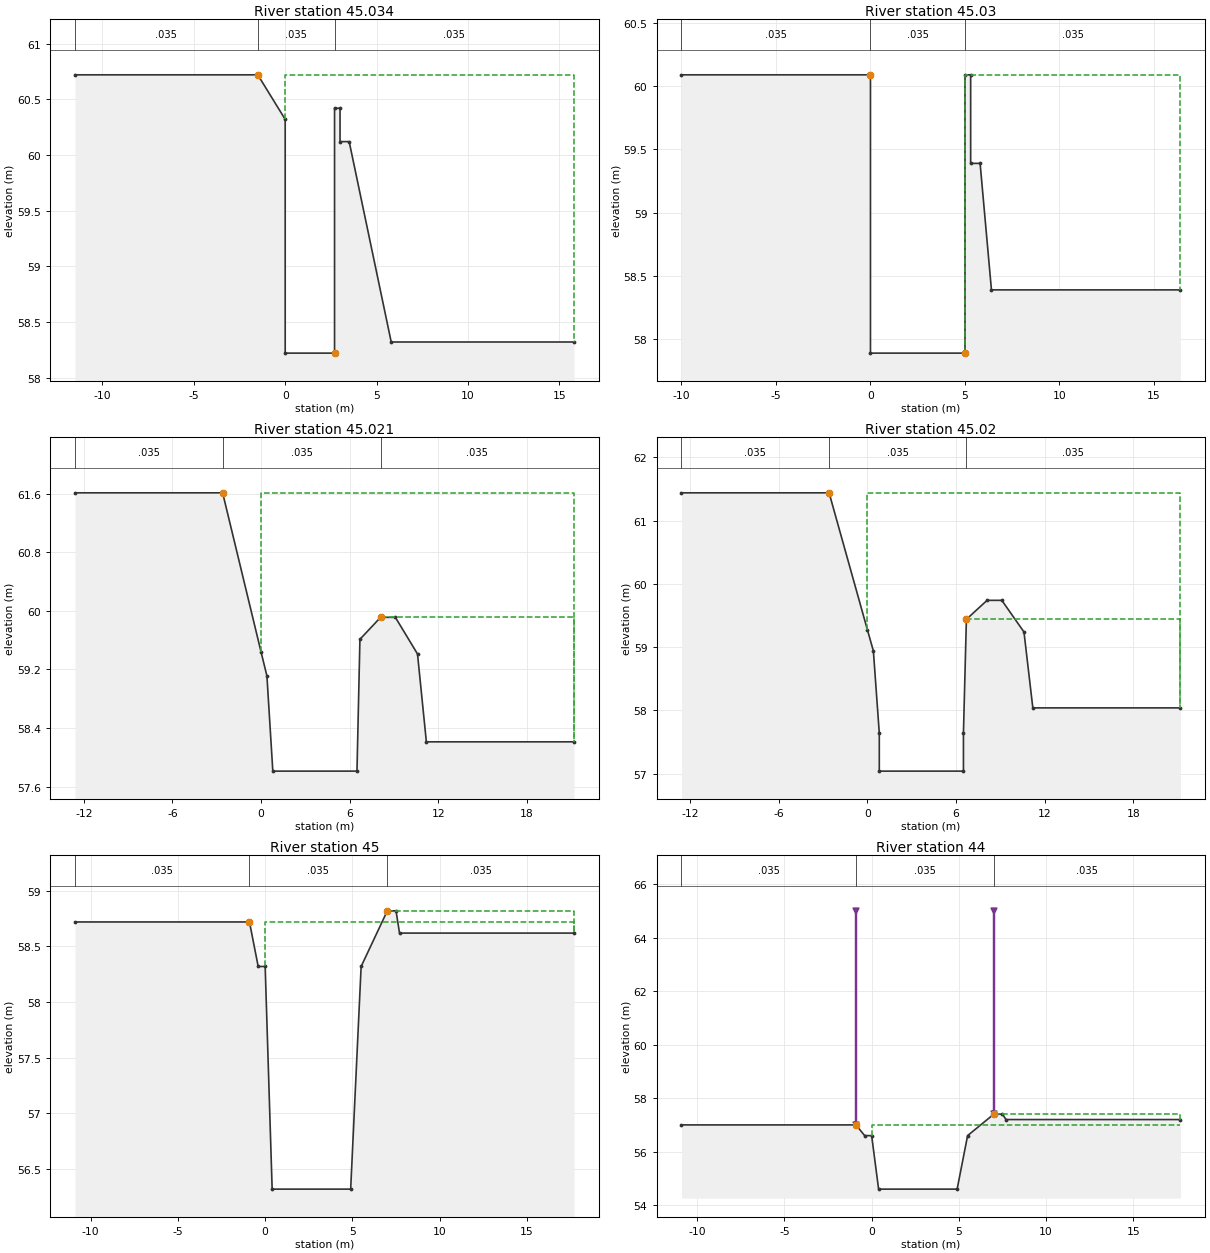
Type RM Length L Ch R = 1 ,45.034  ,4,4,4
#Sta/Elev= 11
   -11.5   60.72    -1.5   60.72       0   60.32       0   58.22     2.7   58.22
     2.7   60.42       3   60.42       3   60.12     3.5   60.12     5.8   58.32
    15.8   58.32
#Mann= 3 , 0 , 0
   -11.5    .035       0    -1.5    .035       0     2.7    .035       0
#XS Ineff= 2 , 0
       0    -1.5   60.72     2.7       0   58.22
Permanent Ineff=
       F       F
Bank Sta=-1.5,2.7
XS Rating Curve= 0
Exp/Cntr=.3,.1

Type RM Length L Ch R = 1 ,45.03   ,9,9,9
#Sta/Elev= 10
     -10   60.09       0   60.09       0   57.89       5   57.89       5   60.09
     5.3   60.09     5.3   59.39     5.8   59.39     6.4   58.39    16.4   58.39
#Mann= 3 , 0 , 0
     -10    .035       0       0    .035       0       5    .035       0
#XS Ineff= 2 , 0
               0   60.09       5           60.09
Permanent Ineff=
       F       F
Bank Sta=0,5
XS Rating Curve= 0
Exp/Cntr=.3,.1

Type RM Length L Ch R = 1 ,45.021  ,1,1,1
#Sta/Elev= 12
   -12.6   61.61    -2.6   61.61       0   59.44      .4   59.11      .8   57.81
     6.5   57.81     6.7   59.61     8.1   59.91     9.1   59.91    10.6   59.41
    11.2   58.21    21.2   58.21
#Mann= 3 , 0 , 0
   -12.6    .035       0    -2.6    .035       0     8.1    .035       0
#XS Ineff= 2 , 0
       0    -2.6   61.61     8.1       0   59.91
Permanent Ineff=
       F       F
Bank Sta=-2.6,8.1
XS Rating Curve= 0
Exp/Cntr=.3,.1

Type RM Length L Ch R = 1 ,45.02   ,20,20,20
#Sta/Elev= 14
   -12.6   61.44    -2.6   61.44       0   59.27      .4   58.94      .8   57.64
      .8   57.04     6.5   57.04     6.5   57.64     6.7   59.44     8.1   59.74
     9.1   59.74    10.6   59.24    11.2   58.04    21.2   58.04
#Mann= 3 , 0 , 0
   -12.6    .035       0    -2.6    .035       0     6.7    .035       0
#XS Ineff= 2 , 0
       0    -2.6   61.44     6.7       0   59.44
Permanent Ineff=
       F       F
Bank Sta=-2.6,6.7
XS Rating Curve= 0
Exp/Cntr=.3,.1

Type RM Length L Ch R = 1 ,45      ,50,50,50
#Sta/Elev= 11
   -10.9   58.72     -.9   58.72     -.4   58.32       0   58.32      .4   56.32
     4.9   56.32     5.5   58.32       7   58.82     7.5   58.82     7.7   58.62
    17.7   58.62
#Mann= 3 , 0 , 0
   -10.9    .035       0     -.9    .035       0       7    .035       0
#XS Ineff= 2 , 0
       0     -.9   58.72       7       0   58.82
Permanent Ineff=
       F       F
Bank Sta=-.9,7
XS Rating Curve= 0
Exp/Cntr=.3,.1

Type RM Length L Ch R = 1 ,44      ,21,21,21
#Sta/Elev= 11
   -10.9      57     -.9      57     -.4    56.6       0    56.6      .4    54.6
     4.9    54.6     5.5    56.6       7    57.4     7.5    57.4     7.7    57.2
    17.7    57.2
#Mann= 3 , 0 , 0
   -10.9    .035       0     -.9    .035       0       7    .035       0
Levee=-1,-.9,65,-1,7,65,,
#XS Ineff= 2 , 0
       0     -.9      57       7       0    57.4
Permanent Ineff=
       F       F
Bank Sta=-.9,7
XS Rating Curve= 0
Exp/Cntr=.3,.1

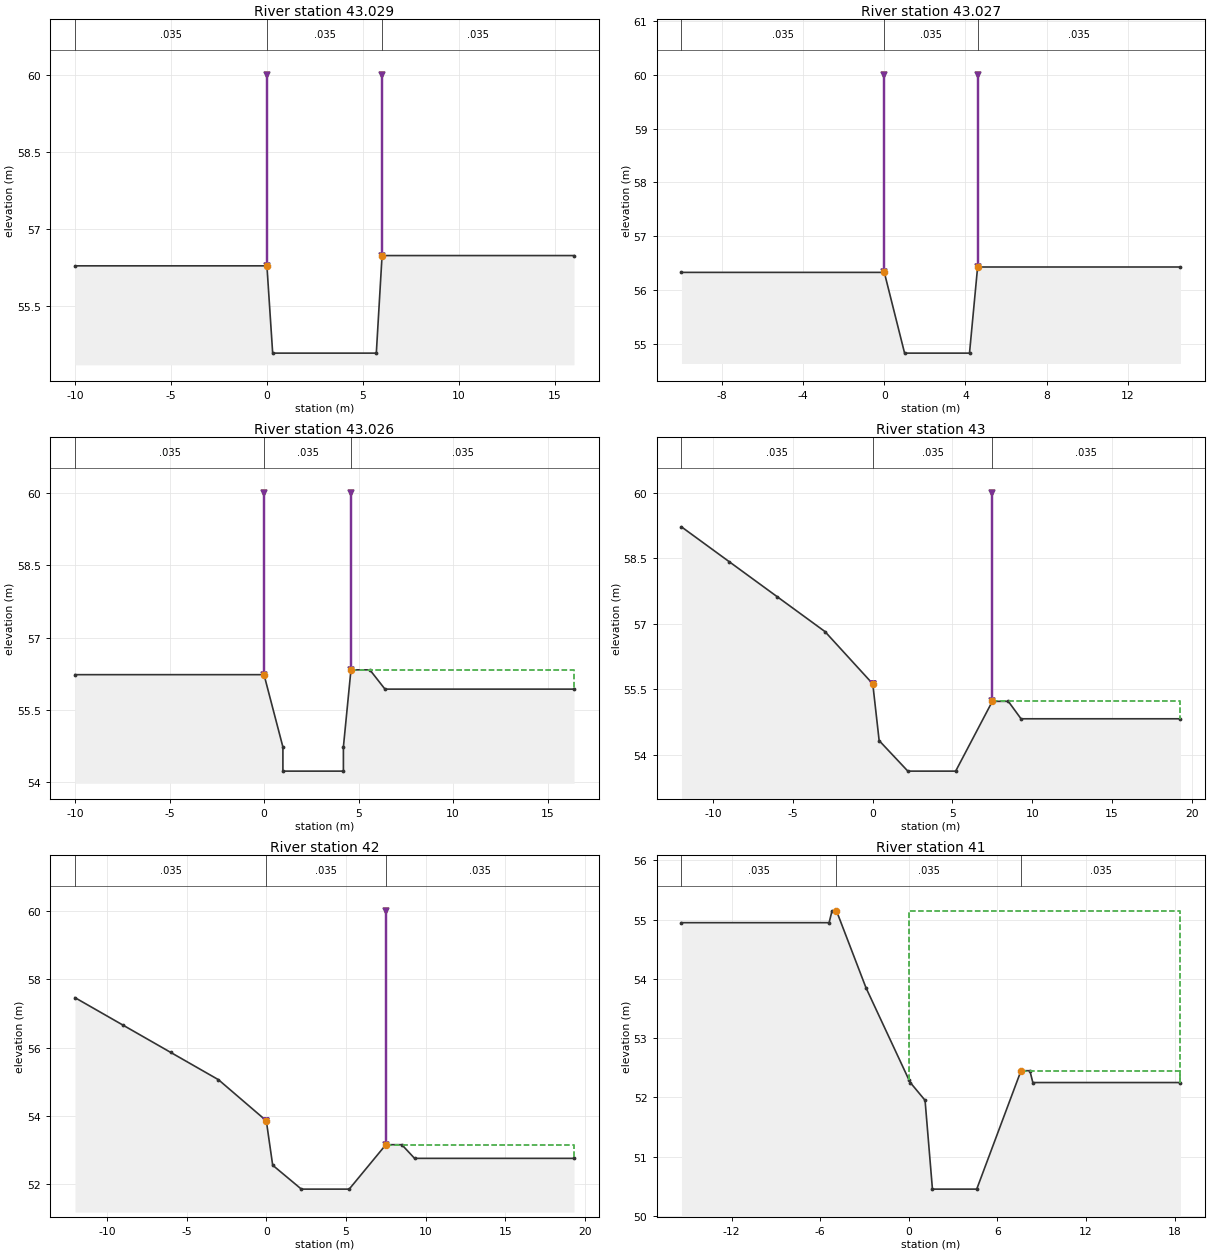
Type RM Length L Ch R = 1 ,43.029  ,2,2,2
#Sta/Elev= 6
     -10   56.28       0   56.28      .3   54.58     5.7   54.58       6   56.48
      16   56.48
#Mann= 3 , 0 , 0
     -10    .035       0       0    .035       0       6    .035       0
Levee=-1,0,60,-1,6,60,,
#XS Ineff= 2 , 0
               0   56.28       6           56.48
Permanent Ineff=
       F       F
Bank Sta=0,6
XS Rating Curve= 0
Exp/Cntr=.3,.1

Type RM Length L Ch R = 1 ,43.027  ,1,1,1
#Sta/Elev= 6
     -10   56.33       0   56.33       1   54.83     4.2   54.83     4.6   56.43
    14.6   56.43
#Mann= 3 , 0 , 0
     -10    .035       0       0    .035       0     4.6    .035       0
Levee=-1,0,60,-1,4.6,60,,
#XS Ineff= 2 , 0
               0   56.33     4.6           56.43
Permanent Ineff=
       F       F
Bank Sta=0,4.6
XS Rating Curve= 0
Exp/Cntr=.3,.1

Type RM Length L Ch R = 1 ,43.026  ,26,26,26
#Sta/Elev= 10
     -10   56.23       0   56.23       1   54.73       1   54.23     4.2   54.23
     4.2   54.73     4.6   56.33     5.6   56.33     6.4   55.93    16.4   55.93
#Mann= 3 , 0 , 0
     -10    .035       0       0    .035       0     4.6    .035       0
Levee=-1,0,60,-1,4.6,60,,
#XS Ineff= 2 , 0
               0   56.23     4.6           56.33
Permanent Ineff=
       F       F
Bank Sta=0,4.6
XS Rating Curve= 0
Exp/Cntr=.3,.1

Type RM Length L Ch R = 1 ,43      ,50,50,50
#Sta/Elev= 12
     -12   59.22      -9   58.42      -6   57.62      -3   56.82       0   55.62
      .4   54.32     2.2   53.62     5.2   53.62     7.5   55.22     8.5   55.22
     9.3   54.82    19.3   54.82
#Mann= 3 , 0 , 0
     -12    .035       0       0    .035       0     7.5    .035       0
Levee=-1,0,55.62,-1,7.5,60,,
#XS Ineff= 2 , 0
               0   55.62     7.5           55.22
Permanent Ineff=
       F       F
Bank Sta=0,7.5
XS Rating Curve= 0
Exp/Cntr=.3,.1

Type RM Length L Ch R = 1 ,42      ,50,50,50
#Sta/Elev= 12
     -12   57.46      -9   56.66      -6   55.86      -3   55.06       0   53.86
      .4   52.56     2.2   51.86     5.2   51.86     7.5   53.16     8.5   53.16
     9.3   52.76    19.3   52.76
#Mann= 3 , 0 , 0
     -12    .035       0       0    .035       0     7.5    .035       0
Levee=-1,0,53.86,-1,7.5,60,,
#XS Ineff= 2 , 0
               0   53.86     7.5           53.16
Permanent Ineff=
       F       F
Bank Sta=0,7.5
XS Rating Curve= 0
Exp/Cntr=.3,.1

Type RM Length L Ch R = 1 ,41      ,50,50,50
#Sta/Elev= 14
   -15.4   54.95    -5.4   54.95    -5.2   55.15    -4.9   55.15    -2.9   53.85
       0    52.3      .1   52.25     1.1   51.95     1.6   50.45     4.6   50.45
     7.6   52.45     8.2   52.45     8.4   52.25    18.4   52.25
#Mann= 3 , 0 , 0
   -15.4    .035       0    -4.9    .035       0     7.6    .035       0
#XS Ineff= 2 , 0
       0    -4.9   55.15     7.6       0   52.45
Permanent Ineff=
       F       F
Bank Sta=-4.9,7.6
XS Rating Curve= 0
Exp/Cntr=.3,.1

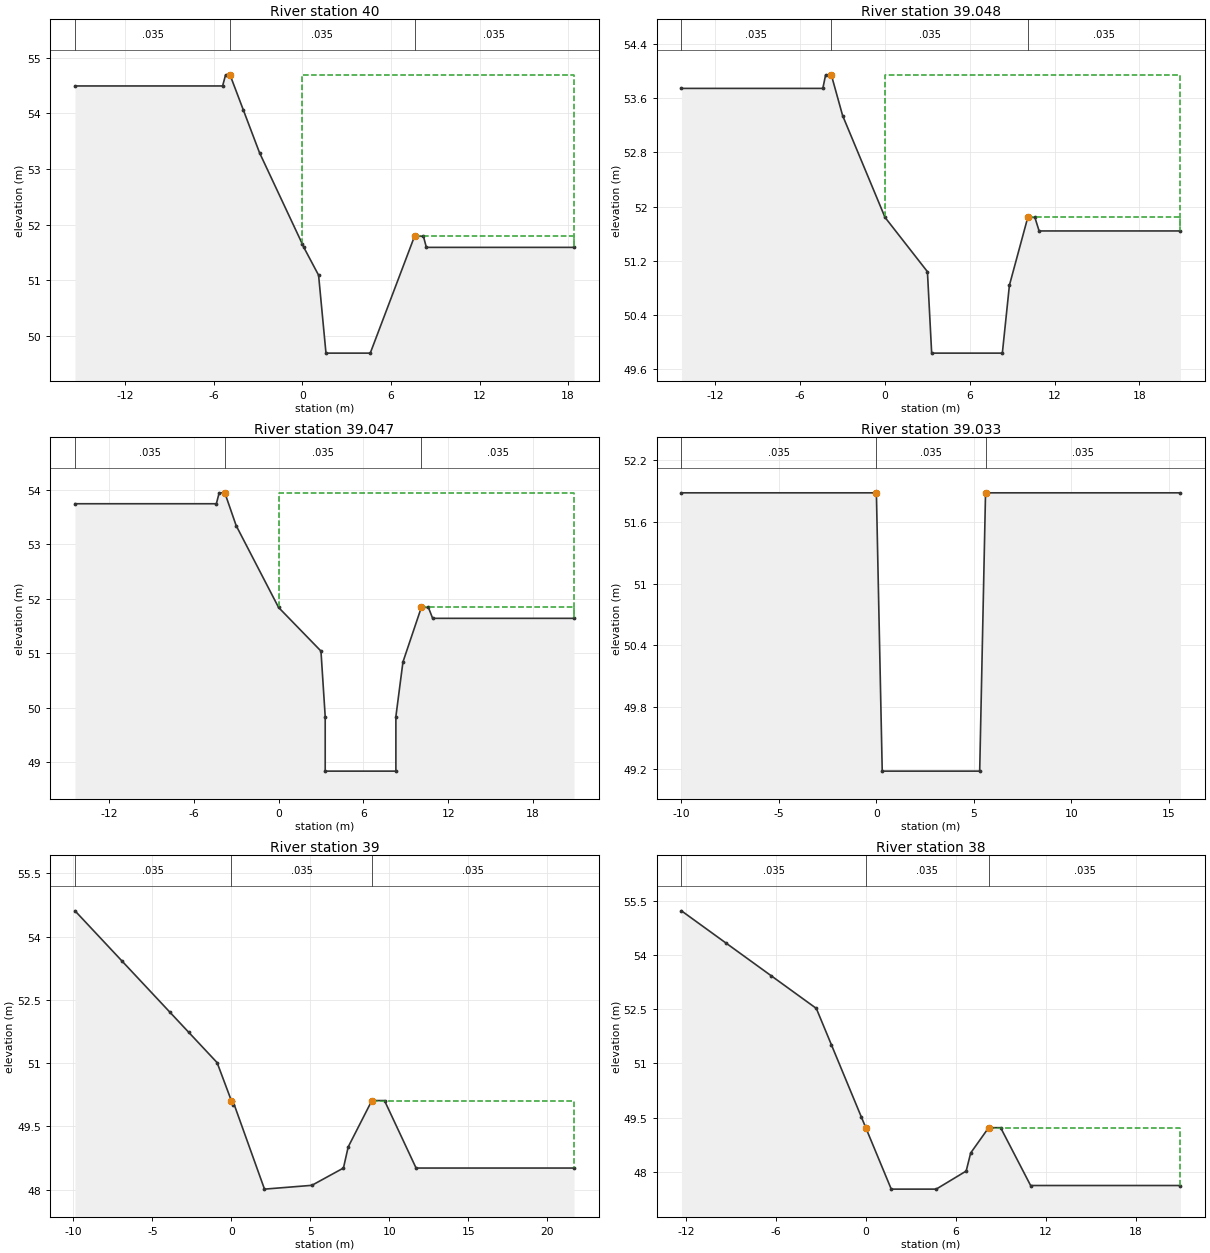
Type RM Length L Ch R = 1 ,40      ,2,2,2
#Sta/Elev= 15
   -15.4   54.49    -5.4   54.49    -5.2   54.69    -4.9   54.69      -4   54.06
    -2.9   53.29       0   51.65      .1   51.59     1.1   51.09     1.6   49.69
     4.6   49.69     7.6   51.79     8.2   51.79     8.4   51.59    18.4   51.59
#Mann= 3 , 0 , 0
   -15.4    .035       0    -4.9    .035       0     7.6    .035       0
#XS Ineff= 2 , 0
       0    -4.9   54.69     7.6       0   51.79
Permanent Ineff=
       F       F
Bank Sta=-4.9,7.6
XS Rating Curve= 0
Exp/Cntr=.3,.1

Type RM Length L Ch R = 1 ,39.048  ,1,1,1
#Sta/Elev= 14
   -14.4   53.74    -4.4   53.74    -4.2   53.94    -3.8   53.94      -3   53.34
       0   51.84       3   51.04     3.3   49.84     8.3   49.84     8.8   50.84
    10.1   51.84    10.6   51.84    10.9   51.64    20.9   51.64
#Mann= 3 , 0 , 0
   -14.4    .035       0    -3.8    .035       0    10.1    .035       0
#XS Ineff= 2 , 0
       0    -3.8   53.94    10.1       0   51.84
Permanent Ineff=
       F       F
Bank Sta=-3.8,10.1
XS Rating Curve= 0
Exp/Cntr=.3,.1

Type RM Length L Ch R = 1 ,39.047  ,14,14,14
#Sta/Elev= 16
   -14.4   53.74    -4.4   53.74    -4.2   53.94    -3.8   53.94      -3   53.34
       0   51.84       3   51.04     3.3   49.84     3.3   48.84     8.3   48.84
     8.3   49.84     8.8   50.84    10.1   51.84    10.6   51.84    10.9   51.64
    20.9   51.64
#Mann= 3 , 0 , 0
   -14.4    .035       0    -3.8    .035       0    10.1    .035       0
#XS Ineff= 2 , 0
       0    -3.8   53.94    10.1       0   51.84
Permanent Ineff=
       F       F
Bank Sta=-3.8,10.1
XS Rating Curve= 0
Exp/Cntr=.3,.1

Type RM Length L Ch R = 1 ,39.033  ,33,33,33
#Sta/Elev= 6
     -10   51.88       0   51.88      .3   49.18     5.3   49.18     5.6   51.88
    15.6   51.88
#Mann= 3 , 0 , 0
     -10    .035       0       0    .035       0     5.6    .035       0
#XS Ineff= 2 , 0
               0   51.88     5.6           51.88
Permanent Ineff=
       F       F
Bank Sta=0,5.6
XS Rating Curve= 0
Exp/Cntr=.3,.1

Type RM Length L Ch R = 1 ,39      ,50,50,50
#Sta/Elev= 16
    -9.9   54.61    -6.9   53.41    -3.9   52.21    -2.7   51.73     -.9   51.01
       0   50.11      .1   50.01      .1    50.1     2.1   48.01     5.1    48.1
     7.1   48.51     7.4   49.01     8.9   50.11     9.7   50.11    11.7   48.51
    21.7   48.51
#Mann= 3 , 0 , 0
    -9.9    .035       0       0    .035       0     8.9    .035       0
#XS Ineff= 2 , 0
               0   50.11     8.9           50.11
Permanent Ineff=
       F       F
Bank Sta=0,8.9
XS Rating Curve= 0
Exp/Cntr=.3,.1

Type RM Length L Ch R = 1 ,38      ,50,50,50
#Sta/Elev= 15
   -12.3   55.22    -9.3   54.32    -6.3   53.42    -3.3   52.52    -2.3   51.52
     -.3   49.52       0   49.22     1.7   47.52     4.7   47.52     6.7   48.02
       7   48.52     8.2   49.22       9   49.22      11   47.62      21   47.62
#Mann= 3 , 0 , 0
   -12.3    .035       0       0    .035       0     8.2    .035       0
#XS Ineff= 2 , 0
               0   49.22     8.2           49.22
Permanent Ineff=
       F       F
Bank Sta=0,8.2
XS Rating Curve= 0
Exp/Cntr=.3,.1

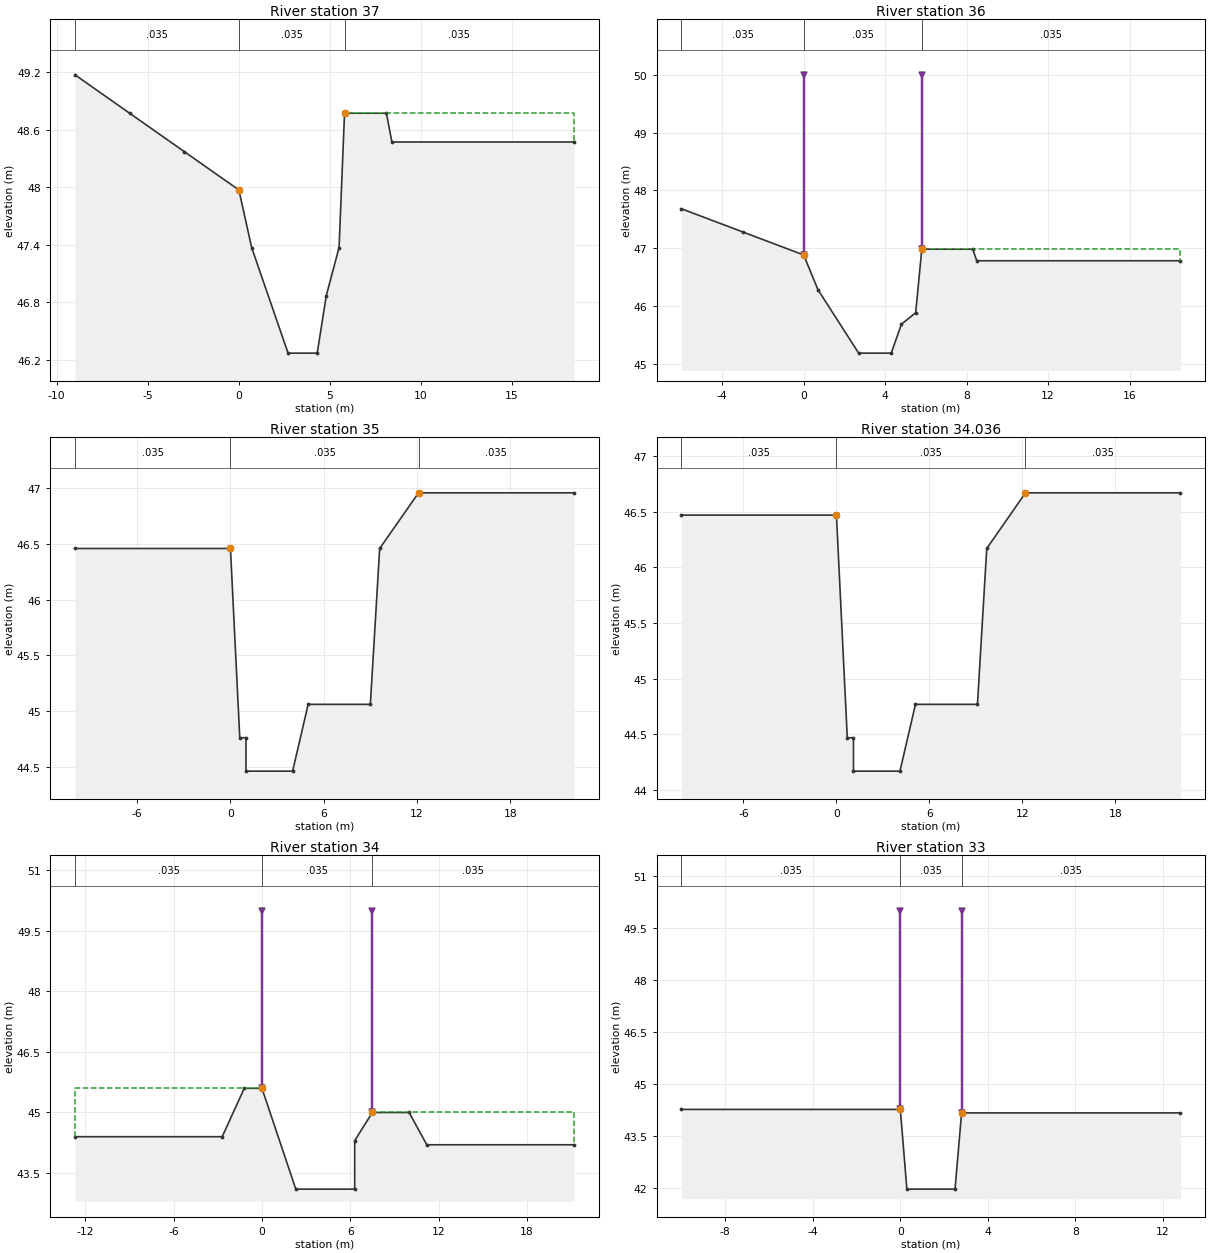
Type RM Length L Ch R = 1 ,37      ,50,50,50
#Sta/Elev= 13
      -9   49.17      -6   48.77      -3   48.37       0   47.97      .7   47.37
     2.7   46.27     4.3   46.27     4.8   46.87     5.5   47.37     5.8   48.77
     8.1   48.77     8.4   48.47    18.4   48.47
#Mann= 3 , 0 , 0
      -9    .035       0       0    .035       0     5.8    .035       0
#XS Ineff= 2 , 0
               0   47.97     5.8           48.77
Permanent Ineff=
       F       F
Bank Sta=0,5.8
XS Rating Curve= 0
Exp/Cntr=.3,.1

Type RM Length L Ch R = 1 ,36      ,50,50,50
#Sta/Elev= 12
      -6   47.68      -3   47.28       0   46.88      .7   46.28     2.7   45.18
     4.3   45.18     4.8   45.68     5.5   45.88     5.8   46.98     8.3   46.98
     8.5   46.78    18.5   46.78
#Mann= 3 , 0 , 0
      -6    .035       0       0    .035       0     5.8    .035       0
Levee=-1,0,50,-1,5.8,50,,
#XS Ineff= 2 , 0
               0   46.88     5.8           46.98
Permanent Ineff=
       F       F
Bank Sta=0,5.8
XS Rating Curve= 0
Exp/Cntr=.3,.1

Type RM Length L Ch R = 1 ,35      ,14,14,14
#Sta/Elev= 11
     -10   46.46       0   46.46      .6   44.76       1   44.76       1   44.46
       4   44.46       5   45.06       9   45.06     9.6   46.46    12.1   46.96
    22.1   46.96
#Mann= 3 , 0 , 0
     -10    .035       0       0    .035       0    12.1    .035       0
#XS Ineff= 2 , 0
               0   46.46    12.1           46.96
Permanent Ineff=
       F       F
Bank Sta=0,12.1
XS Rating Curve= 0
Exp/Cntr=.3,.1

Type RM Length L Ch R = 1 ,34.036  ,36,36,36
#Sta/Elev= 11
     -10   46.47       0   46.47      .7   44.47     1.1   44.47     1.1   44.17
     4.1   44.17     5.1   44.77     9.1   44.77     9.7   46.17    12.2   46.67
    22.2   46.67
#Mann= 3 , 0 , 0
     -10    .035       0       0    .035       0    12.2    .035       0
#XS Ineff= 2 , 0
               0   46.47    12.2           46.67
Permanent Ineff=
       F       F
Bank Sta=0,12.2
XS Rating Curve= 0
Exp/Cntr=.3,.1

Type RM Length L Ch R = 1 ,34      ,50,50,50
#Sta/Elev= 11
   -12.7    44.4    -2.7    44.4    -1.2    45.6       0    45.6     2.3    43.1
     6.3    43.1     6.3    44.3     7.5      45      10      45    11.2    44.2
    21.2    44.2
#Mann= 3 , 0 , 0
   -12.7    .035       0       0    .035       0     7.5    .035       0
Levee=-1,0,50,-1,7.5,50,,
#XS Ineff= 2 , 0
               0    45.6     7.5              45
Permanent Ineff=
       F       F
Bank Sta=0,7.5
XS Rating Curve= 0
Exp/Cntr=.3,.1

Type RM Length L Ch R = 1 ,33      ,22,22,22
#Sta/Elev= 6
     -10   44.27       0   44.27      .3   41.97     2.5   41.97     2.8   44.17
    12.8   44.17
#Mann= 3 , 0 , 0
     -10    .035       0       0    .035       0     2.8    .035       0
Levee=-1,0,50,-1,2.8,50,,
#XS Ineff= 2 , 0
               0   44.27     2.8           44.17
Permanent Ineff=
       F       F
Bank Sta=0,2.8
XS Rating Curve= 0
Exp/Cntr=.3,.1

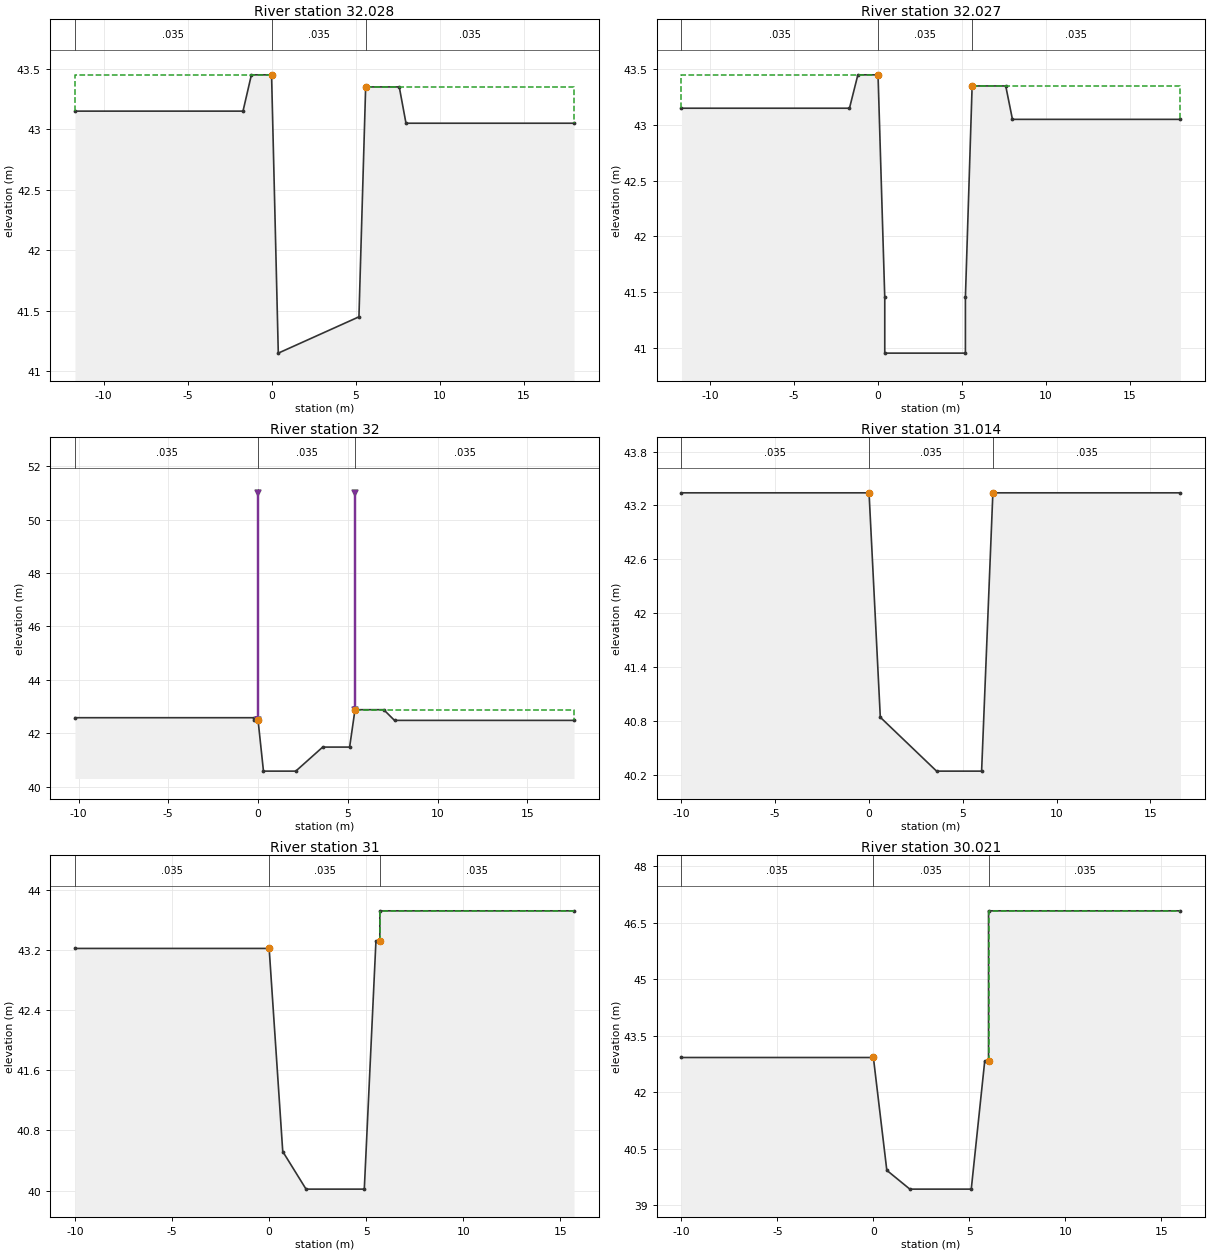
Type RM Length L Ch R = 1 ,32.028  ,1,1,1
#Sta/Elev= 10
   -11.7   43.15    -1.7   43.15    -1.2   43.45       0   43.45      .4   41.15
     5.2   41.45     5.6   43.35     7.6   43.35       8   43.05      18   43.05
#Mann= 3 , 0 , 0
   -11.7    .035       0       0    .035       0     5.6    .035       0
#XS Ineff= 2 , 0
               0   43.45     5.6           43.35
Permanent Ineff=
       F       F
Bank Sta=0,5.6
XS Rating Curve= 0
Exp/Cntr=.3,.1

Type RM Length L Ch R = 1 ,32.027  ,27,27,27
#Sta/Elev= 12
   -11.7   43.15    -1.7   43.15    -1.2   43.45       0   43.45      .4   41.45
      .4   40.95     5.2   40.95     5.2   41.45     5.6   43.35     7.6   43.35
       8   43.05      18   43.05
#Mann= 3 , 0 , 0
   -11.7    .035       0       0    .035       0     5.6    .035       0
#XS Ineff= 2 , 0
               0   43.45     5.6           43.35
Permanent Ineff=
       F       F
Bank Sta=0,5.6
XS Rating Curve= 0
Exp/Cntr=.3,.1

Type RM Length L Ch R = 1 ,32      ,36,36,36
#Sta/Elev= 12
   -10.2   42.58     -.2   42.58     -.2   42.48       0   42.48      .3   40.58
     2.1   40.58     3.6   41.48     5.1   41.48     5.4   42.88       7   42.88
     7.6   42.48    17.6   42.48
#Mann= 3 , 0 , 0
   -10.2    .035       0       0    .035       0     5.4    .035       0
Levee=-1,0,51,-1,5.4,51,,
#XS Ineff= 2 , 0
       0       0   42.48     5.4       0   42.88
Permanent Ineff=
       F       F
Bank Sta=0,5.4
XS Rating Curve= 0
Exp/Cntr=.3,.1

Type RM Length L Ch R = 1 ,31.014  ,14,14,14
#Sta/Elev= 7
     -10   43.34       0   43.34      .6   40.84     3.6   40.24       6   40.24
     6.6   43.34    16.6   43.34
#Mann= 3 , 0 , 0
     -10    .035       0       0    .035       0     6.6    .035       0
#XS Ineff= 2 , 0
               0   43.34     6.6           43.34
Permanent Ineff=
       F       F
Bank Sta=0,6.6
XS Rating Curve= 0
Exp/Cntr=.3,.1

Type RM Length L Ch R = 1 ,31      ,29,29,29
#Sta/Elev= 9
     -10   43.22       0   43.22      .7   40.52     1.9   40.02     4.9   40.02
     5.5   43.32     5.7   43.32     5.7   43.72    15.7   43.72
#Mann= 3 , 0 , 0
     -10    .035       0       0    .035       0     5.7    .035       0
#XS Ineff= 2 , 0
               0   43.22     5.7           43.72
Permanent Ineff=
       F       F
Bank Sta=0,5.7
XS Rating Curve= 0
Exp/Cntr=.3,.1

Type RM Length L Ch R = 1 ,30.021  ,21,21,21
#Sta/Elev= 9
     -10   42.92       0   42.92      .7   39.92     1.9   39.42     5.1   39.42
     5.8   42.82       6   42.82       6   46.82      16   46.82
#Mann= 3 , 0 , 0
     -10    .035       0       0    .035       0       6    .035       0
#XS Ineff= 2 , 0
               0   42.92       6           46.82
Permanent Ineff=
       F       F
Bank Sta=0,6
XS Rating Curve= 0
Exp/Cntr=.3,.1

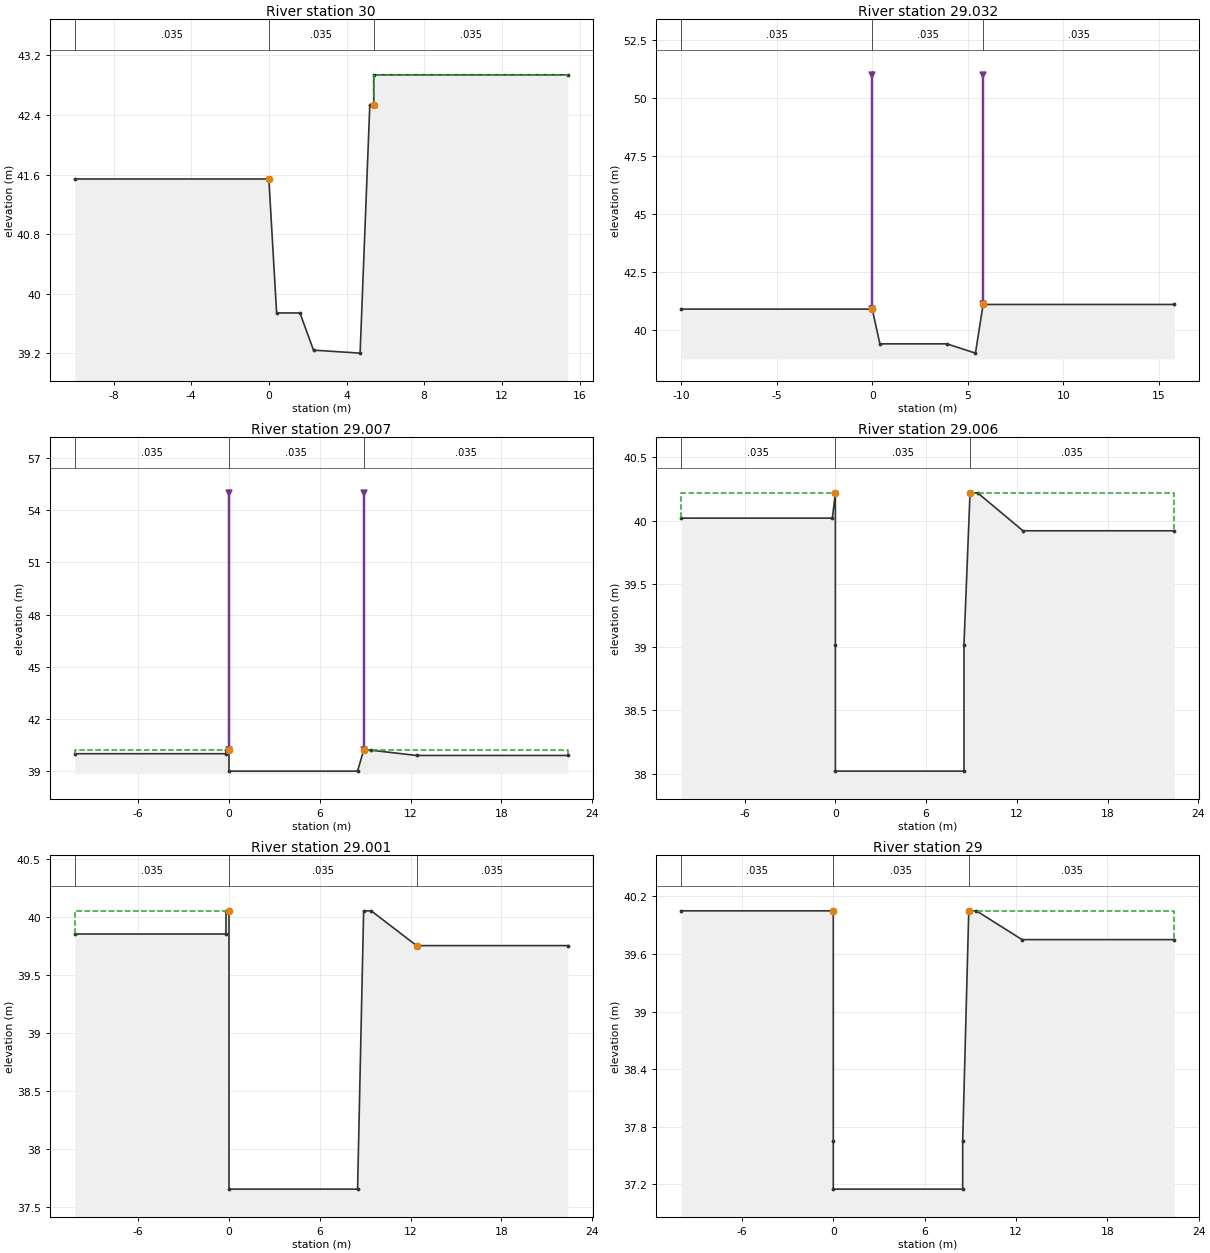
Type RM Length L Ch R = 1 ,30      ,18,18,18
#Sta/Elev= 10
     -10   41.54       0   41.54      .4   39.74     1.6   39.74     2.3   39.24
     4.7    39.2     5.2   42.54     5.4   42.54     5.4   42.94    15.4   42.94
#Mann= 3 , 0 , 0
     -10    .035       0       0    .035       0     5.4    .035       0
#XS Ineff= 2 , 0
               0   41.54     5.4           42.94
Permanent Ineff=
       F       F
Bank Sta=0,5.4
XS Rating Curve= 0
Exp/Cntr=.3,.1

Type RM Length L Ch R = 1 ,29.032  ,25,25,25
#Sta/Elev= 7
     -10   40.89       0   40.89      .4   39.39     3.9   39.39     5.4   38.99
     5.8   41.09    15.8   41.09
#Mann= 3 , 0 , 0
     -10    .035       0       0    .035       0     5.8    .035       0
Levee=-1,0,51,-1,5.8,51,,
#XS Ineff= 2 , 0
               0   40.89     5.8           41.09
Permanent Ineff=
       F       F
Bank Sta=0,5.8
XS Rating Curve= 0
Exp/Cntr=.3,.1

Type RM Length L Ch R = 1 ,29.007  ,1,1,1
#Sta/Elev= 10
   -10.2   40.02     -.2   40.02     -.2   40.22       0   40.22       0   39.02
     8.5   39.02     8.9   40.22     9.4   40.22    12.4   39.92    22.4   39.92
#Mann= 3 , 0 , 0
   -10.2    .035       0       0    .035       0     8.9    .035       0
Levee=-1,0,55,-1,8.9,55,,
#XS Ineff= 2 , 0
               0   40.22     8.9           40.22
Permanent Ineff=
       F       F
Bank Sta=0,8.9
XS Rating Curve= 0
Exp/Cntr=.3,.1

Type RM Length L Ch R = 1 ,29.006  ,5,5,5
#Sta/Elev= 11
   -10.2   40.02     -.2   40.02       0   40.22       0   39.02       0   38.02
     8.5   38.02     8.5   39.02     8.9   40.22     9.4   40.22    12.4   39.92
    22.4   39.92
#Mann= 3 , 0 , 0
   -10.2    .035       0       0    .035       0     8.9    .035       0
#XS Ineff= 2 , 0
               0   40.22     8.9           40.22
Permanent Ineff=
       F       F
Bank Sta=0,8.9
XS Rating Curve= 0
Exp/Cntr=.3,.1

Type RM Length L Ch R = 1 ,29.001  ,1,1,1
#Sta/Elev= 10
   -10.2   39.85     -.2   39.85     -.2   40.05       0   40.05       0   37.65
     8.5   37.65     8.9   40.05     9.4   40.05    12.4   39.75    22.4   39.75
#Mann= 3 , 0 , 0
   -10.2    .035       0       0    .035       0    12.4    .035       0
#XS Ineff= 2 , 0
               0   40.05    12.4           39.75
Permanent Ineff=
       F       F
Bank Sta=0,12.4
XS Rating Curve= 0
Exp/Cntr=.3,.1

Type RM Length L Ch R = 1 ,29      ,50,50,50
#Sta/Elev= 10
     -10   40.05       0   40.05       0   37.65       0   37.15     8.5   37.15
     8.5   37.65     8.9   40.05     9.4   40.05    12.4   39.75    22.4   39.75
#Mann= 3 , 0 , 0
     -10    .035       0       0    .035       0     8.9    .035       0
#XS Ineff= 2 , 0
               0   40.05     8.9           40.05
Permanent Ineff=
       F       F
Bank Sta=0,8.9
XS Rating Curve= 0
Exp/Cntr=.3,.1