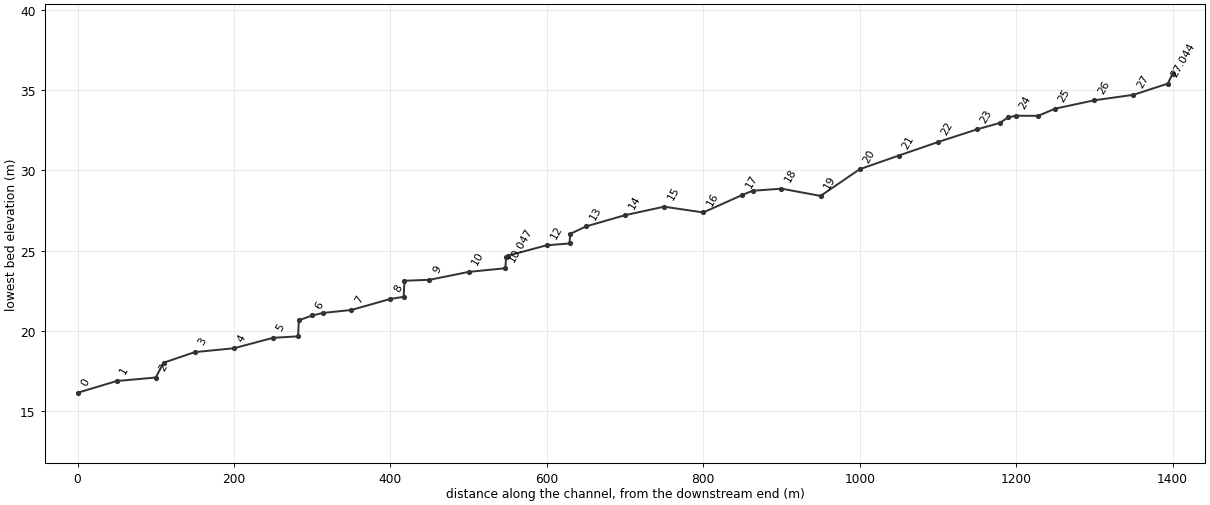
HEC-RAS study bbc.prj: bobong-ch

--- bbc.g01 (geometry) --- (continued)

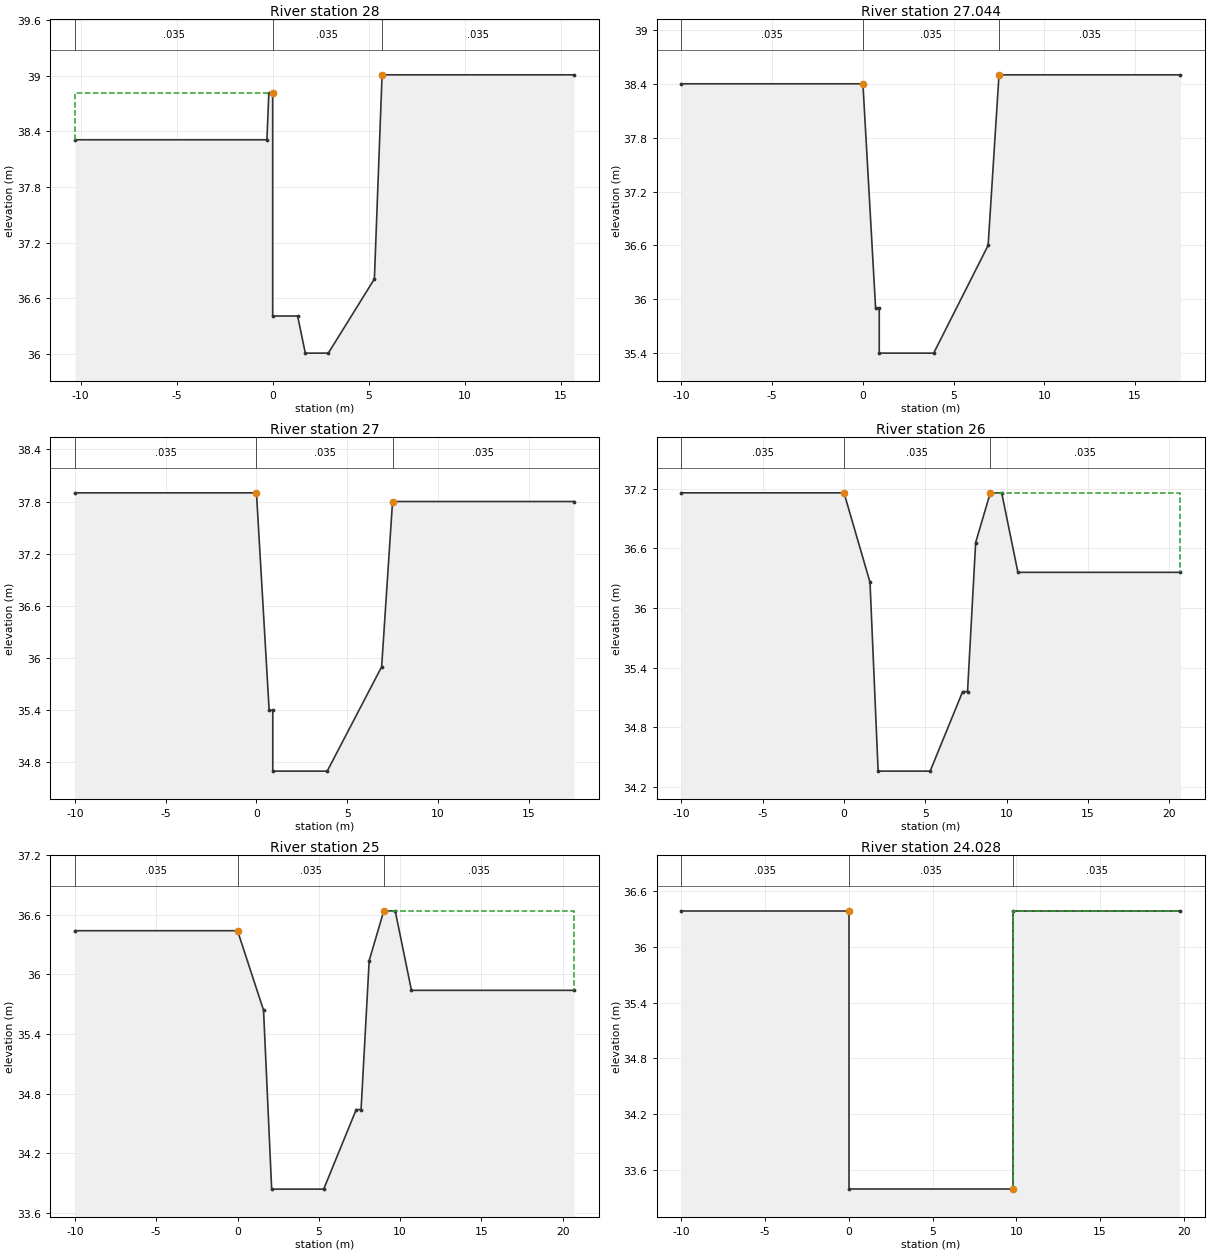
Type RM Length L Ch R = 1 ,28      ,6,6,6
#Sta/Elev= 11
   -10.3   38.31     -.3   38.31     -.2   38.81       0   38.81       0   36.41
     1.3   36.41     1.7   36.01     2.9   36.01     5.3   36.81     5.7   39.01
    15.7   39.01
#Mann= 3 , 0 , 0
   -10.3    .035       0       0    .035       0     5.7    .035       0
#XS Ineff= 2 , 0
               0   38.81     5.7           39.01
Permanent Ineff=
       F       F
Bank Sta=0,5.7
XS Rating Curve= 0
Exp/Cntr=.3,.1

Type RM Length L Ch R = 1 ,27.044  ,44,44,44
#Sta/Elev= 9
     -10    38.4       0    38.4      .7    35.9      .9    35.9      .9    35.4
     3.9    35.4     6.9    36.6     7.5    38.5    17.5    38.5
#Mann= 3 , 0 , 0
     -10    .035       0       0    .035       0     7.5    .035       0
#XS Ineff= 2 , 0
               0    38.4     7.5            38.5
Permanent Ineff=
       F       F
Bank Sta=0,7.5
XS Rating Curve= 0
Exp/Cntr=.3,.1

Type RM Length L Ch R = 1 ,27      ,50,50,50
#Sta/Elev= 9
     -10    37.9       0    37.9      .7    35.4      .9    35.4      .9    34.7
     3.9    34.7     6.9    35.9     7.5    37.8    17.5    37.8
#Mann= 3 , 0 , 0
     -10    .035       0       0    .035       0     7.5    .035       0
#XS Ineff= 2 , 0
               0    37.9     7.5            37.8
Permanent Ineff=
       F       F
Bank Sta=0,7.5
XS Rating Curve= 0
Exp/Cntr=.3,.1

Type RM Length L Ch R = 1 ,26      ,50,50,50
#Sta/Elev= 12
     -10   37.16       0   37.16     1.6   36.26     2.1   34.36     5.3   34.36
     7.3   35.16     7.6   35.16     8.1   36.66       9   37.16     9.7   37.16
    10.7   36.36    20.7   36.36
#Mann= 3 , 0 , 0
     -10    .035       0       0    .035       0       9    .035       0
#XS Ineff= 2 , 0
               0   37.16       9           37.16
Permanent Ineff=
       F       F
Bank Sta=0,9
XS Rating Curve= 0
Exp/Cntr=.3,.1

Type RM Length L Ch R = 1 ,25      ,22,22,22
#Sta/Elev= 12
     -10   36.44       0   36.44     1.6   35.64     2.1   33.84     5.3   33.84
     7.3   34.64     7.6   34.64     8.1   36.14       9   36.64     9.7   36.64
    10.7   35.84    20.7   35.84
#Mann= 3 , 0 , 0
     -10    .035       0       0    .035       0       9    .035       0
#XS Ineff= 2 , 0
               0   36.44       9           36.64
Permanent Ineff=
       F       F
Bank Sta=0,9
XS Rating Curve= 0
Exp/Cntr=.3,.1

Type RM Length L Ch R = 1 ,24.028  ,28,28,28
#Sta/Elev= 6
     -10   36.39       0   36.39       0   33.39     9.8   33.39     9.8   36.39
    19.8   36.39
#Mann= 3 , 0 , 0
     -10    .035       0       0    .035       0     9.8    .035       0
#XS Ineff= 2 , 0
               0   36.39     9.8           36.39
Permanent Ineff=
       F       F
Bank Sta=0,9.8
XS Rating Curve= 0
Exp/Cntr=.3,.1

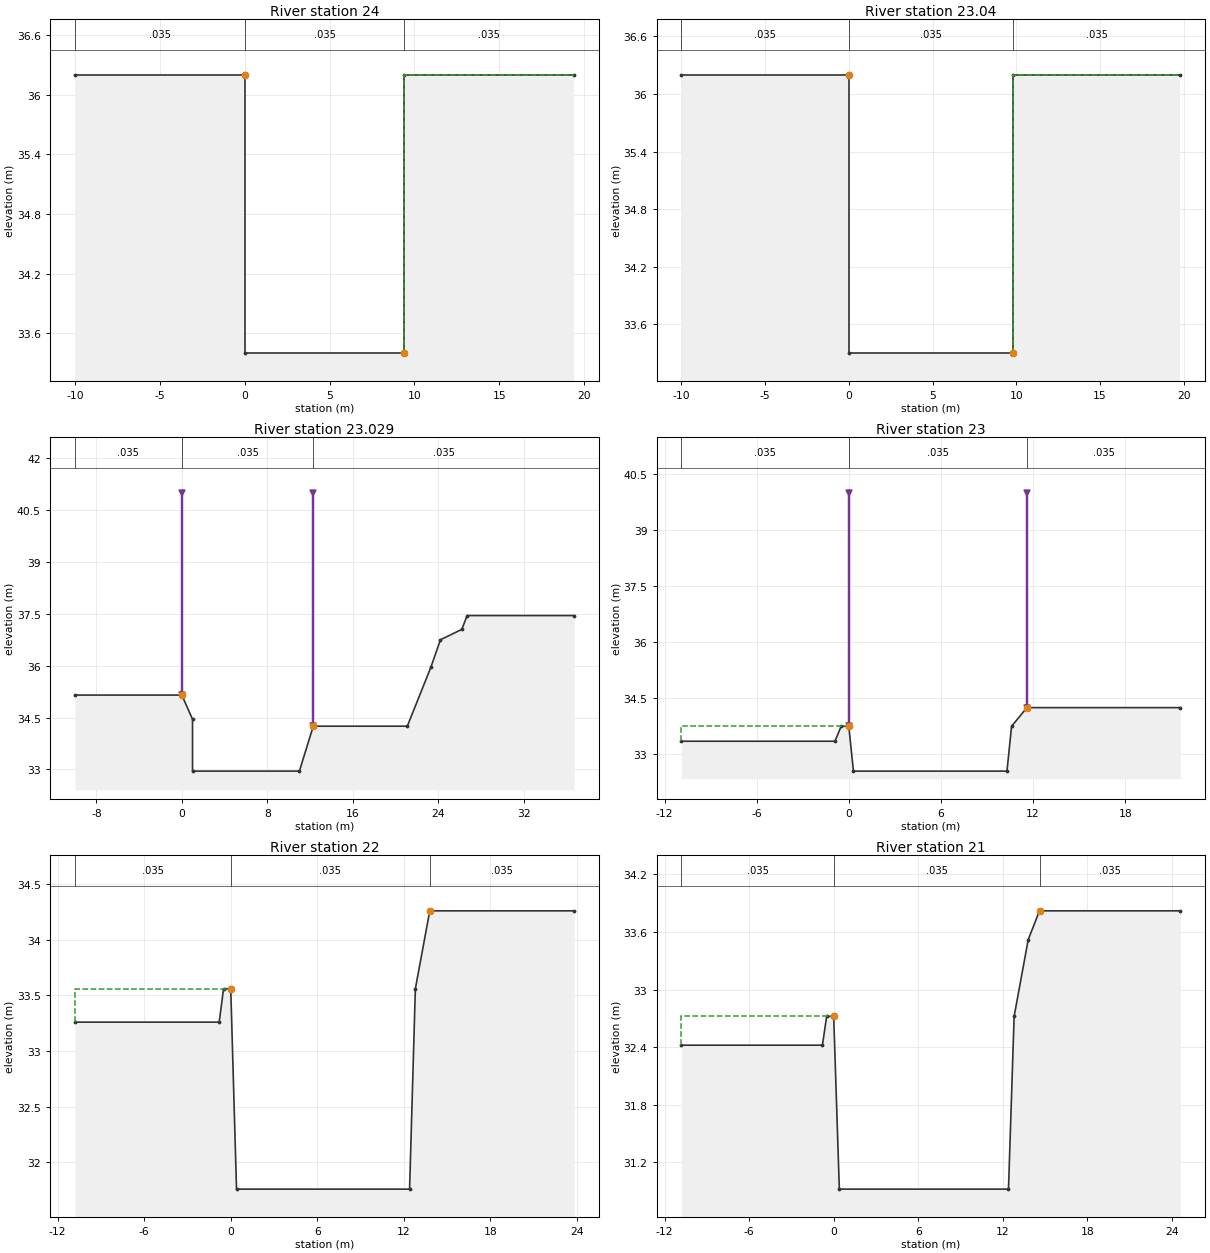
Type RM Length L Ch R = 1 ,24      ,10,10,10
#Sta/Elev= 6
     -10    36.2       0    36.2       0    33.4     9.4    33.4     9.4    36.2
    19.4    36.2
#Mann= 3 , 0 , 0
     -10    .035       0       0    .035       0     9.4    .035       0
#XS Ineff= 2 , 0
               0    36.2     9.4            36.2
Permanent Ineff=
       F       F
Bank Sta=0,9.4
XS Rating Curve= 0
Exp/Cntr=.3,.1

Type RM Length L Ch R = 1 ,23.04   ,11,11,11
#Sta/Elev= 6
     -10    36.2       0    36.2       0    33.3     9.8    33.3     9.8    36.2
    19.8    36.2
#Mann= 3 , 0 , 0
     -10    .035       0       0    .035       0     9.8    .035       0
#XS Ineff= 2 , 0
               0    36.2     9.8            36.2
Permanent Ineff=
       F       F
Bank Sta=0,9.8
XS Rating Curve= 0
Exp/Cntr=.3,.1

Type RM Length L Ch R = 1 ,23.029  ,29,29,29
#Sta/Elev= 12
     -10   35.15       0   35.15       1   34.45       1   32.95      11   32.95
    12.3   34.25    21.1   34.25    23.3   35.95    24.2   36.75    26.2   37.05
    26.7   37.45    36.7   37.45
#Mann= 3 , 0 , 0
     -10    .035       0       0    .035       0    12.3    .035       0
Levee=-1,0,41,-1,12.3,41,,
#XS Ineff= 2 , 0
               0   35.15    12.3           34.25
Permanent Ineff=
       F       F
Bank Sta=0,12.3
XS Rating Curve= 0
Exp/Cntr=.3,.1

Type RM Length L Ch R = 1 ,23      ,50,50,50
#Sta/Elev= 9
   -10.9   33.35     -.9   33.35     -.5   33.75       0   33.75      .3   32.55
    10.3   32.55    10.6   33.75    11.6   34.25    21.6   34.25
#Mann= 3 , 0 , 0
   -10.9    .035       0       0    .035       0    11.6    .035       0
Levee=-1,0,40,-1,11.6,40,,
#XS Ineff= 2 , 0
               0   33.75    11.6           34.25
Permanent Ineff=
       F       F
Bank Sta=0,11.6
XS Rating Curve= 0
Exp/Cntr=.3,.1

Type RM Length L Ch R = 1 ,22      ,50,50,50
#Sta/Elev= 9
   -10.8   33.26     -.8   33.26     -.5   33.56       0   33.56      .4   31.76
    12.4   31.76    12.8   33.56    13.8   34.26    23.8   34.26
#Mann= 3 , 0 , 0
   -10.8    .035       0       0    .035       0    13.8    .035       0
#XS Ineff= 2 , 0
               0   33.56    13.8           34.26
Permanent Ineff=
       F       F
Bank Sta=0,13.8
XS Rating Curve= 0
Exp/Cntr=.3,.1

Type RM Length L Ch R = 1 ,21      ,50,50,50
#Sta/Elev= 10
   -10.8   32.42     -.8   32.42     -.5   32.72       0   32.72      .4   30.92
    12.4   30.92    12.8   32.72    13.8   33.52    14.6   33.82    24.6   33.82
#Mann= 3 , 0 , 0
   -10.8    .035       0       0    .035       0    14.6    .035       0
#XS Ineff= 2 , 0
               0   32.72    14.6           33.82
Permanent Ineff=
       F       F
Bank Sta=0,14.6
XS Rating Curve= 0
Exp/Cntr=.3,.1

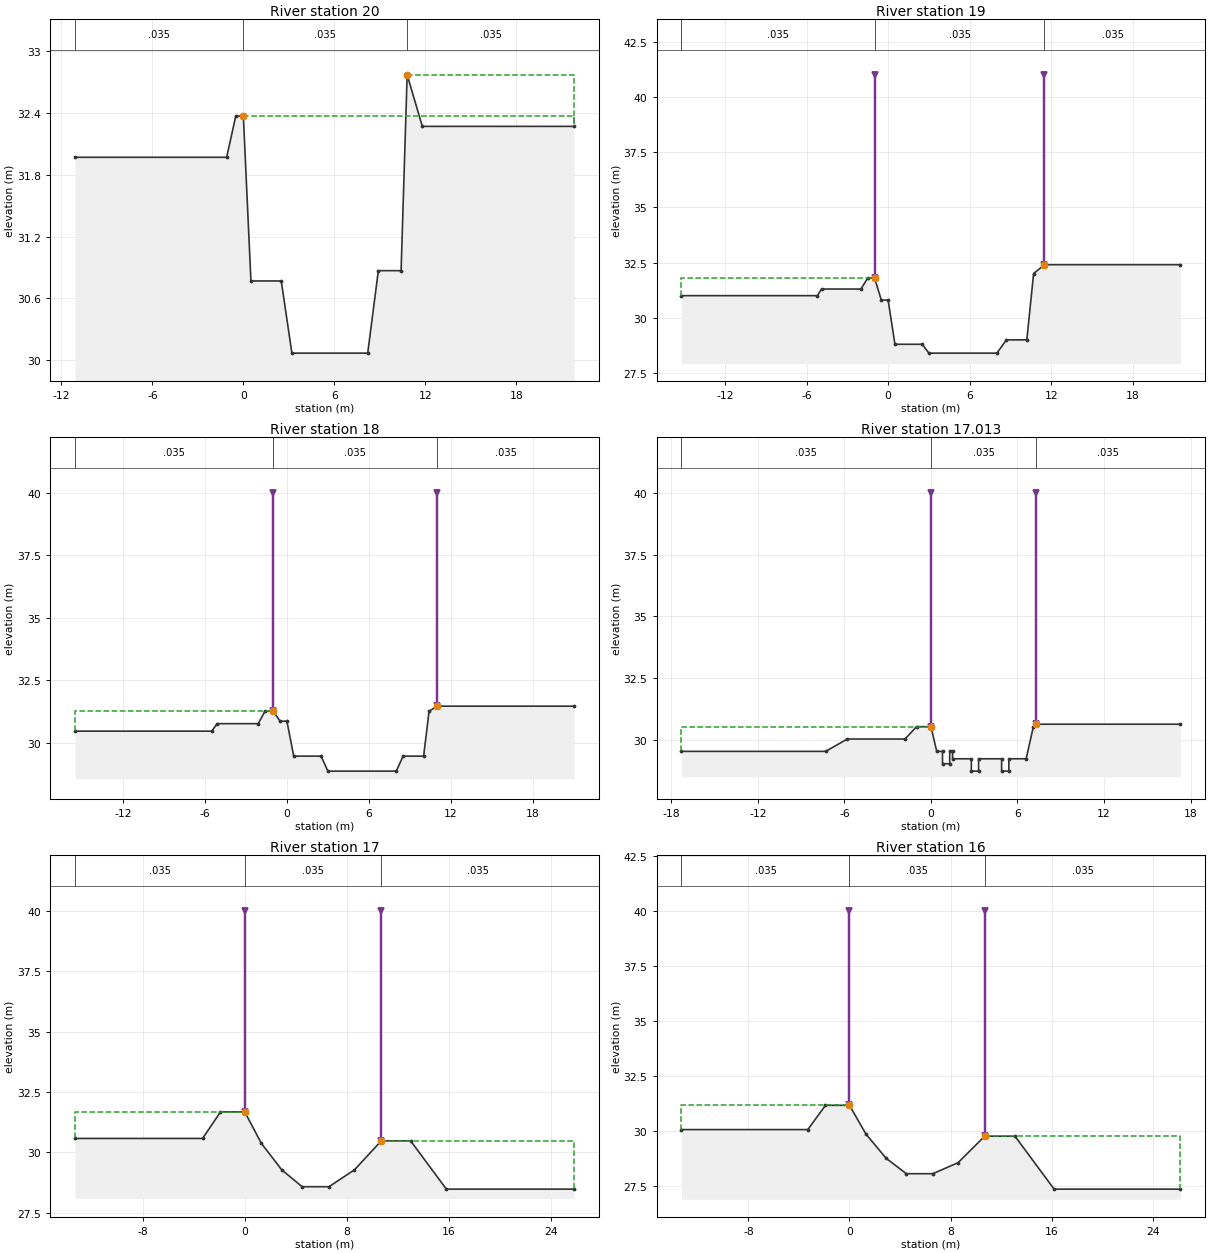
Type RM Length L Ch R = 1 ,20      ,50,50,50
#Sta/Elev= 13
   -11.1   31.97    -1.1   31.97     -.5   32.37       0   32.37      .5   30.77
     2.5   30.77     3.2   30.07     8.2   30.07     8.9   30.87    10.4   30.87
    10.8   32.77    11.8   32.27    21.8   32.27
#Mann= 3 , 0 , 0
   -11.1    .035       0       0    .035       0    10.8    .035       0
#XS Ineff= 2 , 0
       0       0   32.37    10.8       0   32.77
Permanent Ineff=
       F       F
Bank Sta=0,10.8
XS Rating Curve= 0
Exp/Cntr=.3,.1

Type RM Length L Ch R = 1 ,19      ,50,50,50
#Sta/Elev= 17
   -15.2   31.01    -5.2   31.01    -4.9   31.31      -2   31.31    -1.5   31.81
      -1   31.81     -.5   30.81       0   30.81      .5   28.81     2.5   28.81
       3   28.41       8   28.41     8.7   29.01    10.2   29.01    10.7   32.01
    11.5   32.41    21.5   32.41
#Mann= 3 , 0 , 0
   -15.2    .035       0      -1    .035       0    11.5    .035       0
Levee=-1,-1,41,-1,11.5,41,,
#XS Ineff= 2 , 0
              -1   31.81    11.5           32.41
Permanent Ineff=
       F       F
Bank Sta=-1,11.5
XS Rating Curve= 0
Exp/Cntr=.3,.1

Type RM Length L Ch R = 1 ,18      ,37,37,37
#Sta/Elev= 17
   -15.5   30.46    -5.5   30.46    -5.1   30.76    -2.1   30.76    -1.6   31.26
      -1   31.26     -.5   30.86       0   30.86      .5   29.46     2.5   29.46
       3   28.86       8   28.86     8.5   29.46      10   29.46    10.4   31.26
      11   31.46      21   31.46
#Mann= 3 , 0 , 0
   -15.5    .035       0      -1    .035       0      11    .035       0
Levee=-1,-1,40,-1,11,40,,
#XS Ineff= 2 , 0
              -1   31.26      11           31.46
Permanent Ineff=
       F       F
Bank Sta=-1,11
XS Rating Curve= 0
Exp/Cntr=.3,.1

Type RM Length L Ch R = 1 ,17.013  ,13,13,13
#Sta/Elev= 25
   -17.3   29.53    -7.3   29.53    -5.8   30.03    -1.8   30.03      -1   30.53
       0   30.53      .4   29.53      .8   29.53      .8   29.03     1.3   29.03
     1.3   29.53     1.5   29.53     1.5   29.23     2.8   29.23     2.8   28.73
     3.3   28.73     3.3   29.23     4.9   29.23     4.9   28.73     5.4   28.73
     5.4   29.23     6.6   29.23     7.1   30.53     7.3   30.63    17.3   30.63
#Mann= 3 , 0 , 0
   -17.3    .035       0       0    .035       0     7.3    .035       0
Levee=-1,0,40,-1,7.3,40,,
#XS Ineff= 2 , 0
               0   30.53     7.3           30.63
Permanent Ineff=
       F       F
Bank Sta=0,7.3
XS Rating Curve= 0
Exp/Cntr=.3,.1

Type RM Length L Ch R = 1 ,17      ,50,50,50
#Sta/Elev= 13
   -13.3   30.57    -3.3   30.57    -1.9   31.67       0   31.67     1.3   30.37
     2.9   29.27     4.5   28.57     6.6   28.57     8.6   29.27    10.7   30.47
      13   30.47    15.8   28.47    25.8   28.47
#Mann= 3 , 0 , 0
   -13.3    .035       0       0    .035       0    10.7    .035       0
Levee=-1,0,40,-1,10.7,40,,
#XS Ineff= 2 , 0
               0   31.67    10.7           30.47
Permanent Ineff=
       F       F
Bank Sta=0,10.7
XS Rating Curve= 0
Exp/Cntr=.3,.1

Type RM Length L Ch R = 1 ,16      ,50,50,50
#Sta/Elev= 13
   -13.3   30.08    -3.3   30.08    -1.9   31.18       0   31.18     1.3   29.88
     2.9   28.78     4.5   28.08     6.6   28.08     8.6   28.58    10.7   29.78
    13.1   29.78    16.2   27.38    26.2   27.38
#Mann= 3 , 0 , 0
   -13.3    .035       0       0    .035       0    10.7    .035       0
Levee=-1,0,40,-1,10.7,40,,
#XS Ineff= 2 , 0
               0   31.18    10.7           29.78
Permanent Ineff=
       F       F
Bank Sta=0,10.7
XS Rating Curve= 0
Exp/Cntr=.3,.1

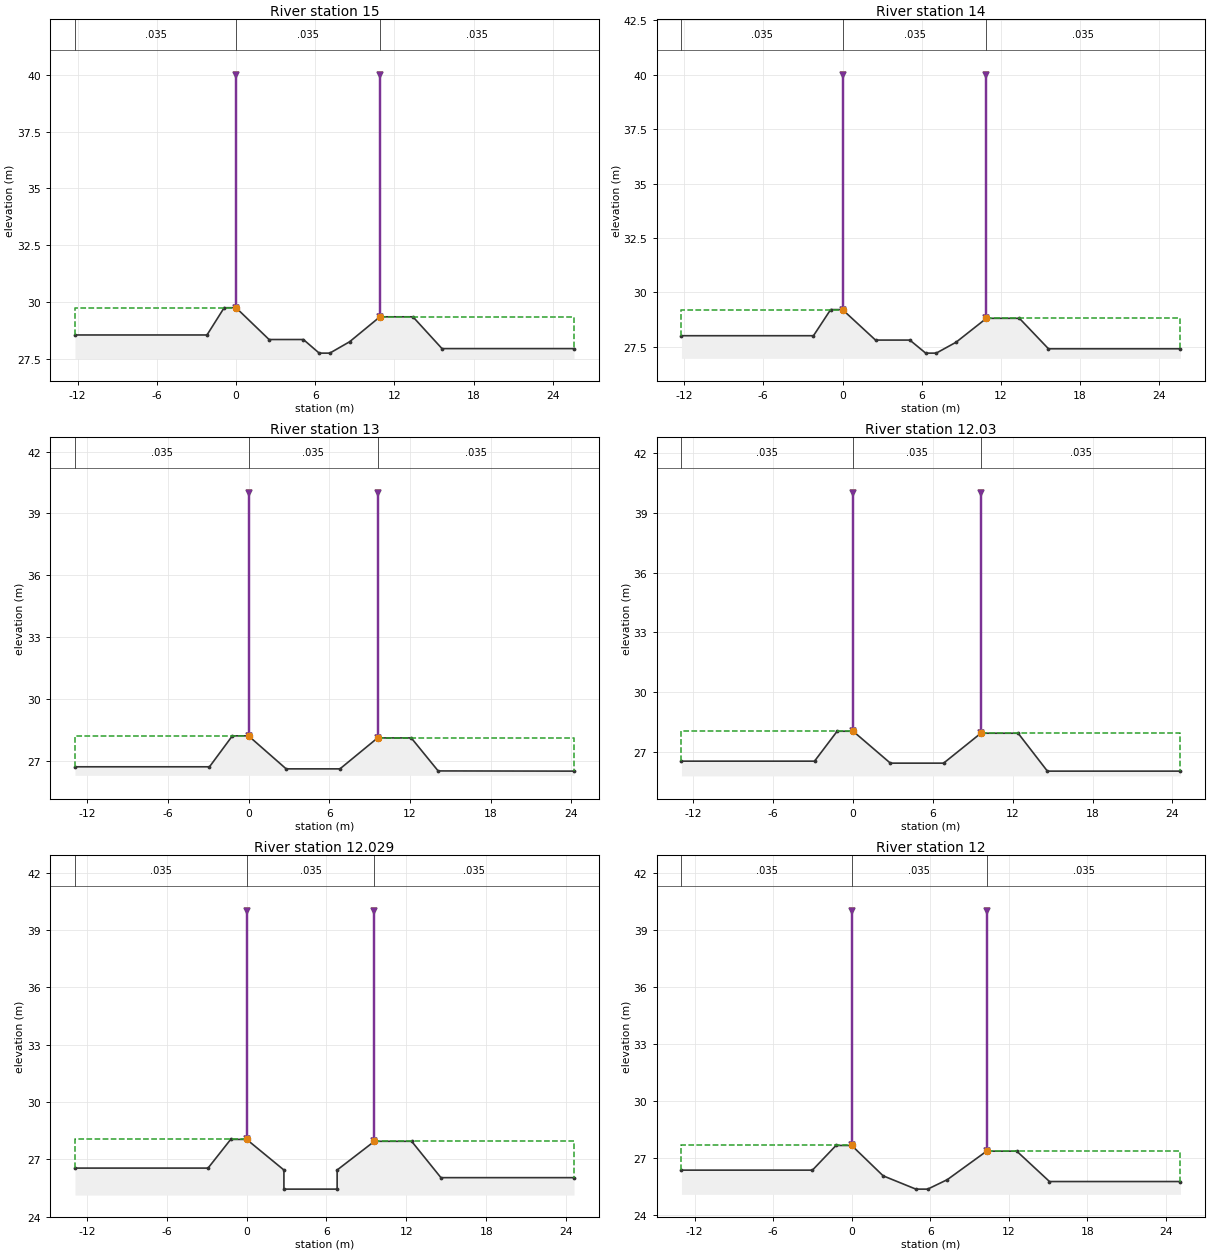
Type RM Length L Ch R = 1 ,15      ,50,50,50
#Sta/Elev= 13
   -12.2   28.54    -2.2   28.54     -.9   29.74       0   29.74     2.5   28.34
     5.1   28.34     6.3   27.74     7.1   27.74     8.6   28.24    10.9   29.34
    13.4   29.34    15.6   27.94    25.6   27.94
#Mann= 3 , 0 , 0
   -12.2    .035       0       0    .035       0    10.9    .035       0
Levee=-1,0,40,-1,10.9,40,,
#XS Ineff= 2 , 0
               0   29.74    10.9           29.34
Permanent Ineff=
       F       F
Bank Sta=0,10.9
XS Rating Curve= 0
Exp/Cntr=.3,.1

Type RM Length L Ch R = 1 ,14      ,50,50,50
#Sta/Elev= 13
   -12.2   28.01    -2.2   28.01     -.9   29.21       0   29.21     2.5   27.81
     5.1   27.81     6.3   27.21     7.1   27.21     8.6   27.71    10.9   28.81
    13.4   28.81    15.6   27.41    25.6   27.41
#Mann= 3 , 0 , 0
   -12.2    .035       0       0    .035       0    10.9    .035       0
Levee=-1,0,40,-1,10.9,40,,
#XS Ineff= 2 , 0
               0   29.21    10.9           28.81
Permanent Ineff=
       F       F
Bank Sta=0,10.9
XS Rating Curve= 0
Exp/Cntr=.3,.1

Type RM Length L Ch R = 1 ,13      ,20,20,20
#Sta/Elev= 10
   -12.9   26.72    -2.9   26.72    -1.2   28.22       0   28.22     2.8   26.62
     6.8   26.62     9.6   28.12    12.1   28.12    14.1   26.52    24.2   26.51
#Mann= 3 , 0 , 0
   -12.9    .035       0       0    .035       0     9.6    .035       0
Levee=-1,0,40,-1,9.6,40,,
#XS Ineff= 2 , 0
               0   28.22     9.6           28.12
Permanent Ineff=
       F       F
Bank Sta=0,9.6
XS Rating Curve= 0
Exp/Cntr=.3,.1

Type RM Length L Ch R = 1 ,12.03   ,1,1,1
#Sta/Elev= 10
   -12.9   26.55    -2.9   26.55    -1.2   28.05       0   28.05     2.8   26.45
     6.8   26.45     9.6   27.95    12.4   27.95    14.6   26.05    24.6   26.05
#Mann= 3 , 0 , 0
   -12.9    .035       0       0    .035       0     9.6    .035       0
Levee=-1,0,40,-1,9.6,40,,
#XS Ineff= 2 , 0
               0   28.05     9.6           27.95
Permanent Ineff=
       F       F
Bank Sta=0,9.6
XS Rating Curve= 0
Exp/Cntr=.3,.1

Type RM Length L Ch R = 1 ,12.029  ,29,29,29
#Sta/Elev= 12
   -12.9   26.55    -2.9   26.55    -1.2   28.05       0   28.05     2.8   26.45
     2.8   25.45     6.8   25.45     6.8   26.45     9.6   27.95    12.4   27.95
    14.6   26.05    24.6   26.05
#Mann= 3 , 0 , 0
   -12.9    .035       0       0    .035       0     9.6    .035       0
Levee=-1,0,40,-1,9.6,40,,
#XS Ineff= 2 , 0
               0   28.05     9.6           27.95
Permanent Ineff=
       F       F
Bank Sta=0,9.6
XS Rating Curve= 0
Exp/Cntr=.3,.1

Type RM Length L Ch R = 1 ,12      ,50,50,50
#Sta/Elev= 12
     -13   26.34      -3   26.34    -1.2   27.64       0   27.64     2.4   26.04
     4.9   25.34     5.8   25.34     7.3   25.84    10.3   27.34    12.6   27.34
    15.1   25.74    25.1   25.74
#Mann= 3 , 0 , 0
     -13    .035       0       0    .035       0    10.3    .035       0
Levee=-1,0,40,-1,10.3,40,,
#XS Ineff= 2 , 0
               0   27.64    10.3           27.34
Permanent Ineff=
       F       F
Bank Sta=0,10.3
XS Rating Curve= 0
Exp/Cntr=.3,.1

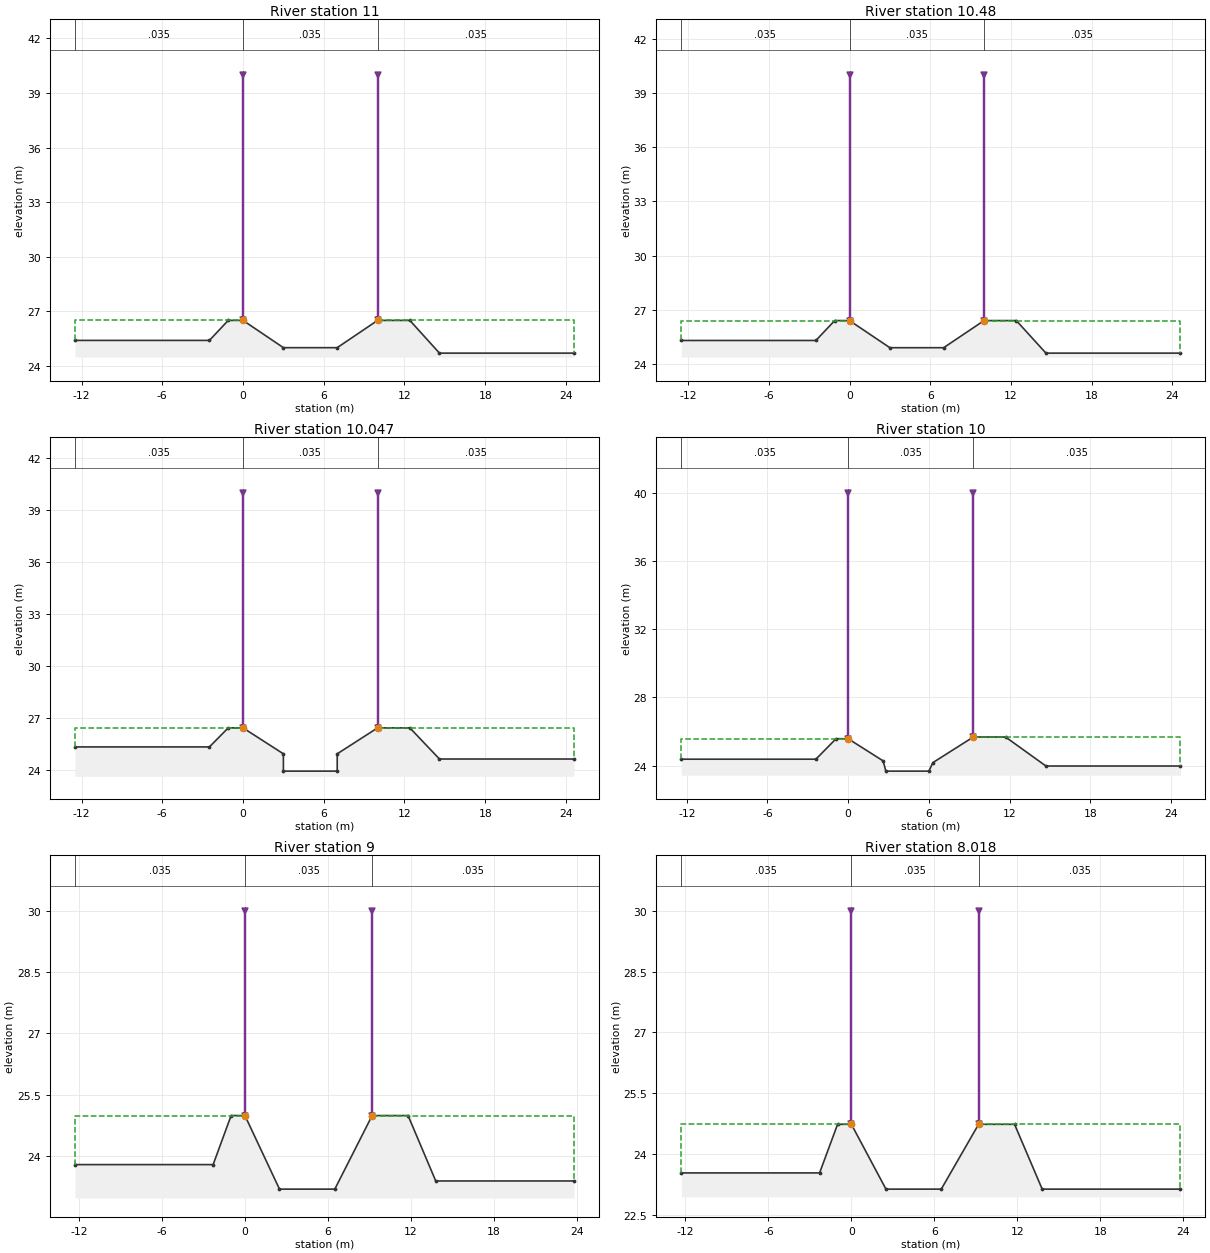
Type RM Length L Ch R = 1 ,11      ,2,2,2
#Sta/Elev= 10
   -12.5   25.39    -2.5   25.39    -1.1   26.49       0   26.49       3   24.99
       7   24.99      10   26.49    12.4   26.49    14.6   24.69    24.6   24.69
#Mann= 3 , 0 , 0
   -12.5    .035       0       0    .035       0      10    .035       0
Levee=-1,0,40,-1,10,40,,
#XS Ineff= 2 , 0
               0   26.49      10           26.49
Permanent Ineff=
       F       F
Bank Sta=0,10
XS Rating Curve= 0
Exp/Cntr=.3,.1

Type RM Length L Ch R = 1 ,10.48   ,1,1,1
#Sta/Elev= 10
   -12.5   25.31    -2.5   25.31    -1.1   26.41       0   26.41       3   24.91
       7   24.91      10   26.41    12.4   26.41    14.6   24.61    24.6   24.61
#Mann= 3 , 0 , 0
   -12.5    .035       0       0    .035       0      10    .035       0
Levee=-1,0,40,-1,10,40,,
#XS Ineff= 2 , 0
               0   26.41      10           26.41
Permanent Ineff=
       F       F
Bank Sta=0,10
XS Rating Curve= 0
Exp/Cntr=.3,.1

Type RM Length L Ch R = 1 ,10.047  ,47,47,47
#Sta/Elev= 12
   -12.5   25.31    -2.5   25.31    -1.1   26.41       0   26.41       3   24.91
       3   23.91       7   23.91       7   24.91      10   26.41    12.4   26.41
    14.6   24.61    24.6   24.61
#Mann= 3 , 0 , 0
   -12.5    .035       0       0    .035       0      10    .035       0
Levee=-1,0,40,-1,10,40,,
#XS Ineff= 2 , 0
               0   26.41      10           26.41
Permanent Ineff=
       F       F
Bank Sta=0,10
XS Rating Curve= 0
Exp/Cntr=.3,.1

Type RM Length L Ch R = 1 ,10      ,50,50,50
#Sta/Elev= 12
   -12.4   24.38    -2.4   24.38     -.9   25.58       0   25.58     2.6   24.28
     2.8   23.68       6   23.68     6.3   24.18     9.3   25.68    11.7   25.68
    14.7   23.98    24.7   23.98
#Mann= 3 , 0 , 0
   -12.4    .035       0       0    .035       0     9.3    .035       0
Levee=-1,0,40,-1,9.3,40,,
#XS Ineff= 2 , 0
               0   25.58     9.3           25.68
Permanent Ineff=
       F       F
Bank Sta=0,9.3
XS Rating Curve= 0
Exp/Cntr=.3,.1

Type RM Length L Ch R = 1 ,9       ,32,32,32
#Sta/Elev= 10
   -12.3   23.79    -2.3   23.79      -1   24.99       0   24.99     2.5   23.19
     6.5   23.19     9.2   24.99    11.8   24.99    13.8   23.39    23.8   23.39
#Mann= 3 , 0 , 0
   -12.3    .035       0       0    .035       0     9.2    .035       0
Levee=-1,0,30,-1,9.2,30,,
#XS Ineff= 2 , 0
               0   24.99     9.2           24.99
Permanent Ineff=
       F       F
Bank Sta=0,9.2
XS Rating Curve= 0
Exp/Cntr=.3,.1

Type RM Length L Ch R = 1 ,8.018   ,1,1,1
#Sta/Elev= 10
   -12.3   23.53    -2.3   23.53      -1   24.73       0   24.73     2.5   23.13
     6.5   23.13     9.2   24.73    11.8   24.73    13.8   23.13    23.8   23.13
#Mann= 3 , 0 , 0
   -12.3    .035       0       0    .035       0     9.2    .035       0
Levee=-1,0,30,-1,9.2,30,,
#XS Ineff= 2 , 0
               0   24.73     9.2           24.73
Permanent Ineff=
       F       F
Bank Sta=0,9.2
XS Rating Curve= 0
Exp/Cntr=.3,.1

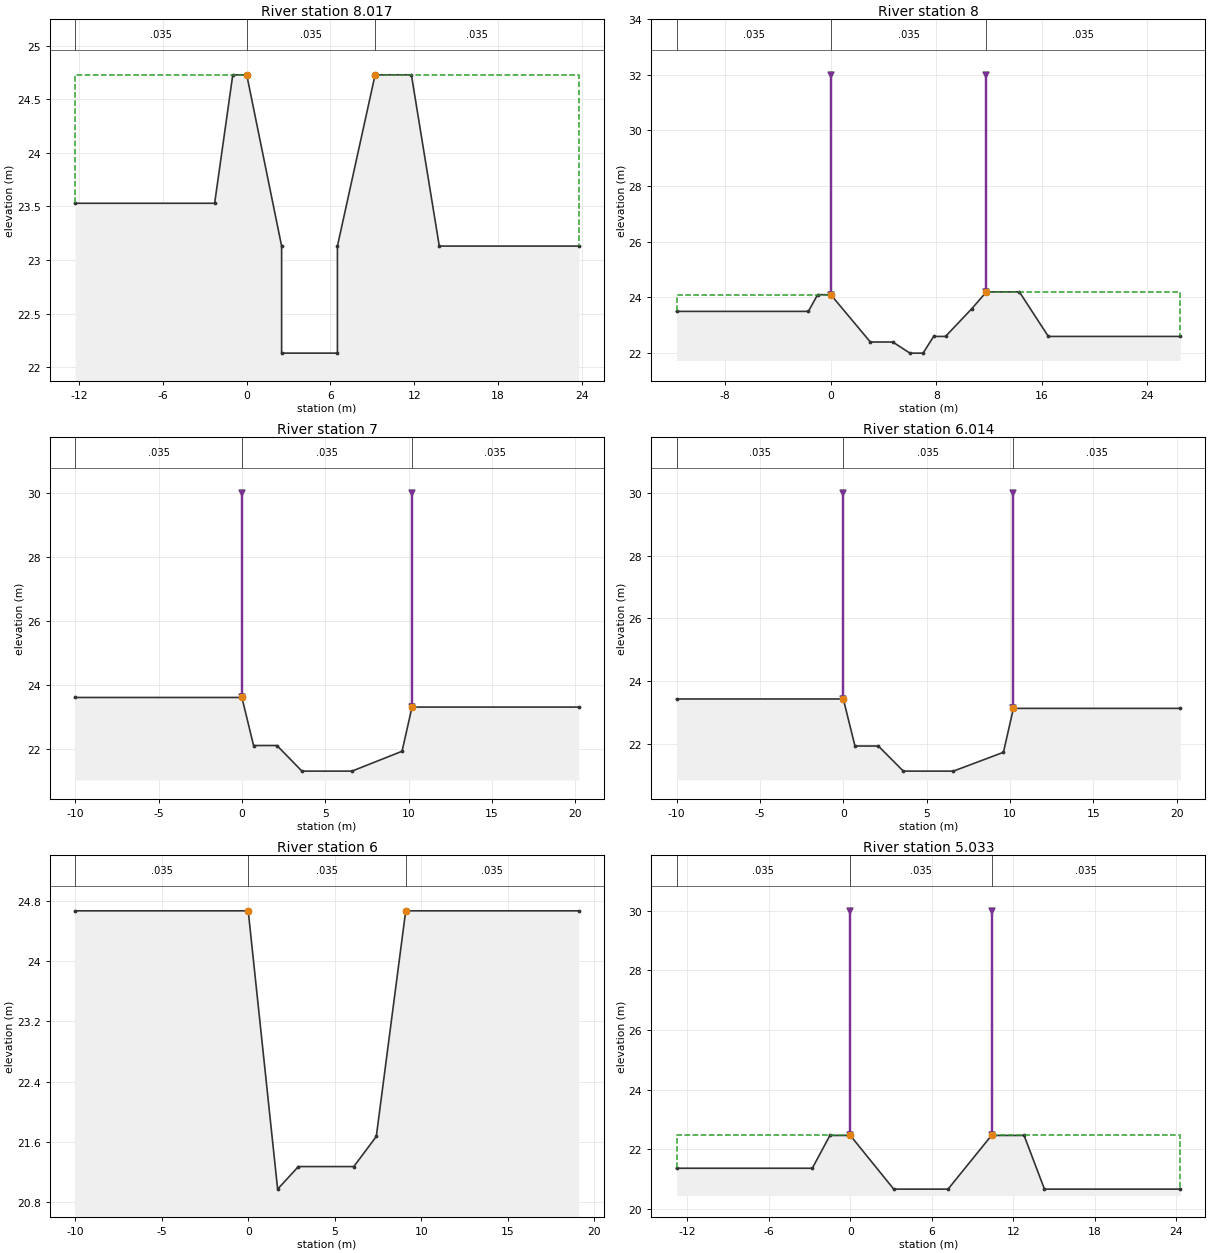
Type RM Length L Ch R = 1 ,8.017   ,17,17,17
#Sta/Elev= 12
   -12.3   23.53    -2.3   23.53      -1   24.73       0   24.73     2.5   23.13
     2.5   22.13     6.5   22.13     6.5   23.13     9.2   24.73    11.8   24.73
    13.8   23.13    23.8   23.13
#Mann= 3 , 0 , 0
   -12.3    .035       0       0    .035       0     9.2    .035       0
#XS Ineff= 2 , 0
               0   24.73     9.2           24.73
Permanent Ineff=
       F       F
Bank Sta=0,9.2
XS Rating Curve= 0
Exp/Cntr=.3,.1

Type RM Length L Ch R = 1 ,8       ,50,50,50
#Sta/Elev= 15
   -11.7    23.5    -1.7    23.5      -1    24.1       0    24.1       3    22.4
     4.7    22.4       6      22       7      22     7.8    22.6     8.7    22.6
    10.7    23.6    11.8    24.2    14.3    24.2    16.5    22.6    26.5    22.6
#Mann= 3 , 0 , 0
   -11.7    .035       0       0    .035       0    11.8    .035       0
Levee=-1,0,32,-1,11.8,32,,
#XS Ineff= 2 , 0
               0    24.1    11.8            24.2
Permanent Ineff=
       F       F
Bank Sta=0,11.8
XS Rating Curve= 0
Exp/Cntr=.3,.1

Type RM Length L Ch R = 1 ,7       ,36,36,36
#Sta/Elev= 9
     -10   23.61       0   23.61      .7   22.11     2.1   22.11     3.6   21.31
     6.6   21.31     9.6   21.93    10.2   23.31    20.2   23.31
#Mann= 3 , 0 , 0
     -10    .035       0       0    .035       0    10.2    .035       0
Levee=-1,0,30,-1,10.2,30,,
#XS Ineff= 2 , 0
               0   23.61    10.2           23.31
Permanent Ineff=
       F       F
Bank Sta=0,10.2
XS Rating Curve= 0
Exp/Cntr=.3,.1

Type RM Length L Ch R = 1 ,6.014   ,14,14,14
#Sta/Elev= 9
     -10   23.43       0   23.43      .7   21.93     2.1   21.93     3.6   21.13
     6.6   21.13     9.6   21.73    10.2   23.13    20.2   23.13
#Mann= 3 , 0 , 0
     -10    .035       0       0    .035       0    10.2    .035       0
Levee=-1,0,30,-1,10.2,30,,
#XS Ineff= 2 , 0
               0   23.43    10.2           23.13
Permanent Ineff=
       F       F
Bank Sta=0,10.2
XS Rating Curve= 0
Exp/Cntr=.3,.1

Type RM Length L Ch R = 1 ,6       ,17,17,17
#Sta/Elev= 8
     -10   24.67       0   24.67     1.7   20.97     2.9   21.27     6.1   21.27
     7.4   21.67     9.1   24.67    19.1   24.67
#Mann= 3 , 0 , 0
     -10    .035       0       0    .035       0     9.1    .035       0
#XS Ineff= 2 , 0
               0   24.67     9.1           24.67
Permanent Ineff=
       F       F
Bank Sta=0,9.1
XS Rating Curve= 0
Exp/Cntr=.3,.1

Type RM Length L Ch R = 1 ,5.033   ,1,1,1
#Sta/Elev= 10
   -12.8   21.37    -2.8   21.37    -1.5   22.47       0   22.47     3.2   20.67
     7.2   20.67    10.4   22.47    12.8   22.47    14.3   20.67    24.3   20.67
#Mann= 3 , 0 , 0
   -12.8    .035       0       0    .035       0    10.4    .035       0
Levee=-1,0,30,-1,10.4,30,,
#XS Ineff= 2 , 0
               0   22.47    10.4           22.47
Permanent Ineff=
       F       F
Bank Sta=0,10.4
XS Rating Curve= 0
Exp/Cntr=.3,.1

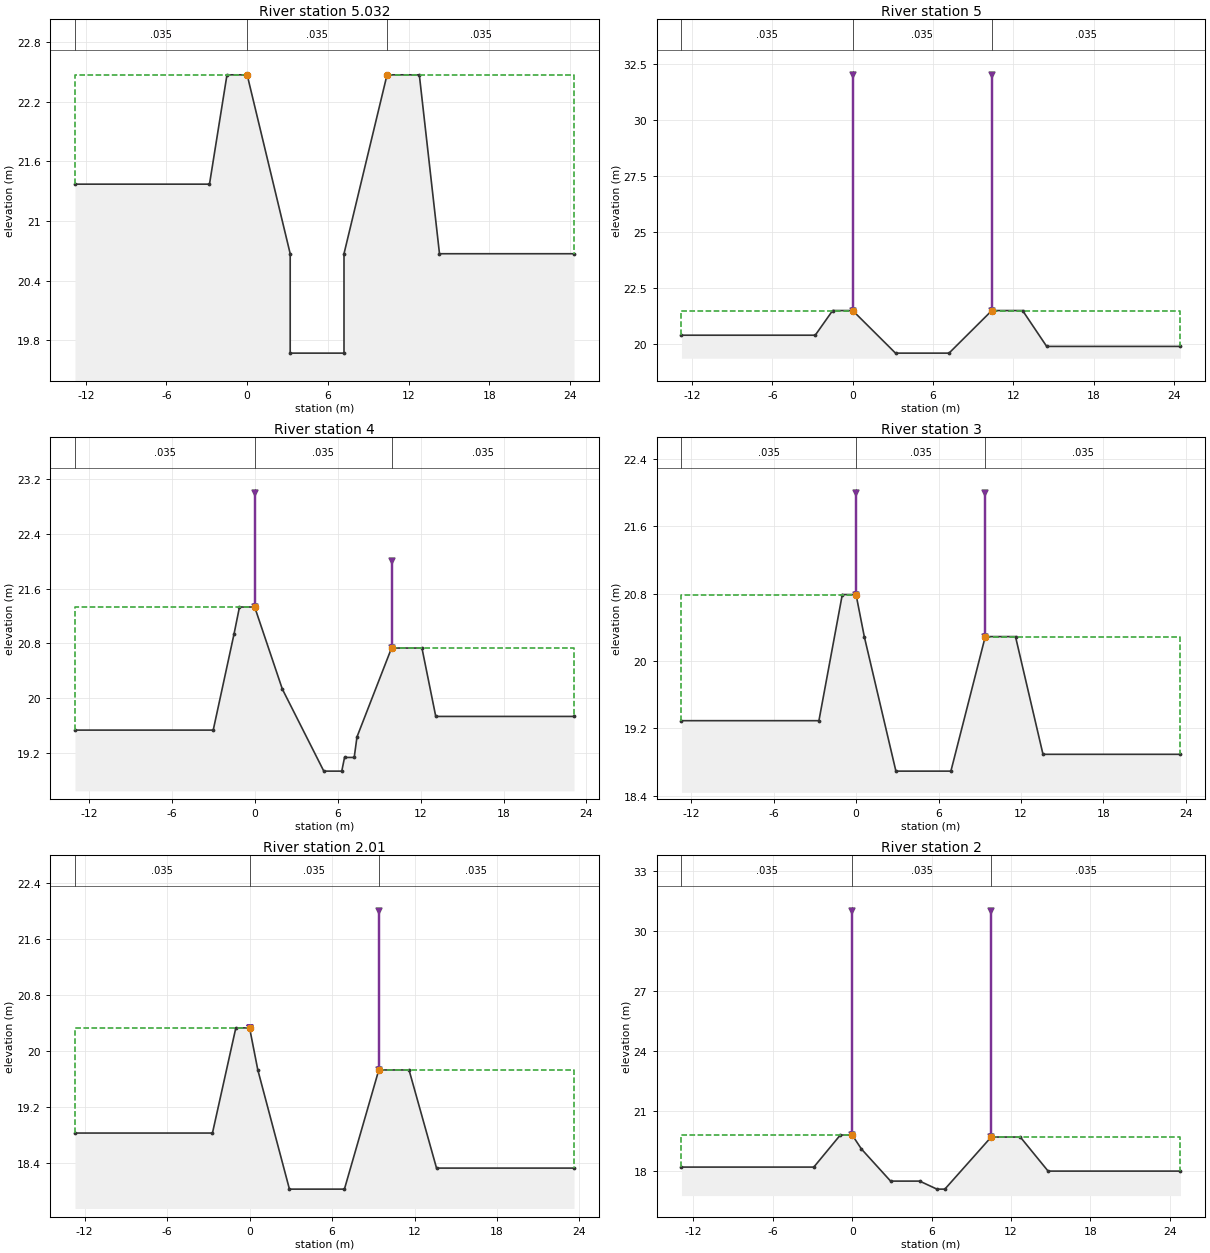
Type RM Length L Ch R = 1 ,5.032   ,32,32,32
#Sta/Elev= 12
   -12.8   21.37    -2.8   21.37    -1.5   22.47       0   22.47     3.2   20.67
     3.2   19.67     7.2   19.67     7.2   20.67    10.4   22.47    12.8   22.47
    14.3   20.67    24.3   20.67
#Mann= 3 , 0 , 0
   -12.8    .035       0       0    .035       0    10.4    .035       0
#XS Ineff= 2 , 0
               0   22.47    10.4           22.47
Permanent Ineff=
       F       F
Bank Sta=0,10.4
XS Rating Curve= 0
Exp/Cntr=.3,.1

Type RM Length L Ch R = 1 ,5       ,50,50,50
#Sta/Elev= 10
   -12.8   20.38    -2.8   20.38    -1.5   21.48       0   21.48     3.2   19.58
     7.2   19.58    10.4   21.48    12.7   21.48    14.5   19.88    24.5   19.88
#Mann= 3 , 0 , 0
   -12.8    .035       0       0    .035       0    10.4    .035       0
Levee=-1,0,32,-1,10.4,32,,
#XS Ineff= 2 , 0
               0   21.48    10.4           21.48
Permanent Ineff=
       F       F
Bank Sta=0,10.4
XS Rating Curve= 0
Exp/Cntr=.3,.1

Type RM Length L Ch R = 1 ,4       ,50,50,50
#Sta/Elev= 15
     -13   19.53      -3   19.53    -1.5   20.93    -1.1   21.33       0   21.33
       2   20.13       5   18.93     6.3   18.93     6.5   19.13     7.2   19.13
     7.4   19.43     9.9   20.73    12.1   20.73    13.1   19.73    23.1   19.73
#Mann= 3 , 0 , 0
     -13    .035       0       0    .035       0     9.9    .035       0
Levee=-1,0,23,-1,9.9,22,,
#XS Ineff= 2 , 0
               0   21.33     9.9           20.73
Permanent Ineff=
       F       F
Bank Sta=0,9.9
XS Rating Curve= 0
Exp/Cntr=.3,.1

Type RM Length L Ch R = 1 ,3       ,40,40,40
#Sta/Elev= 11
   -12.7   19.29    -2.7   19.29      -1   20.79       0   20.79      .6   20.29
     2.9   18.69     6.9   18.69     9.4   20.29    11.6   20.29    13.6   18.89
    23.6   18.89
#Mann= 3 , 0 , 0
   -12.7    .035       0       0    .035       0     9.4    .035       0
Levee=-1,0,22,-1,9.4,22,,
#XS Ineff= 2 , 0
               0   20.79     9.4           20.29
Permanent Ineff=
       F       F
Bank Sta=0,9.4
XS Rating Curve= 0
Exp/Cntr=.3,.1

Type RM Length L Ch R = 1 ,2.01    ,10,10,10
#Sta/Elev= 11
   -12.7   18.83    -2.7   18.83      -1   20.33       0   20.33      .6   19.73
     2.9   18.03     6.9   18.03     9.4   19.73    11.6   19.73    13.6   18.33
    23.6   18.33
#Mann= 3 , 0 , 0
   -12.7    .035       0       0    .035       0     9.4    .035       0
Levee=-1,0,20.33,-1,9.4,22,,
#XS Ineff= 2 , 0
               0   20.33     9.4           19.73
Permanent Ineff=
       F       F
Bank Sta=0,9.4
XS Rating Curve= 0
Exp/Cntr=.3,.1

Type RM Length L Ch R = 1 ,2       ,50,50,50
#Sta/Elev= 13
   -12.9   18.21    -2.9   18.21     -.9   19.81       0   19.81      .7   19.11
     2.9   17.51     5.1   17.51     6.4   17.11       7   17.11    10.5   19.71
    12.7   19.71    14.8   18.01    24.8   18.01
#Mann= 3 , 0 , 0
   -12.9    .035       0       0    .035       0    10.5    .035       0
Levee=-1,0,31,-1,10.5,31,,
#XS Ineff= 2 , 0
               0   19.81    10.5           19.71
Permanent Ineff=
       F       F
Bank Sta=0,10.5
XS Rating Curve= 0
Exp/Cntr=.3,.1

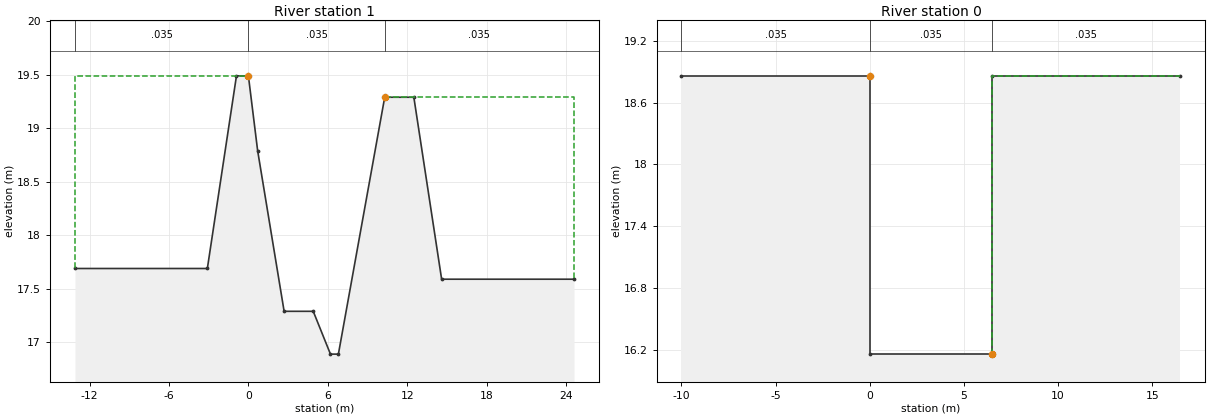
Type RM Length L Ch R = 1 ,1       ,50,50,50
#Sta/Elev= 13
   -13.1   17.69    -3.1   17.69     -.9   19.49       0   19.49      .7   18.79
     2.7   17.29     4.9   17.29     6.2   16.89     6.8   16.89    10.3   19.29
    12.5   19.29    14.6   17.59    24.6   17.59
#Mann= 3 , 0 , 0
   -13.1    .035       0       0    .035       0    10.3    .035       0
#XS Ineff= 2 , 0
               0   19.49    10.3           19.29
Permanent Ineff=
       F       F
Bank Sta=0,10.3
XS Rating Curve= 0
Exp/Cntr=.3,.1

Type RM Length L Ch R = 1 ,0       ,0,0,0
#Sta/Elev= 6
     -10   18.86       0   18.86       0   16.16     6.5   16.16     6.5   18.86
    16.5   18.86
#Mann= 3 , 0 , 0
     -10    .035       0       0    .035       0     6.5    .035       0
#XS Ineff= 2 , 0
               0   18.86     6.5           18.86
Permanent Ineff=
       F       F
Bank Sta=0,6.5
XS Rating Curve= 0
Exp/Cntr=.3,.1

Chan Stop Cuts=-1