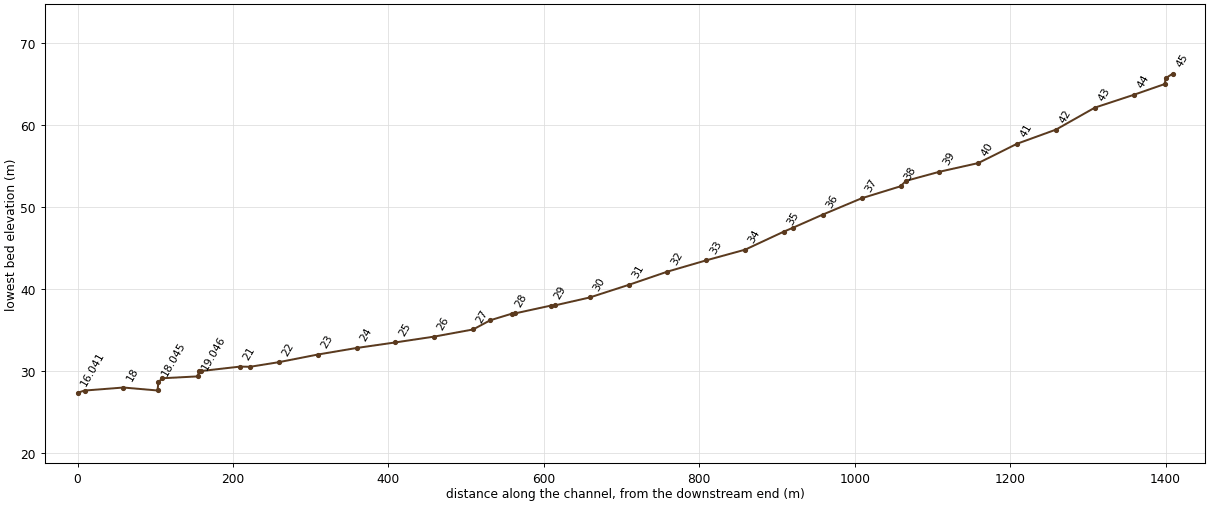
--- mkc.prj (project) ---

Proj Title=magang-ch
Current Plan=p01
Default Exp/Contr=.3,.1
SI Units
Geom File=g01
Flow File=f01
Plan File=p01
Y Axis Title=Elevation
X Axis Title(PF)=Main Channel Distance
X Axis Title(XS)=Station
BEGIN DESCRIPTION:
           BACK WATER COMPUTATION
      APPLICATION OF HEC-2 BY Samju Construction Engineering
      magang-ch: 10,20,30,50,80 yr
END DESCRIPTION:
DSS Export Rating Curves= 0
DSS Export Rating Curve Sorted= 0
DSS Export Volume Flow Curves= 0
DXF OffsetX= 0
DXF OffsetY= 0
DXF ScaleX= 1
DXF ScaleY= 10

--- mkc.p01 (plan) ---

Plan Title=Imported Plan 01
Version=Version 3.0.1  Mar 2001
Short Identifier=Imported Pla
Geom File=g01
Flow File=f01
Subcritical Flow
K Sum by GR= 0
Std Step Tol= 0.003
Critical Tol= 0.003
Num of Std Step Trials= 20
Max Error Tol= 0.1
Flow Tol Ratio= 0.001
Split Flow NTrial= 30
Split Flow Tol= 0.02
Split Flow Ratio= 0.02
Log Output Level= 0
Friction Slope Method= 1
Unsteady Friction Slope Method= 2
Parabolic Critical Depth
Global Vel Dist= 0 , 0 , 0
Global Log Level= 0
CheckData=True
Encroach Param=-1 ,0,0, 0
Computation Interval=1HOUR
Output Interval=1HOUR
Run HTab= 0
Run UNet= 0
Run PostProcess= 0
UNET Theta= 1
UNET ZTol= 0.02
UNET ZSATol= 0.1
UNET MxIter= 20
UNET MaxInSteps= 20
UNET DtIC= 0
UNET DtMin= 0
UNET MaxCRTS= 20
UNET WFStab= 2
UNET SFStab= 1
UNET WFX= 1
UNET SFX= 1
UNET Convert EG Bridges=-1
UNET Use Existing IB Tables=-1
Instantaneous Interval=1HOUR
Write IC File= 0
Write Velocity= 0
Write Detailed= 0

--- mkc.f01 (steady flow) ---

Flow Title=Imported Flow 01
Version=Version 3.0.1  Mar 2001
Number of Profiles= 5
Profile Names=10yr,20yr,30yr,50yr,80yr
River Rch & RM=RIVER-1,Reach-1         ,45
   11.05   12.17   12.83   13.65   14.41
River Rch & RM=RIVER-1,Reach-1         ,28
   19.99   22.03   23.22   24.73   26.11
Boundary for River Rch & Prof#=RIVER-1,Reach-1         , 1
Up Type= 0
Dn Type= 3
Dn Slope=.021
Boundary for River Rch & Prof#=RIVER-1,Reach-1         , 2
Up Type= 0
Dn Type= 3
Dn Slope=.021
Boundary for River Rch & Prof#=RIVER-1,Reach-1         , 3
Up Type= 0
Dn Type= 3
Dn Slope=.021
Boundary for River Rch & Prof#=RIVER-1,Reach-1         , 4
Up Type= 0
Dn Type= 3
Dn Slope=.021
Boundary for River Rch & Prof#=RIVER-1,Reach-1         , 5
Up Type= 0
Dn Type= 3
Dn Slope=.021
DSS Import GetInterval= 0
DSS Import GetPeak= 0
DSS Import FillOption= 0

--- mkc.g01 (geometry) ---

Geom Title=Imported Geom 01
Version=Version 3.0.1  Mar 2001

River Reach=RIVER-1         ,Reach-1
Reach XY= 2
              .5             .95              .5             .05

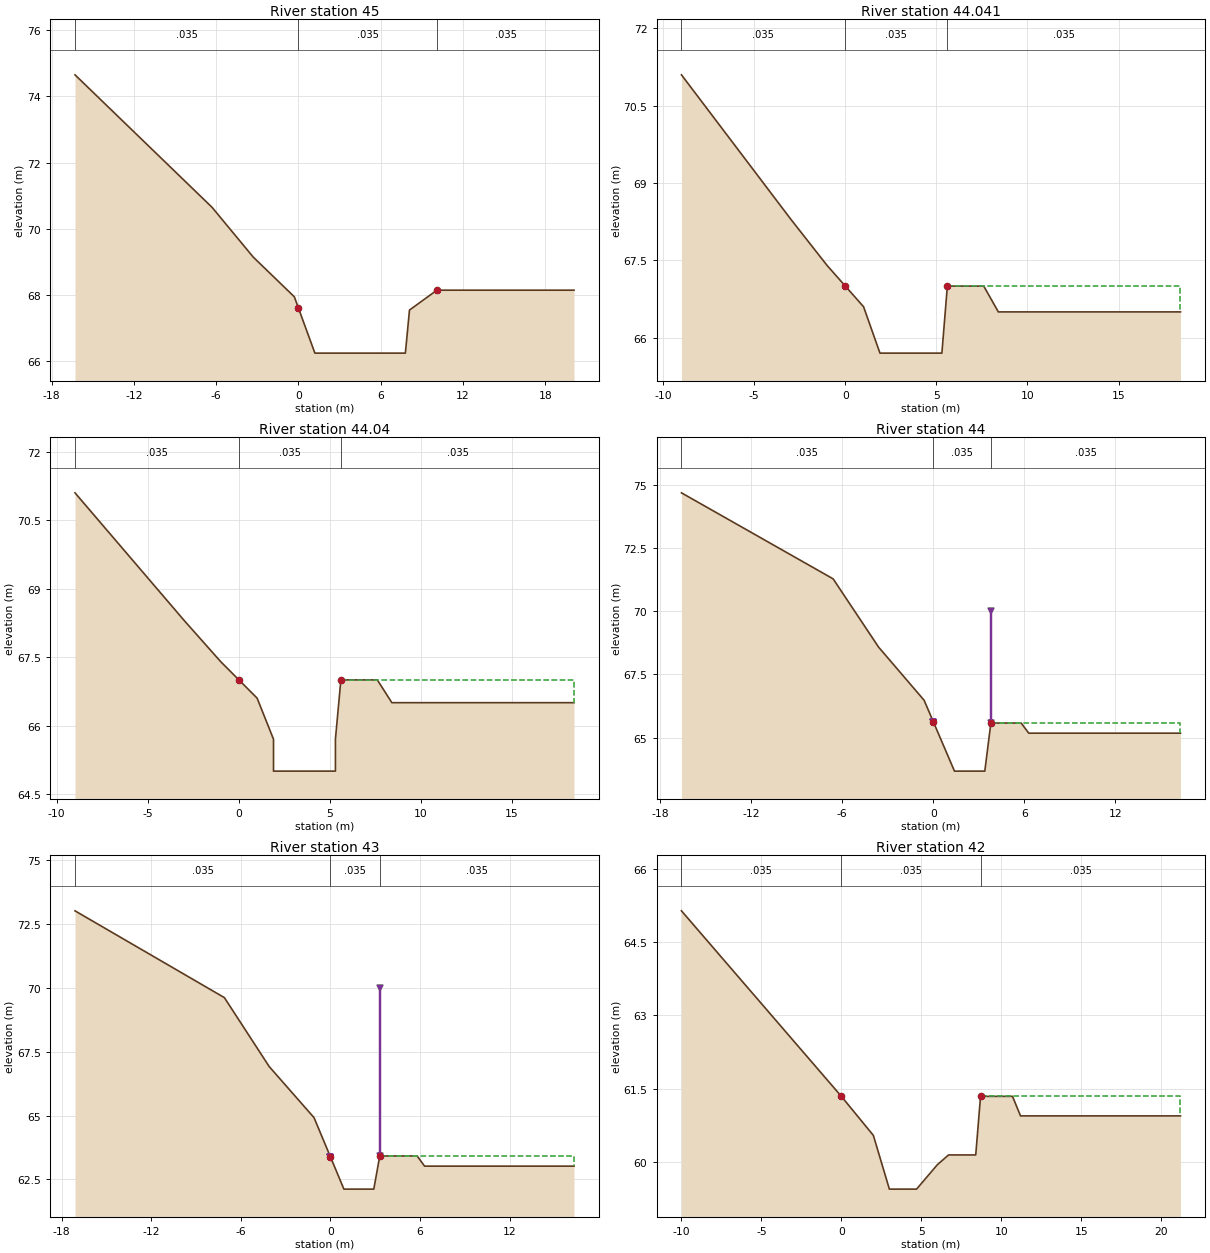
Type RM Length L Ch R = 1 ,45      ,9,9,9
#Sta/Elev= 11
   -16.3   74.65   -11.3   72.65    -6.3   70.65    -3.3   69.15     -.3   67.95
       0   67.61     1.2   66.25     7.8   66.25     8.1   67.55    10.1   68.15
    20.1   68.15
#Mann= 3 , 0 , 0
   -16.3    .035       0       0    .035       0    10.1    .035       0
#XS Ineff= 2 , 0
               0   67.61    10.1           68.15
Permanent Ineff=
       F       F
Bank Sta=0,10.1
XS Rating Curve= 0
Exp/Cntr=.3,.1

Type RM Length L Ch R = 1 ,44.041  ,1,1,1
#Sta/Elev= 12
      -9    71.1      -6    69.7      -3    68.3      -1    67.4       0      67
       1    66.6     1.9    65.7     5.3    65.7     5.6      67     7.6      67
     8.4    66.5    18.4    66.5
#Mann= 3 , 0 , 0
      -9    .035       0       0    .035       0     5.6    .035       0
#XS Ineff= 2 , 0
               0      67     5.6              67
Permanent Ineff=
       F       F
Bank Sta=0,5.6
XS Rating Curve= 0
Exp/Cntr=.3,.1

Type RM Length L Ch R = 1 ,44.04   ,40,40,40
#Sta/Elev= 14
      -9    71.1      -6    69.7      -3    68.3      -1    67.4       0      67
       1    66.6     1.9    65.7     1.9      65     5.3      65     5.3    65.7
     5.6      67     7.6      67     8.4    66.5    18.4    66.5
#Mann= 3 , 0 , 0
      -9    .035       0       0    .035       0     5.6    .035       0
#XS Ineff= 2 , 0
               0      67     5.6              67
Permanent Ineff=
       F       F
Bank Sta=0,5.6
XS Rating Curve= 0
Exp/Cntr=.3,.1

Type RM Length L Ch R = 1 ,44      ,50,50,50
#Sta/Elev= 12
   -16.6   74.68   -11.6   72.98    -6.6   71.28    -3.6   68.58     -.6   66.48
       0   65.64     1.4   63.68     3.4   63.68     3.8   65.58     5.8   65.58
     6.3   65.18    16.3   65.18
#Mann= 3 , 0 , 0
   -16.6    .035       0       0    .035       0     3.8    .035       0
Levee=-1,0,65.64,-1,3.8,70,,
#XS Ineff= 2 , 0
               0   65.64     3.8           65.58
Permanent Ineff=
       F       F
Bank Sta=0,3.8
XS Rating Curve= 0
Exp/Cntr=.3,.1

Type RM Length L Ch R = 1 ,43      ,50,50,50
#Sta/Elev= 12
   -17.1   73.02   -12.1   71.32    -7.1   69.62    -4.1   66.92    -1.1   64.92
       0   63.38      .9   62.12     2.9   62.12     3.3   63.42     5.8   63.42
     6.3   63.02    16.3   63.02
#Mann= 3 , 0 , 0
   -17.1    .035       0       0    .035       0     3.3    .035       0
Levee=-1,0,63.38,-1,3.3,70,,
#XS Ineff= 2 , 0
               0   63.38     3.3           63.42
Permanent Ineff=
       F       F
Bank Sta=0,3.3
XS Rating Curve= 0
Exp/Cntr=.3,.1

Type RM Length L Ch R = 1 ,42      ,50,50,50
#Sta/Elev= 13
     -10   65.14      -5   63.24       0   61.34       2   60.54       3   59.44
     4.7   59.44       6   59.94     6.7   60.14     8.4   60.14     8.7   61.34
    10.7   61.34    11.2   60.94    21.2   60.94
#Mann= 3 , 0 , 0
     -10    .035       0       0    .035       0     8.7    .035       0
#XS Ineff= 2 , 0
               0   61.34     8.7           61.34
Permanent Ineff=
       F       F
Bank Sta=0,8.7
XS Rating Curve= 0
Exp/Cntr=.3,.1

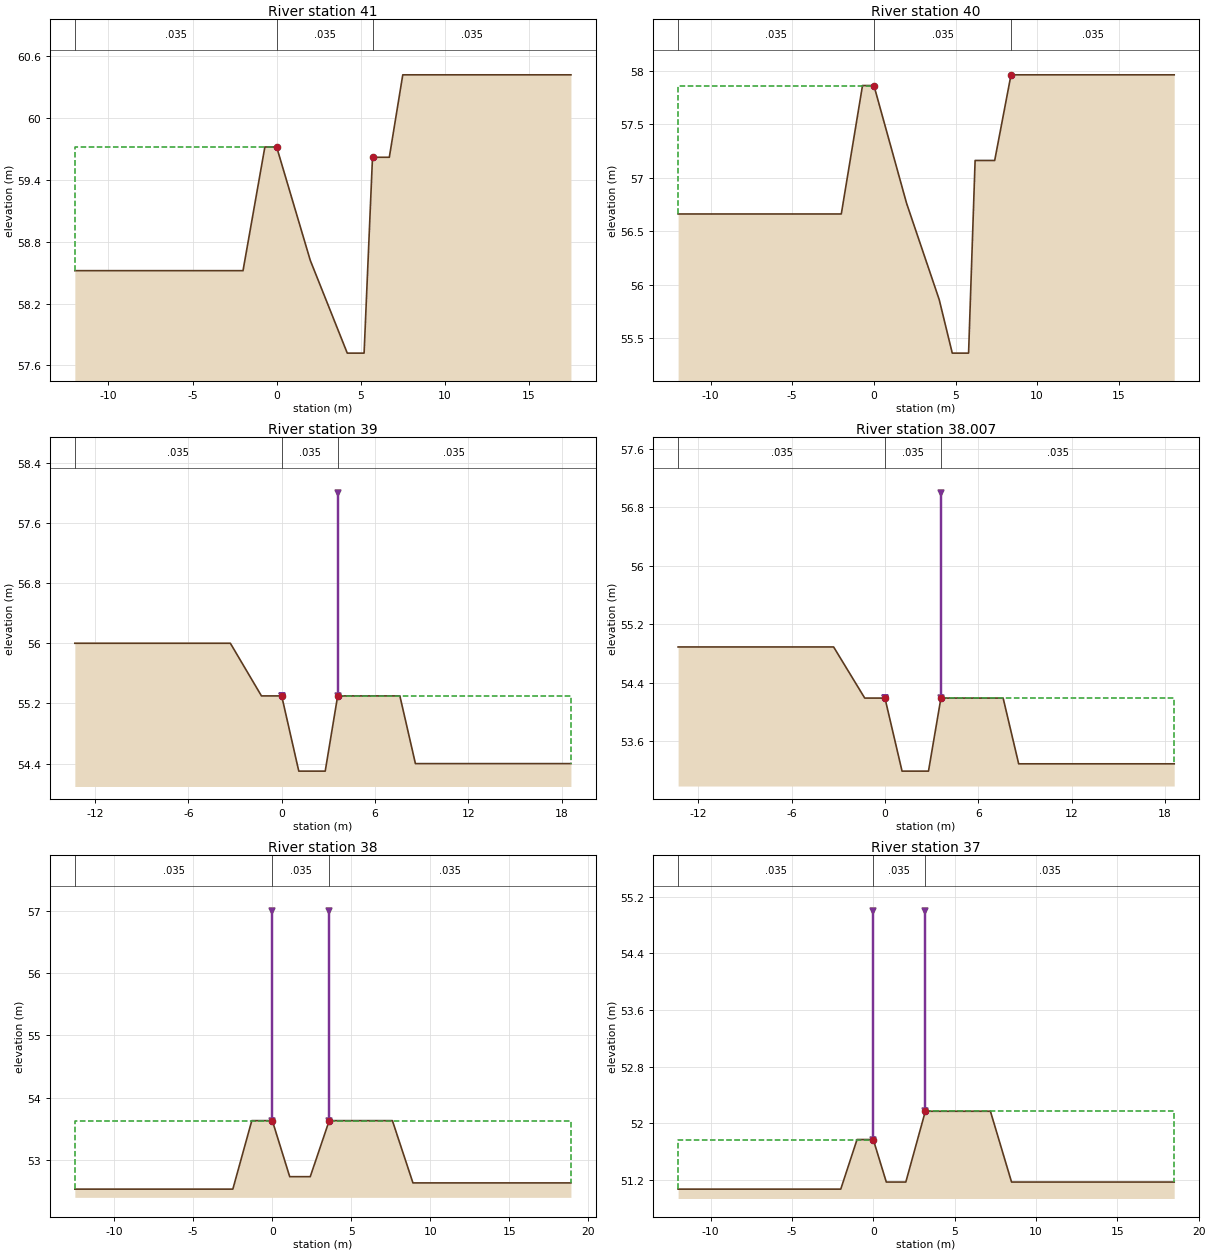
Type RM Length L Ch R = 1 ,41      ,50,50,50
#Sta/Elev= 11
     -12   58.52      -2   58.52     -.7   59.72       0   59.72       2   58.62
     4.2   57.72     5.2   57.72     5.7   59.62     6.7   59.62     7.5   60.42
    17.5   60.42
#Mann= 3 , 0 , 0
     -12    .035       0       0    .035       0     5.7    .035       0
#XS Ineff= 2 , 0
               0   59.72     5.7           59.62
Permanent Ineff=
       F       F
Bank Sta=0,5.7
XS Rating Curve= 0
Exp/Cntr=.3,.1

Type RM Length L Ch R = 1 ,40      ,50,50,50
#Sta/Elev= 12
     -12   56.66      -2   56.66     -.7   57.86       0   57.86       2   56.76
       4   55.86     4.8   55.36     5.8   55.36     6.2   57.16     7.4   57.16
     8.4   57.96    18.4   57.96
#Mann= 3 , 0 , 0
     -12    .035       0       0    .035       0     8.4    .035       0
#XS Ineff= 2 , 0
               0   57.86     8.4           57.96
Permanent Ineff=
       F       F
Bank Sta=0,8.4
XS Rating Curve= 0
Exp/Cntr=.3,.1

Type RM Length L Ch R = 1 ,39      ,43,43,43
#Sta/Elev= 10
   -13.3      56    -3.3      56    -1.3    55.3       0    55.3     1.1    54.3
     2.8    54.3     3.6    55.3     7.6    55.3     8.6    54.4    18.6    54.4
#Mann= 3 , 0 , 0
   -13.3    .035       0       0    .035       0     3.6    .035       0
Levee=-1,0,55.3,-1,3.6,58,,
#XS Ineff= 2 , 0
               0    55.3     3.6            55.3
Permanent Ineff=
       F       F
Bank Sta=0,3.6
XS Rating Curve= 0
Exp/Cntr=.3,.1

Type RM Length L Ch R = 1 ,38.007  ,7,7,7
#Sta/Elev= 10
   -13.3   54.89    -3.3   54.89    -1.3   54.19       0   54.19     1.1   53.19
     2.8   53.19     3.6   54.19     7.6   54.19     8.6   53.29    18.6   53.29
#Mann= 3 , 0 , 0
   -13.3    .035       0       0    .035       0     3.6    .035       0
Levee=-1,0,54.19,-1,3.6,57,,
#XS Ineff= 2 , 0
               0   54.19     3.6           54.19
Permanent Ineff=
       F       F
Bank Sta=0,3.6
XS Rating Curve= 0
Exp/Cntr=.3,.1

Type RM Length L Ch R = 1 ,38      ,50,50,50
#Sta/Elev= 10
   -12.5   52.53    -2.5   52.53    -1.3   53.63       0   53.63     1.1   52.73
     2.4   52.73     3.6   53.63     7.6   53.63     8.9   52.63    18.9   52.63
#Mann= 3 , 0 , 0
   -12.5    .035       0       0    .035       0     3.6    .035       0
Levee=-1,0,57,-1,3.6,57,,
#XS Ineff= 2 , 0
               0   53.63     3.6           53.63
Permanent Ineff=
       F       F
Bank Sta=0,3.6
XS Rating Curve= 0
Exp/Cntr=.3,.1

Type RM Length L Ch R = 1 ,37      ,50,50,50
#Sta/Elev= 10
     -12   51.07      -2   51.07      -1   51.77       0   51.77      .8   51.17
       2   51.17     3.2   52.17     7.2   52.17     8.5   51.17    18.5   51.17
#Mann= 3 , 0 , 0
     -12    .035       0       0    .035       0     3.2    .035       0
Levee=-1,0,55,-1,3.2,55,,
#XS Ineff= 2 , 0
               0   51.77     3.2           52.17
Permanent Ineff=
       F       F
Bank Sta=0,3.2
XS Rating Curve= 0
Exp/Cntr=.3,.1

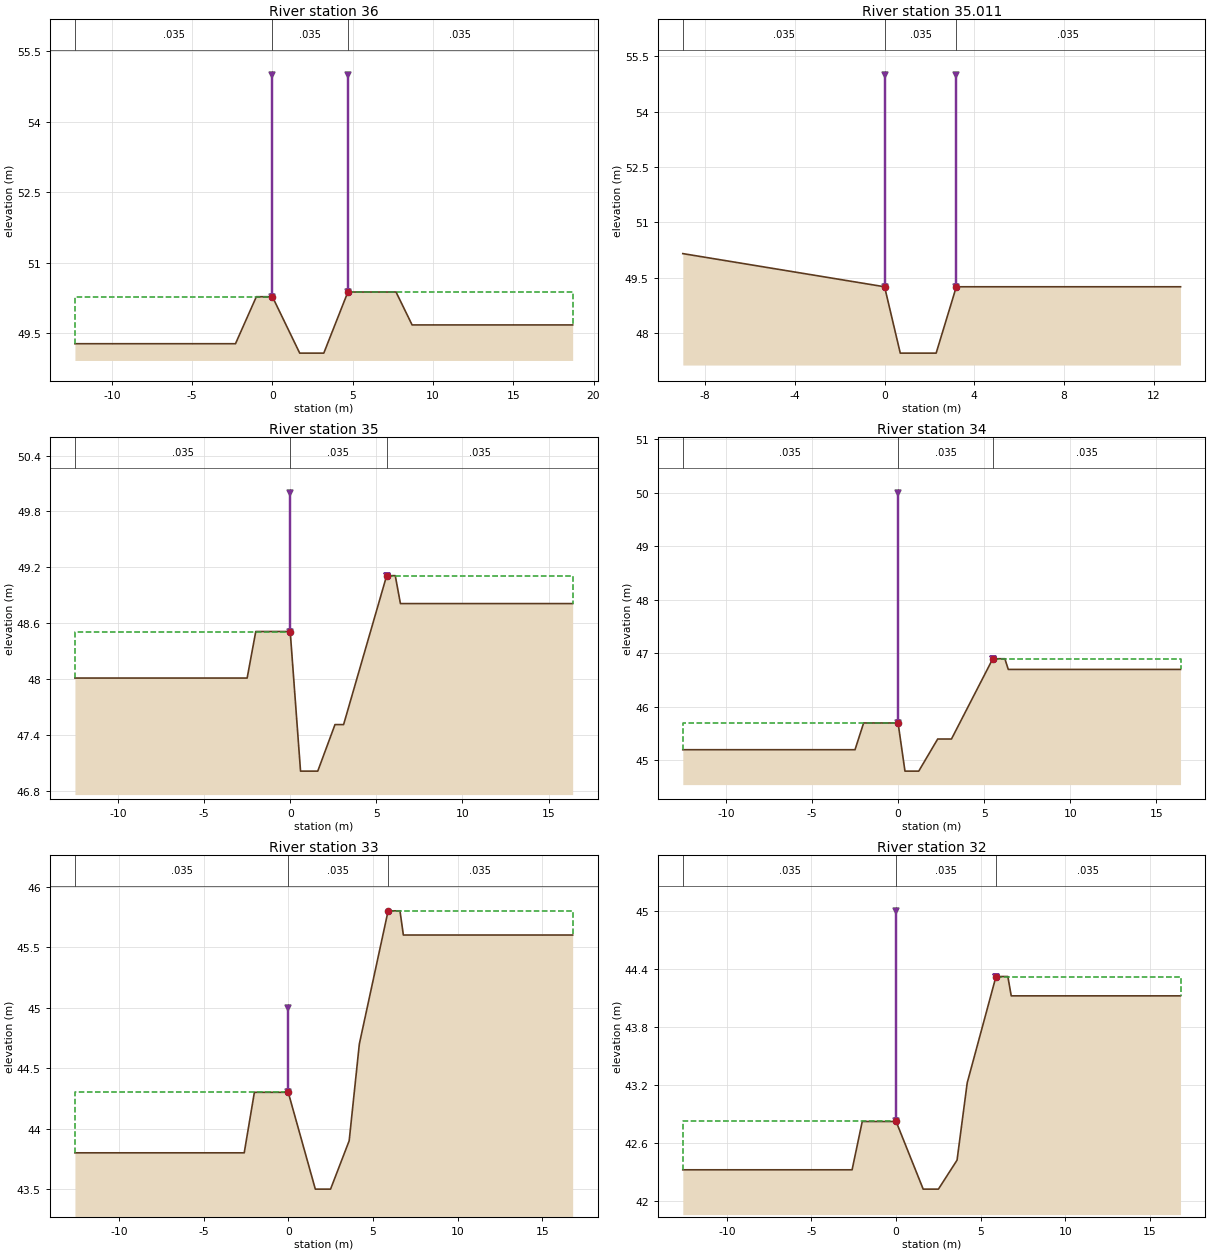
Type RM Length L Ch R = 1 ,36      ,39,39,39
#Sta/Elev= 10
   -12.3   49.28    -2.3   49.28      -1   50.28       0   50.28     1.7   49.08
     3.2   49.08     4.7   50.38     7.7   50.38     8.7   49.68    18.7   49.68
#Mann= 3 , 0 , 0
   -12.3    .035       0       0    .035       0     4.7    .035       0
Levee=-1,0,55,-1,4.7,55,,
#XS Ineff= 2 , 0
               0   50.28     4.7           50.38
Permanent Ineff=
       F       F
Bank Sta=0,4.7
XS Rating Curve= 0
Exp/Cntr=.3,.1

Type RM Length L Ch R = 1 ,35.011  ,11,11,11
#Sta/Elev= 8
      -9   50.15      -6   49.85      -3   49.55       0   49.25      .7   47.45
     2.3   47.45     3.2   49.25    13.2   49.25
#Mann= 3 , 0 , 0
      -9    .035       0       0    .035       0     3.2    .035       0
Levee=-1,0,55,-1,3.2,55,,
#XS Ineff= 2 , 0
               0   49.25     3.2           49.25
Permanent Ineff=
       F       F
Bank Sta=0,3.2
XS Rating Curve= 0
Exp/Cntr=.3,.1

Type RM Length L Ch R = 1 ,35      ,50,50,50
#Sta/Elev= 12
   -12.5   48.01    -2.5   48.01      -2   48.51       0   48.51      .6   47.01
     1.6   47.01     2.6   47.51     3.1   47.51     5.6   49.11     6.1   49.11
     6.4   48.81    16.4   48.81
#Mann= 3 , 0 , 0
   -12.5    .035       0       0    .035       0     5.6    .035       0
Levee=-1,0,50,-1,5.6,49.11,,
#XS Ineff= 2 , 0
               0   48.51     5.6           49.11
Permanent Ineff=
       F       F
Bank Sta=0,5.6
XS Rating Curve= 0
Exp/Cntr=.3,.1

Type RM Length L Ch R = 1 ,34      ,50,50,50
#Sta/Elev= 12
   -12.5    45.2    -2.5    45.2      -2    45.7       0    45.7      .4    44.8
     1.2    44.8     2.3    45.4     3.1    45.4     5.5    46.9     6.2    46.9
     6.4    46.7    16.4    46.7
#Mann= 3 , 0 , 0
   -12.5    .035       0       0    .035       0     5.5    .035       0
Levee=-1,0,50,-1,5.5,46.9,,
#XS Ineff= 2 , 0
               0    45.7     5.5            46.9
Permanent Ineff=
       F       F
Bank Sta=0,5.5
XS Rating Curve= 0
Exp/Cntr=.3,.1

Type RM Length L Ch R = 1 ,33      ,50,50,50
#Sta/Elev= 12
   -12.6    43.8    -2.6    43.8      -2    44.3       0    44.3     1.6    43.5
     2.5    43.5     3.6    43.9     4.2    44.7     5.9    45.8     6.6    45.8
     6.8    45.6    16.8    45.6
#Mann= 3 , 0 , 0
   -12.6    .035       0       0    .035       0     5.9    .035       0
Levee=-1,0,45,-1,5.9,,,
#XS Ineff= 2 , 0
               0    44.3     5.9            45.8
Permanent Ineff=
       F       F
Bank Sta=0,5.9
XS Rating Curve= 0
Exp/Cntr=.3,.1

Type RM Length L Ch R = 1 ,32      ,50,50,50
#Sta/Elev= 12
   -12.6   42.32    -2.6   42.32      -2   42.82       0   42.82     1.6   42.12
     2.5   42.12     3.6   42.42     4.2   43.22     5.9   44.32     6.6   44.32
     6.8   44.12    16.8   44.12
#Mann= 3 , 0 , 0
   -12.6    .035       0       0    .035       0     5.9    .035       0
Levee=-1,0,45,-1,5.9,44.32,,
#XS Ineff= 2 , 0
               0   42.82     5.9           44.32
Permanent Ineff=
       F       F
Bank Sta=0,5.9
XS Rating Curve= 0
Exp/Cntr=.3,.1

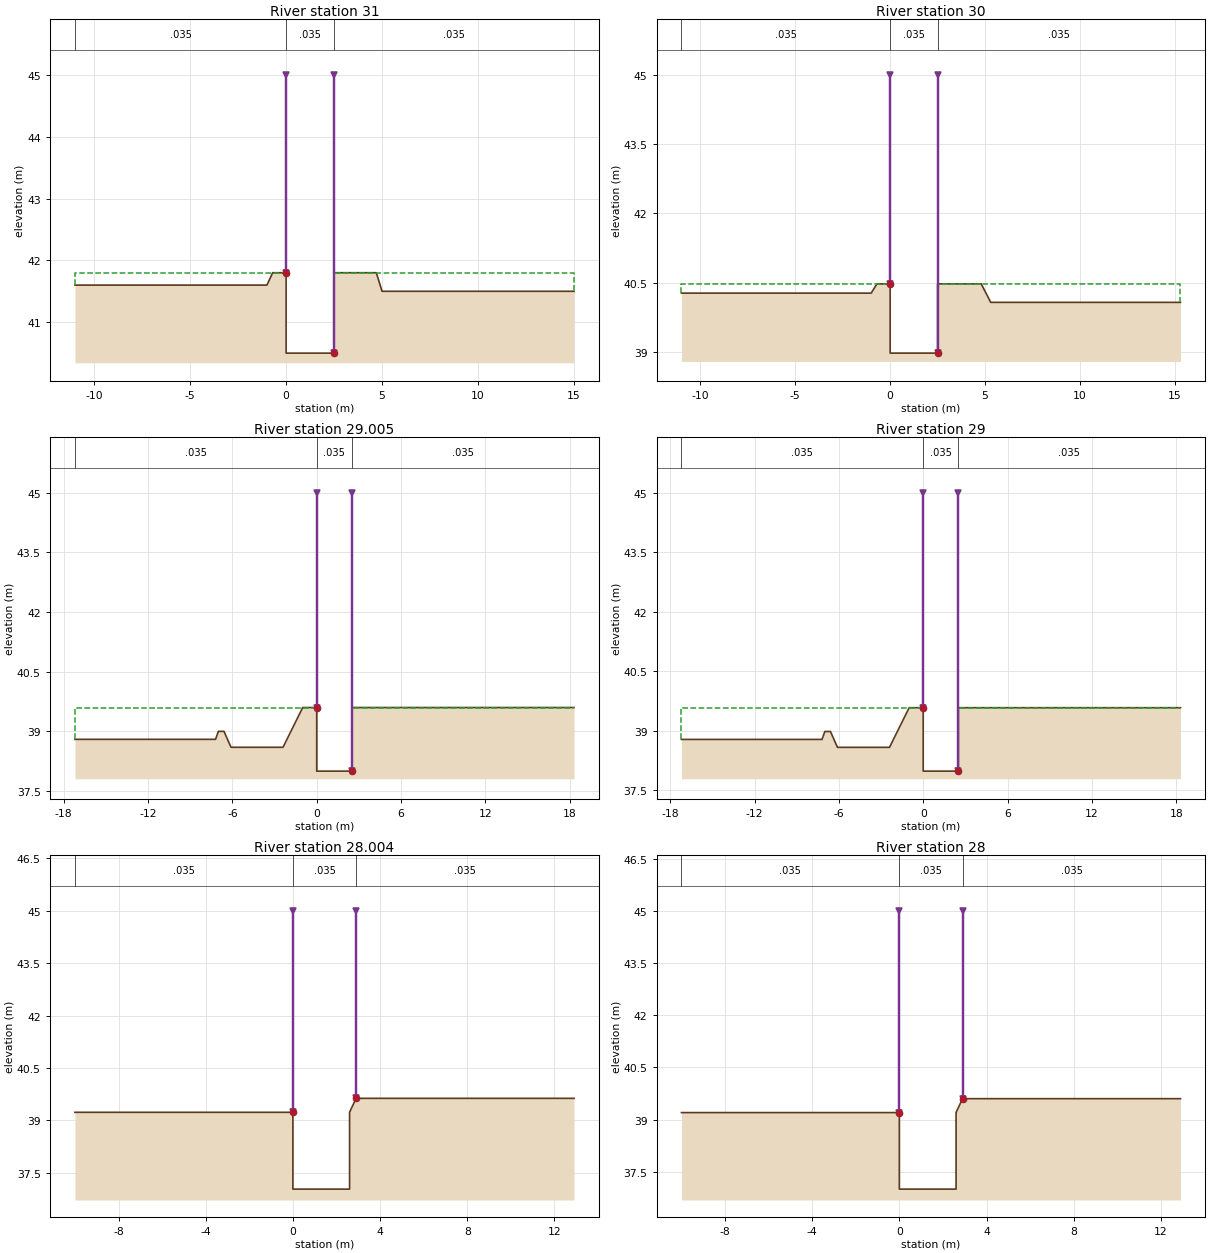
Type RM Length L Ch R = 1 ,31      ,50,50,50
#Sta/Elev= 10
     -11    41.6      -1    41.6     -.7    41.8       0    41.8       0    40.5
     2.5    40.5     2.5    41.8     4.7    41.8       5    41.5      15    41.5
#Mann= 3 , 0 , 0
     -11    .035       0       0    .035       0     2.5    .035       0
Levee=-1,0,45,-1,2.5,45,,
#XS Ineff= 2 , 0
               0    41.8     2.5            41.8
Permanent Ineff=
       F       F
Bank Sta=0,2.5
XS Rating Curve= 0
Exp/Cntr=.3,.1

Type RM Length L Ch R = 1 ,30      ,45,45,45
#Sta/Elev= 10
     -11   40.27      -1   40.27     -.7   40.47       0   40.47       0   38.97
     2.5   38.97     2.5   40.47     4.8   40.47     5.3   40.07    15.3   40.07
#Mann= 3 , 0 , 0
     -11    .035       0       0    .035       0     2.5    .035       0
Levee=-1,0,45,-1,2.5,45,,
#XS Ineff= 2 , 0
               0   40.47     2.5           40.47
Permanent Ineff=
       F       F
Bank Sta=0,2.5
XS Rating Curve= 0
Exp/Cntr=.3,.1

Type RM Length L Ch R = 1 ,29.005  ,5,5,5
#Sta/Elev= 13
   -17.2    38.8    -7.2    38.8      -7      39    -6.6      39    -6.1    38.6
    -2.4    38.6      -1    39.6       0    39.6       0      38     2.5      38
     2.5    39.6     8.3    39.6    18.3    39.6
#Mann= 3 , 0 , 0
   -17.2    .035       0       0    .035       0     2.5    .035       0
Levee=-1,0,45,-1,2.5,45,,
#XS Ineff= 2 , 0
               0    39.6     2.5            39.6
Permanent Ineff=
       F       F
Bank Sta=0,2.5
XS Rating Curve= 0
Exp/Cntr=.3,.1

Type RM Length L Ch R = 1 ,29      ,46,46,46
#Sta/Elev= 13
   -17.2   38.78    -7.2   38.78      -7   38.98    -6.6   38.98    -6.1   38.58
    -2.4   38.58      -1   39.58       0   39.58       0   37.98     2.5   37.98
     2.5   39.58     8.3   39.58    18.3   39.58
#Mann= 3 , 0 , 0
   -17.2    .035       0       0    .035       0     2.5    .035       0
Levee=-1,0,45,-1,2.5,45,,
#XS Ineff= 2 , 0
               0   39.58     2.5           39.58
Permanent Ineff=
       F       F
Bank Sta=0,2.5
XS Rating Curve= 0
Exp/Cntr=.3,.1

Type RM Length L Ch R = 1 ,28.004  ,4,4,4
#Sta/Elev= 7
     -10   39.23       0   39.23       0   37.03     2.6   37.03     2.6   39.23
     2.9   39.63    12.9   39.63
#Mann= 3 , 0 , 0
     -10    .035       0       0    .035       0     2.9    .035       0
Levee=-1,0,45,-1,2.9,45,,
#XS Ineff= 2 , 0
               0   39.23     2.9           39.63
Permanent Ineff=
       F       F
Bank Sta=0,2.9
XS Rating Curve= 0
Exp/Cntr=.3,.1

Type RM Length L Ch R = 1 ,28      ,28,28,28
#Sta/Elev= 7
     -10    39.2       0    39.2       0      37     2.6      37     2.6    39.2
     2.9    39.6    12.9    39.6
#Mann= 3 , 0 , 0
     -10    .035       0       0    .035       0     2.9    .035       0
Levee=-1,0,45,-1,2.9,45,,
#XS Ineff= 2 , 0
               0    39.2     2.9            39.6
Permanent Ineff=
       F       F
Bank Sta=0,2.9
XS Rating Curve= 0
Exp/Cntr=.3,.1

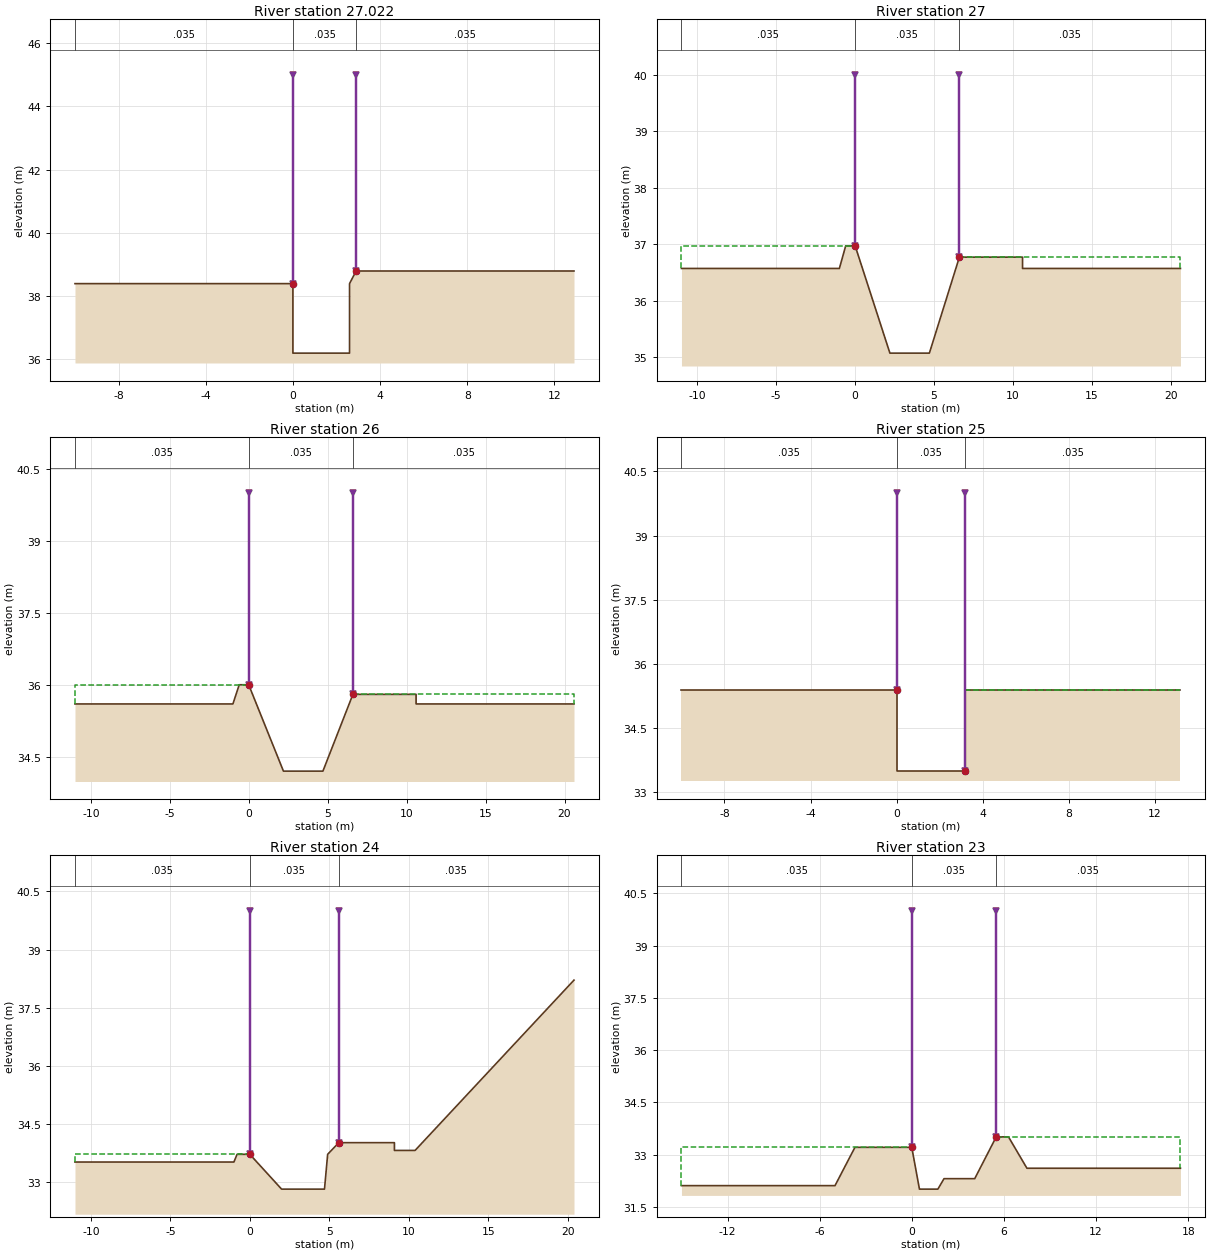
Type RM Length L Ch R = 1 ,27.022  ,22,22,22
#Sta/Elev= 7
     -10   38.39       0   38.39       0   36.19     2.6   36.19     2.6   38.39
     2.9   38.79    12.9   38.79
#Mann= 3 , 0 , 0
     -10    .035       0       0    .035       0     2.9    .035       0
Levee=-1,0,45,-1,2.9,45,,
#XS Ineff= 2 , 0
               0   38.39     2.9           38.79
Permanent Ineff=
       F       F
Bank Sta=0,2.9
XS Rating Curve= 0
Exp/Cntr=.3,.1

Type RM Length L Ch R = 1 ,27      ,50,50,50
#Sta/Elev= 10
     -11   36.57      -1   36.57     -.6   36.97       0   36.97     2.2   35.07
     4.7   35.07     6.6   36.77    10.6   36.77    10.6   36.57    20.6   36.57
#Mann= 3 , 0 , 0
     -11    .035       0       0    .035       0     6.6    .035       0
Levee=-1,0,40,-1,6.6,40,,
#XS Ineff= 2 , 0
               0   36.97     6.6           36.77
Permanent Ineff=
       F       F
Bank Sta=0,6.6
XS Rating Curve= 0
Exp/Cntr=.3,.1

Type RM Length L Ch R = 1 ,26      ,50,50,50
#Sta/Elev= 10
     -11    35.6      -1    35.6     -.6      36       0      36     2.2    34.2
     4.7    34.2     6.6    35.8    10.6    35.8    10.6    35.6    20.6    35.6
#Mann= 3 , 0 , 0
     -11    .035       0       0    .035       0     6.6    .035       0
Levee=-1,0,40,-1,6.6,40,,
#XS Ineff= 2 , 0
               0      36     6.6            35.8
Permanent Ineff=
       F       F
Bank Sta=0,6.6
XS Rating Curve= 0
Exp/Cntr=.3,.1

Type RM Length L Ch R = 1 ,25      ,50,50,50
#Sta/Elev= 6
     -10   35.39       0   35.39       0   33.49     3.2   33.49     3.2   35.39
    13.2   35.39
#Mann= 3 , 0 , 0
     -10    .035       0       0    .035       0     3.2    .035       0
Levee=-1,0,40,-1,3.2,40,,
#XS Ineff= 2 , 0
               0   35.39     3.2           35.39
Permanent Ineff=
       F       F
Bank Sta=0,3.2
XS Rating Curve= 0
Exp/Cntr=.3,.1

Type RM Length L Ch R = 1 ,24      ,50,50,50
#Sta/Elev= 13
     -11   33.51      -1   33.51     -.8   33.71       0   33.71       2   32.81
     4.7   32.81     4.9   33.71     5.6   34.01     9.1   34.01     9.1   33.81
    10.4   33.81    15.4   36.01    20.4   38.21
#Mann= 3 , 0 , 0
     -11    .035       0       0    .035       0     5.6    .035       0
Levee=-1,0,40,-1,5.6,40,,
#XS Ineff= 2 , 0
               0   33.71     5.6           34.01
Permanent Ineff=
       F       F
Bank Sta=0,5.6
XS Rating Curve= 0
Exp/Cntr=.3,.1

Type RM Length L Ch R = 1 ,23      ,50,50,50
#Sta/Elev= 12
     -15   32.11      -5   32.11    -3.7   33.21       0   33.21      .5   32.01
     1.7   32.01     2.1   32.31     4.1   32.31     5.5   33.51     6.3   33.51
     7.5   32.61    17.5   32.61
#Mann= 3 , 0 , 0
     -15    .035       0       0    .035       0     5.5    .035       0
Levee=-1,0,40,-1,5.5,40,,
#XS Ineff= 2 , 0
               0   33.21     5.5           33.51
Permanent Ineff=
       F       F
Bank Sta=0,5.5
XS Rating Curve= 0
Exp/Cntr=.3,.1

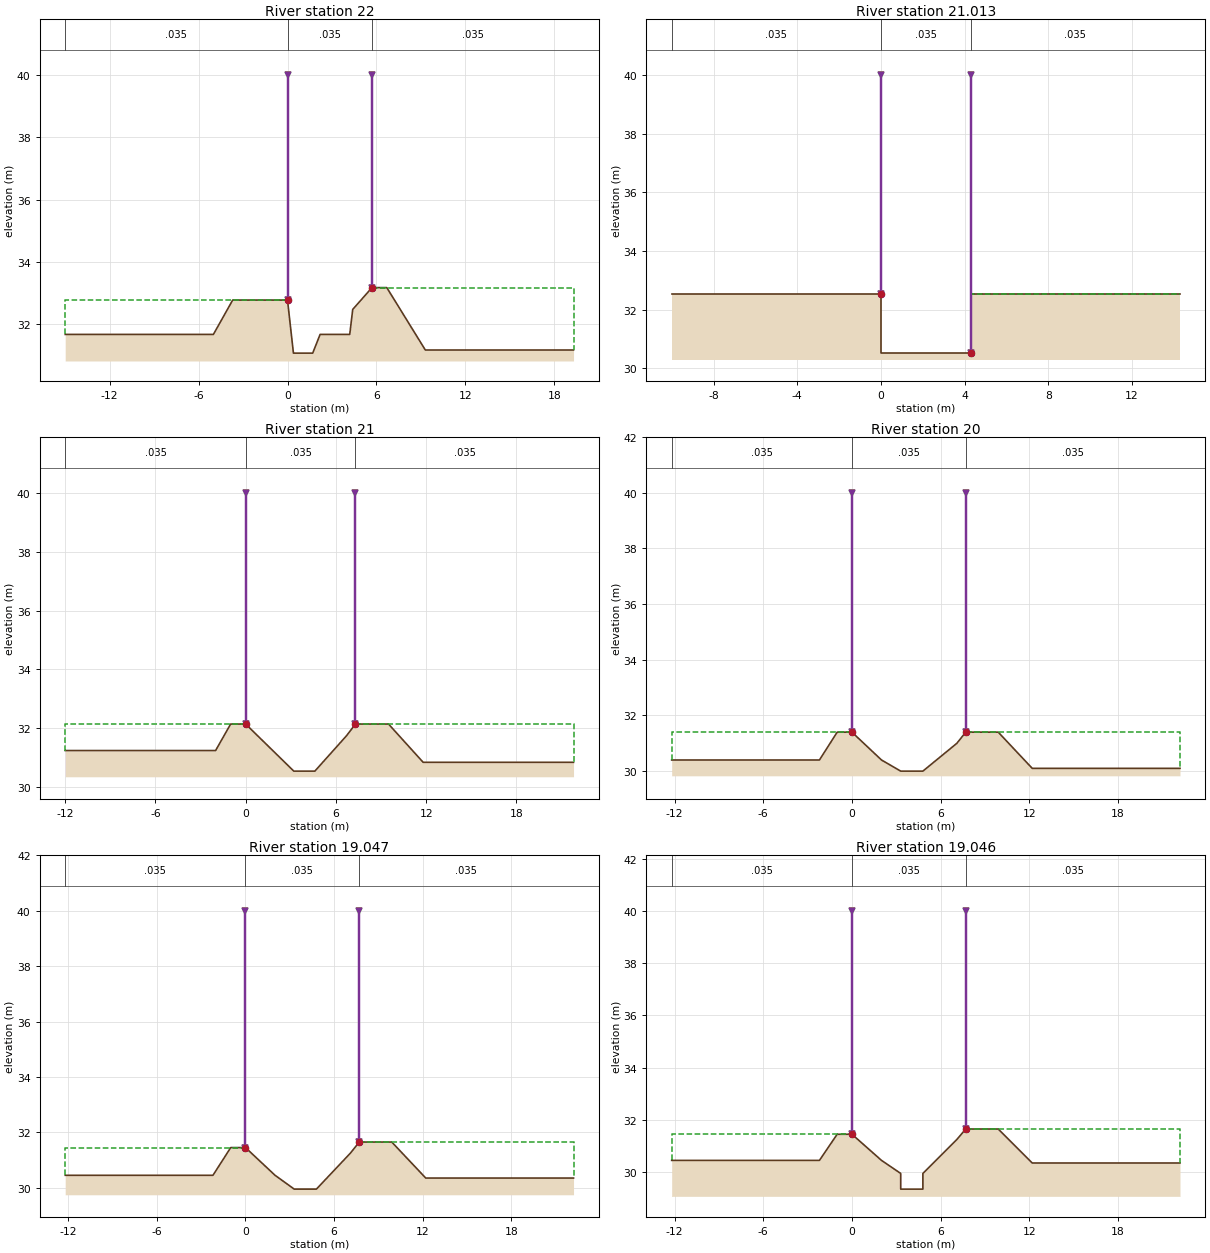
Type RM Length L Ch R = 1 ,22      ,37,37,37
#Sta/Elev= 14
     -15   31.68      -5   31.68    -3.7   32.78       0   32.78      .4   31.08
     1.7   31.08     2.2   31.68     4.2   31.68     4.4   32.48     5.7   33.18
     6.7   33.18       8   32.18     9.3   31.18    19.3   31.18
#Mann= 3 , 0 , 0
     -15    .035       0       0    .035       0     5.7    .035       0
Levee=-1,0,40,-1,5.7,40,,
#XS Ineff= 2 , 0
               0   32.78     5.7           33.18
Permanent Ineff=
       F       F
Bank Sta=0,5.7
XS Rating Curve= 0
Exp/Cntr=.3,.1

Type RM Length L Ch R = 1 ,21.013  ,13,13,13
#Sta/Elev= 6
     -10   32.52       0   32.52       0   30.52     4.3   30.52     4.3   32.52
    14.3   32.52
#Mann= 3 , 0 , 0
     -10    .035       0       0    .035       0     4.3    .035       0
Levee=-1,0,40,-1,4.3,40,,
#XS Ineff= 2 , 0
               0   32.52     4.3           32.52
Permanent Ineff=
       F       F
Bank Sta=0,4.3
XS Rating Curve= 0
Exp/Cntr=.3,.1

Type RM Length L Ch R = 1 ,21      ,50,50,50
#Sta/Elev= 12
     -12   31.24      -2   31.24      -1   32.14       0   32.14       2   31.14
     3.2   30.54     4.6   30.54     6.7   31.74     7.3   32.14     9.5   32.14
    11.8   30.84    21.8   30.84
#Mann= 3 , 0 , 0
     -12    .035       0       0    .035       0     7.3    .035       0
Levee=-1,0,40,-1,7.3,40,,
#XS Ineff= 2 , 0
               0   32.14     7.3           32.14
Permanent Ineff=
       F       F
Bank Sta=0,7.3
XS Rating Curve= 0
Exp/Cntr=.3,.1

Type RM Length L Ch R = 1 ,20      ,3,3,3
#Sta/Elev= 12
   -12.2    30.4    -2.2    30.4      -1    31.4       0    31.4       2    30.4
     3.3      30     4.8      30     7.1      31     7.7    31.4     9.9    31.4
    12.2    30.1    22.2    30.1
#Mann= 3 , 0 , 0
   -12.2    .035       0       0    .035       0     7.7    .035       0
Levee=-1,0,40,-1,7.7,40,,
#XS Ineff= 2 , 0
               0    31.4     7.7            31.4
Permanent Ineff=
       F       F
Bank Sta=0,7.7
XS Rating Curve= 0
Exp/Cntr=.3,.1

Type RM Length L Ch R = 1 ,19.047  ,1,1,1
#Sta/Elev= 12
   -12.2   30.45    -2.2   30.45      -1   31.45       0   31.45       2   30.45
     3.3   29.95     4.8   29.95     7.1   31.25     7.7   31.65     9.9   31.65
    12.2   30.35    22.2   30.35
#Mann= 3 , 0 , 0
   -12.2    .035       0       0    .035       0     7.7    .035       0
Levee=-1,0,40,-1,7.7,40,,
#XS Ineff= 2 , 0
               0   31.45     7.7           31.65
Permanent Ineff=
       F       F
Bank Sta=0,7.7
XS Rating Curve= 0
Exp/Cntr=.3,.1

Type RM Length L Ch R = 1 ,19.046  ,46,46,46
#Sta/Elev= 14
   -12.2   30.45    -2.2   30.45      -1   31.45       0   31.45       2   30.45
     3.3   29.95     3.3   29.35     4.8   29.35     4.8   29.95     7.1   31.25
     7.7   31.65     9.9   31.65    12.2   30.35    22.2   30.35
#Mann= 3 , 0 , 0
   -12.2    .035       0       0    .035       0     7.7    .035       0
Levee=-1,0,40,-1,7.7,40,,
#XS Ineff= 2 , 0
               0   31.45     7.7           31.65
Permanent Ineff=
       F       F
Bank Sta=0,7.7
XS Rating Curve= 0
Exp/Cntr=.3,.1

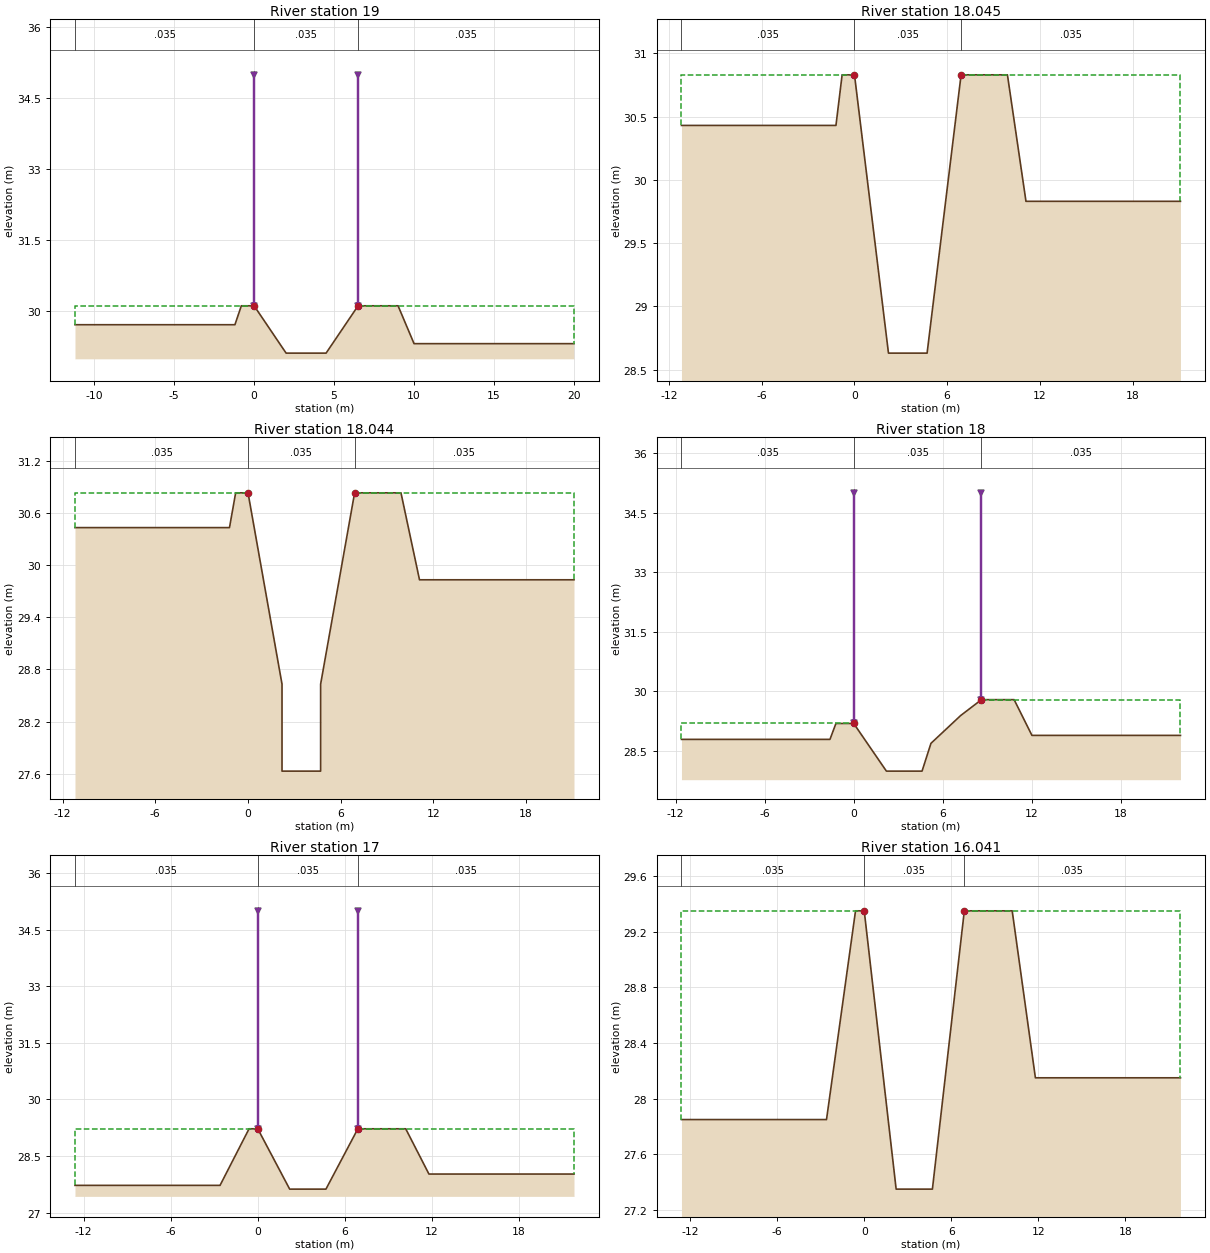
Type RM Length L Ch R = 1 ,19      ,5,5,5
#Sta/Elev= 10
   -11.2   29.72    -1.2   29.72     -.8   30.12       0   30.12       2   29.12
     4.5   29.12     6.5   30.12       9   30.12      10   29.32      20   29.32
#Mann= 3 , 0 , 0
   -11.2    .035       0       0    .035       0     6.5    .035       0
Levee=-1,0,35,-1,6.5,35,,
#XS Ineff= 2 , 0
               0   30.12     6.5           30.12
Permanent Ineff=
       F       F
Bank Sta=0,6.5
XS Rating Curve= 0
Exp/Cntr=.3,.1

Type RM Length L Ch R = 1 ,18.045  ,1,1,1
#Sta/Elev= 10
   -11.2   30.43    -1.2   30.43     -.8   30.83       0   30.83     2.2   28.63
     4.7   28.63     6.9   30.83     9.9   30.83    11.1   29.83    21.1   29.83
#Mann= 3 , 0 , 0
   -11.2    .035       0       0    .035       0     6.9    .035       0
#XS Ineff= 2 , 0
               0   30.83     6.9           30.83
Permanent Ineff=
       F       F
Bank Sta=0,6.9
XS Rating Curve= 0
Exp/Cntr=.3,.1

Type RM Length L Ch R = 1 ,18.044  ,44,44,44
#Sta/Elev= 12
   -11.2   30.43    -1.2   30.43     -.8   30.83       0   30.83     2.2   28.63
     2.2   27.63     4.7   27.63     4.7   28.63     6.9   30.83     9.9   30.83
    11.1   29.83    21.1   29.83
#Mann= 3 , 0 , 0
   -11.2    .035       0       0    .035       0     6.9    .035       0
#XS Ineff= 2 , 0
               0   30.83     6.9           30.83
Permanent Ineff=
       F       F
Bank Sta=0,6.9
XS Rating Curve= 0
Exp/Cntr=.3,.1

Type RM Length L Ch R = 1 ,18      ,50,50,50
#Sta/Elev= 12
   -11.6   28.79    -1.6   28.79    -1.2   29.19       0   29.19     2.2   27.99
     4.6   27.99     5.2   28.69     7.2   29.39     8.6   29.79    10.8   29.79
      12   28.89      22   28.89
#Mann= 3 , 0 , 0
   -11.6    .035       0       0    .035       0     8.6    .035       0
Levee=-1,0,35,-1,8.6,35,,
#XS Ineff= 2 , 0
               0   29.19     8.6           29.79
Permanent Ineff=
       F       F
Bank Sta=0,8.6
XS Rating Curve= 0
Exp/Cntr=.3,.1

Type RM Length L Ch R = 1 ,17      ,9,9,9
#Sta/Elev= 10
   -12.6   27.72    -2.6   27.72     -.6   29.22       0   29.22     2.2   27.62
     4.7   27.62     6.9   29.22    10.2   29.22    11.8   28.02    21.8   28.02
#Mann= 3 , 0 , 0
   -12.6    .035       0       0    .035       0     6.9    .035       0
Levee=-1,0,35,-1,6.9,35,,
#XS Ineff= 2 , 0
               0   29.22     6.9           29.22
Permanent Ineff=
       F       F
Bank Sta=0,6.9
XS Rating Curve= 0
Exp/Cntr=.3,.1

Type RM Length L Ch R = 1 ,16.041  ,1,1,1
#Sta/Elev= 10
   -12.6   27.85    -2.6   27.85     -.6   29.35       0   29.35     2.2   27.35
     4.7   27.35     6.9   29.35    10.2   29.35    11.8   28.15    21.8   28.15
#Mann= 3 , 0 , 0
   -12.6    .035       0       0    .035       0     6.9    .035       0
#XS Ineff= 2 , 0
               0   29.35     6.9           29.35
Permanent Ineff=
       F       F
Bank Sta=0,6.9
XS Rating Curve= 0
Exp/Cntr=.3,.1