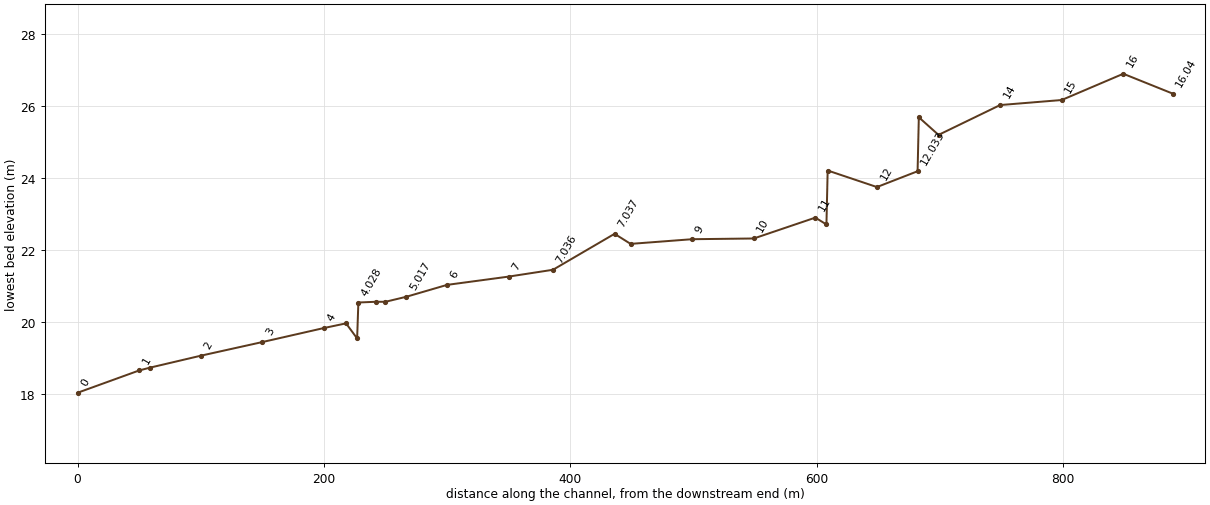
HEC-RAS study mkc.prj: magang-ch

--- mkc.g01 (geometry) --- (continued)

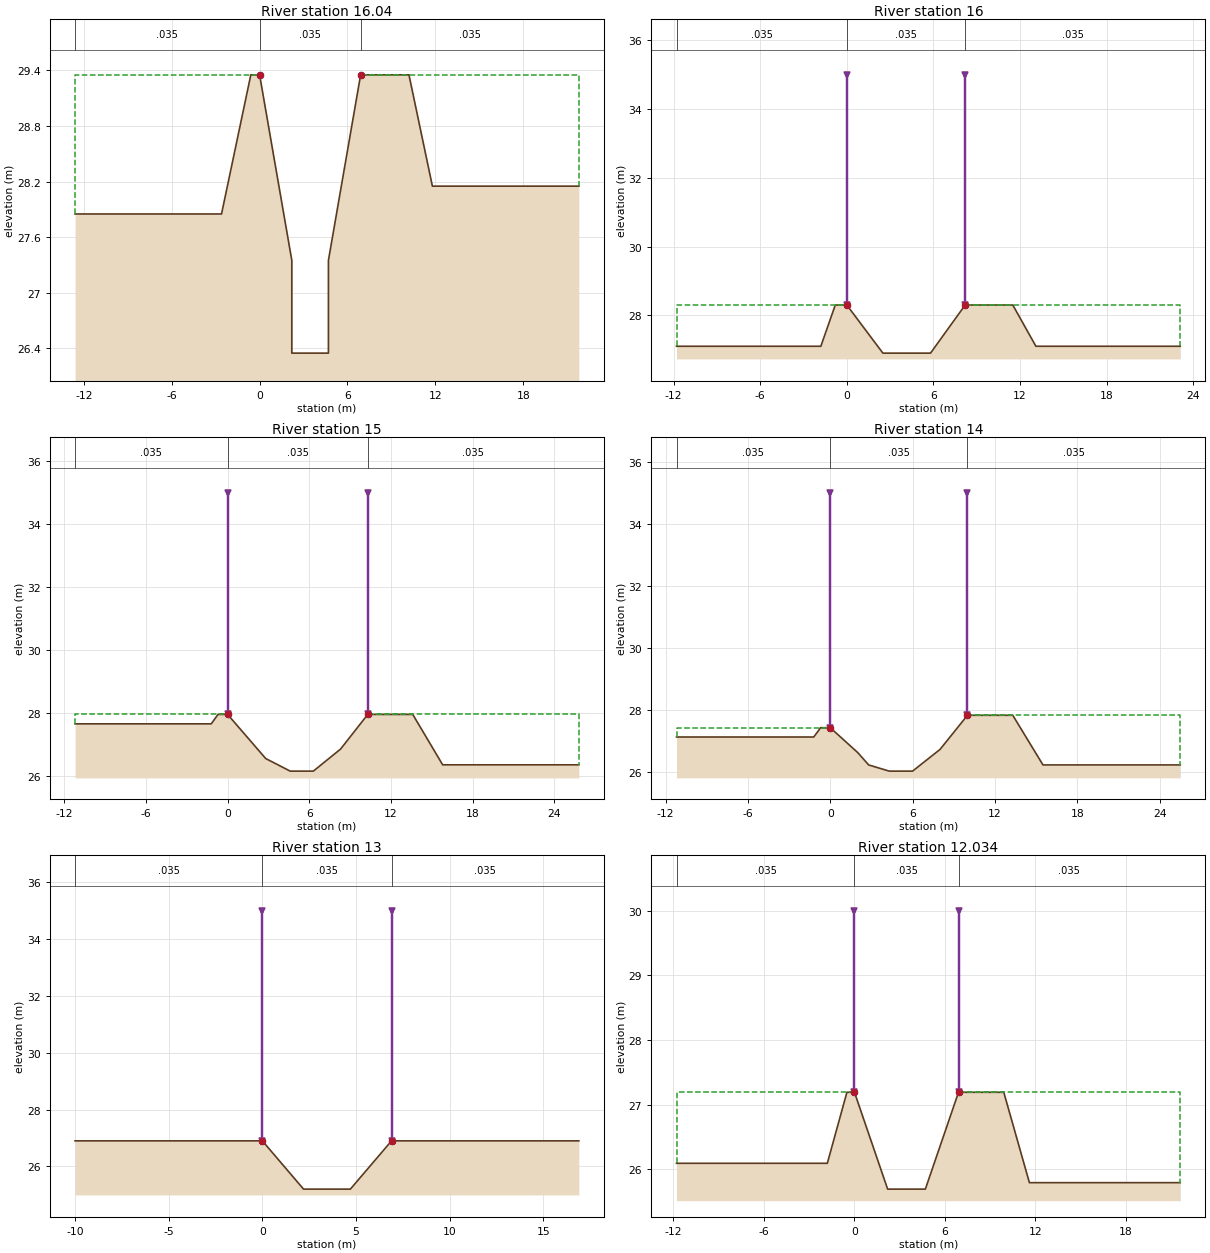
Type RM Length L Ch R = 1 ,16.04   ,40,40,40
#Sta/Elev= 12
   -12.6   27.85    -2.6   27.85     -.6   29.35       0   29.35     2.2   27.35
     2.2   26.35     4.7   26.35     4.7   27.35     6.9   29.35    10.2   29.35
    11.8   28.15    21.8   28.15
#Mann= 3 , 0 , 0
   -12.6    .035       0       0    .035       0     6.9    .035       0
#XS Ineff= 2 , 0
               0   29.35     6.9           29.35
Permanent Ineff=
       F       F
Bank Sta=0,6.9
XS Rating Curve= 0
Exp/Cntr=.3,.1

Type RM Length L Ch R = 1 ,16      ,50,50,50
#Sta/Elev= 10
   -11.8    27.1    -1.8    27.1     -.8    28.3       0    28.3     2.5    26.9
     5.8    26.9     8.2    28.3    11.5    28.3    13.1    27.1    23.1    27.1
#Mann= 3 , 0 , 0
   -11.8    .035       0       0    .035       0     8.2    .035       0
Levee=-1,0,35,-1,8.2,35,,
#XS Ineff= 2 , 0
               0    28.3     8.2            28.3
Permanent Ineff=
       F       F
Bank Sta=0,8.2
XS Rating Curve= 0
Exp/Cntr=.3,.1

Type RM Length L Ch R = 1 ,15      ,50,50,50
#Sta/Elev= 13
   -11.2   27.67    -1.2   27.67     -.7   27.97       0   27.97       2   26.97
     2.8   26.57     4.6   26.17     6.3   26.17     8.3   26.87    10.3   27.97
    13.6   27.97    15.8   26.37    25.8   26.37
#Mann= 3 , 0 , 0
   -11.2    .035       0       0    .035       0    10.3    .035       0
Levee=-1,0,35,-1,10.3,35,,
#XS Ineff= 2 , 0
               0   27.97    10.3           27.97
Permanent Ineff=
       F       F
Bank Sta=0,10.3
XS Rating Curve= 0
Exp/Cntr=.3,.1

Type RM Length L Ch R = 1 ,14      ,50,50,50
#Sta/Elev= 13
   -11.2   27.13    -1.2   27.13     -.7   27.43       0   27.43       2   26.63
     2.8   26.23     4.3   26.03       6   26.03       8   26.73      10   27.83
    13.3   27.83    15.5   26.23    25.5   26.23
#Mann= 3 , 0 , 0
   -11.2    .035       0       0    .035       0      10    .035       0
Levee=-1,0,35,-1,10,35,,
#XS Ineff= 2 , 0
               0   27.43      10           27.83
Permanent Ineff=
       F       F
Bank Sta=0,10
XS Rating Curve= 0
Exp/Cntr=.3,.1

Type RM Length L Ch R = 1 ,13      ,16,16,16
#Sta/Elev= 6
     -10    26.9       0    26.9     2.2    25.2     4.7    25.2     6.9    26.9
    16.9    26.9
#Mann= 3 , 0 , 0
     -10    .035       0       0    .035       0     6.9    .035       0
Levee=-1,0,35,-1,6.9,35,,
#XS Ineff= 2 , 0
               0    26.9     6.9            26.9
Permanent Ineff=
       F       F
Bank Sta=0,6.9
XS Rating Curve= 0
Exp/Cntr=.3,.1

Type RM Length L Ch R = 1 ,12.034  ,1,1,1
#Sta/Elev= 10
   -11.8   26.09    -1.8   26.09     -.5   27.19       0   27.19     2.2   25.69
     4.7   25.69     6.9   27.19     9.9   27.19    11.6   25.79    21.6   25.79
#Mann= 3 , 0 , 0
   -11.8    .035       0       0    .035       0     6.9    .035       0
Levee=-1,0,30,-1,6.9,30,,
#XS Ineff= 2 , 0
               0   27.19     6.9           27.19
Permanent Ineff=
       F       F
Bank Sta=0,6.9
XS Rating Curve= 0
Exp/Cntr=.3,.1

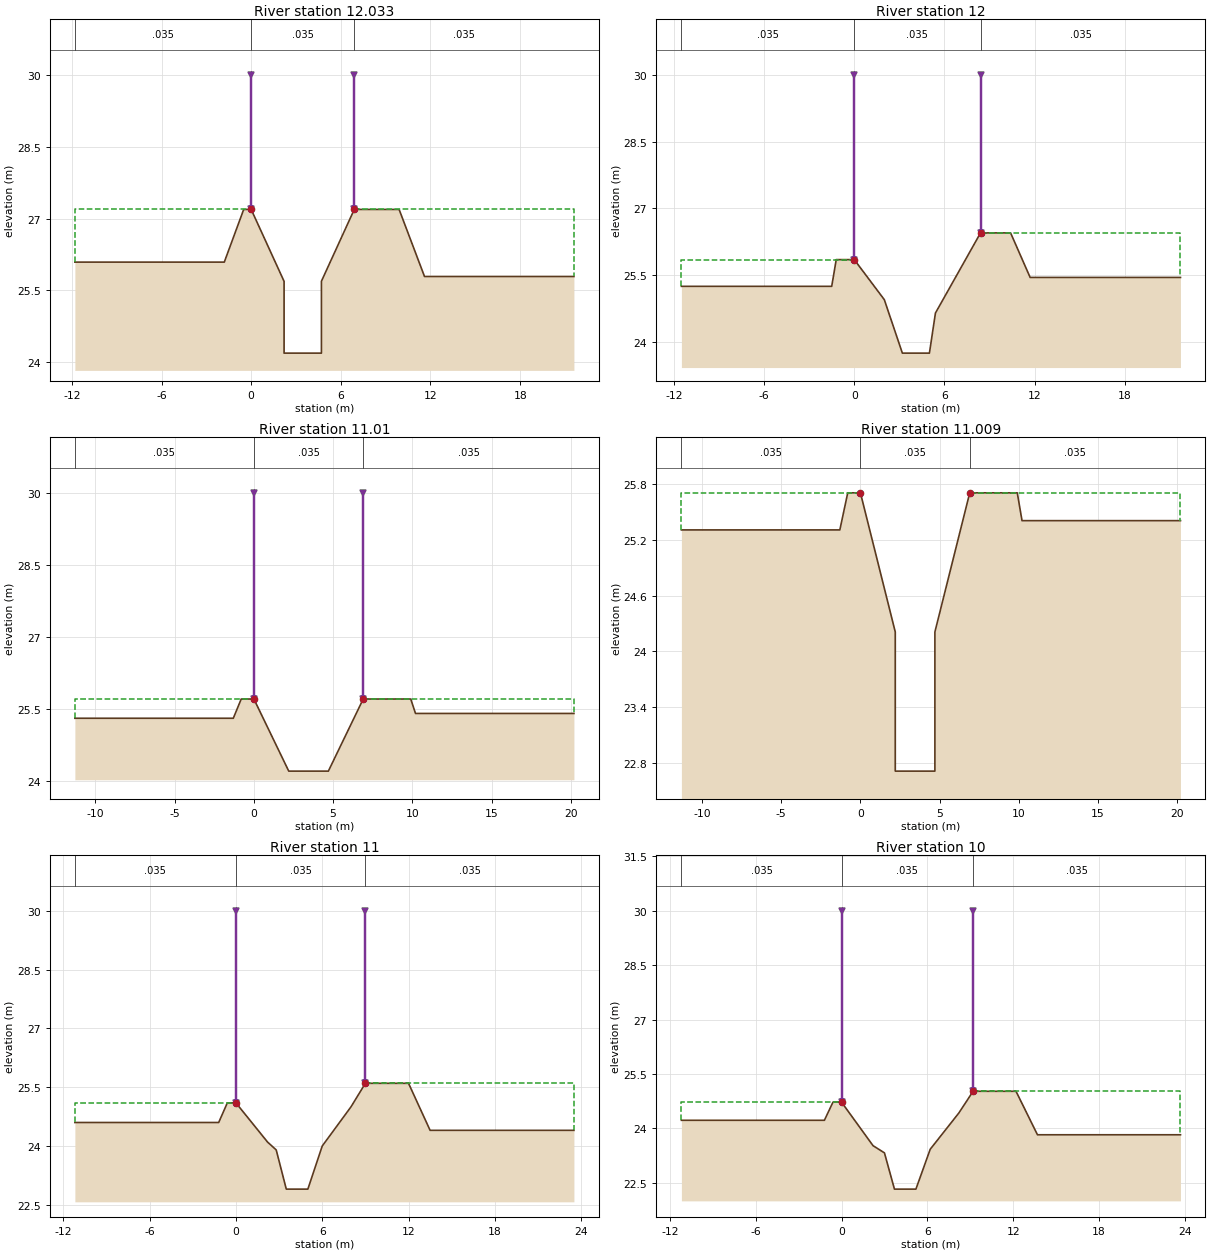
Type RM Length L Ch R = 1 ,12.033  ,33,33,33
#Sta/Elev= 12
   -11.8   26.09    -1.8   26.09     -.5   27.19       0   27.19     2.2   25.69
     2.2   24.19     4.7   24.19     4.7   25.69     6.9   27.19     9.9   27.19
    11.6   25.79    21.6   25.79
#Mann= 3 , 0 , 0
   -11.8    .035       0       0    .035       0     6.9    .035       0
Levee=-1,0,30,-1,6.9,30,,
#XS Ineff= 2 , 0
               0   27.19     6.9           27.19
Permanent Ineff=
       F       F
Bank Sta=0,6.9
XS Rating Curve= 0
Exp/Cntr=.3,.1

Type RM Length L Ch R = 1 ,12      ,40,40,40
#Sta/Elev= 13
   -11.5   25.25    -1.5   25.25    -1.2   25.85       0   25.85       2   24.95
     3.2   23.75       5   23.75     5.4   24.65     7.4   25.85     8.4   26.45
    10.4   26.45    11.7   25.45    21.7   25.45
#Mann= 3 , 0 , 0
   -11.5    .035       0       0    .035       0     8.4    .035       0
Levee=-1,0,30,-1,8.4,30,,
#XS Ineff= 2 , 0
               0   25.85     8.4           26.45
Permanent Ineff=
       F       F
Bank Sta=0,8.4
XS Rating Curve= 0
Exp/Cntr=.3,.1

Type RM Length L Ch R = 1 ,11.01   ,1,1,1
#Sta/Elev= 10
   -11.3   25.31    -1.3   25.31     -.8   25.71       0   25.71     2.2   24.21
     4.7   24.21     6.9   25.71     9.9   25.71    10.2   25.41    20.2   25.41
#Mann= 3 , 0 , 0
   -11.3    .035       0       0    .035       0     6.9    .035       0
Levee=-1,0,30,-1,6.9,30,,
#XS Ineff= 2 , 0
               0   25.71     6.9           25.71
Permanent Ineff=
       F       F
Bank Sta=0,6.9
XS Rating Curve= 0
Exp/Cntr=.3,.1

Type RM Length L Ch R = 1 ,11.009  ,9,9,9
#Sta/Elev= 12
   -11.3   25.31    -1.3   25.31     -.8   25.71       0   25.71     2.2   24.21
     2.2   22.71     4.7   22.71     4.7   24.21     6.9   25.71     9.9   25.71
    10.2   25.41    20.2   25.41
#Mann= 3 , 0 , 0
   -11.3    .035       0       0    .035       0     6.9    .035       0
#XS Ineff= 2 , 0
               0   25.71     6.9           25.71
Permanent Ineff=
       F       F
Bank Sta=0,6.9
XS Rating Curve= 0
Exp/Cntr=.3,.1

Type RM Length L Ch R = 1 ,11      ,50,50,50
#Sta/Elev= 14
   -11.2    24.6    -1.2    24.6     -.6    25.1       0    25.1     2.2    24.1
     2.8    23.9     3.5    22.9       5    22.9       6      24       8      25
       9    25.6      12    25.6    13.5    24.4    23.5    24.4
#Mann= 3 , 0 , 0
   -11.2    .035       0       0    .035       0       9    .035       0
Levee=-1,0,30,-1,9,30,,
#XS Ineff= 2 , 0
               0    25.1       9            25.6
Permanent Ineff=
       F       F
Bank Sta=0,9
XS Rating Curve= 0
Exp/Cntr=.3,.1

Type RM Length L Ch R = 1 ,10      ,50,50,50
#Sta/Elev= 14
   -11.2   24.22    -1.2   24.22     -.6   24.72       0   24.72     2.2   23.52
       3   23.32     3.7   22.32     5.2   22.32     6.2   23.42     8.2   24.42
     9.2   25.02    12.2   25.02    13.7   23.82    23.7   23.82
#Mann= 3 , 0 , 0
   -11.2    .035       0       0    .035       0     9.2    .035       0
Levee=-1,0,30,-1,9.2,30,,
#XS Ineff= 2 , 0
               0   24.72     9.2           25.02
Permanent Ineff=
       F       F
Bank Sta=0,9.2
XS Rating Curve= 0
Exp/Cntr=.3,.1

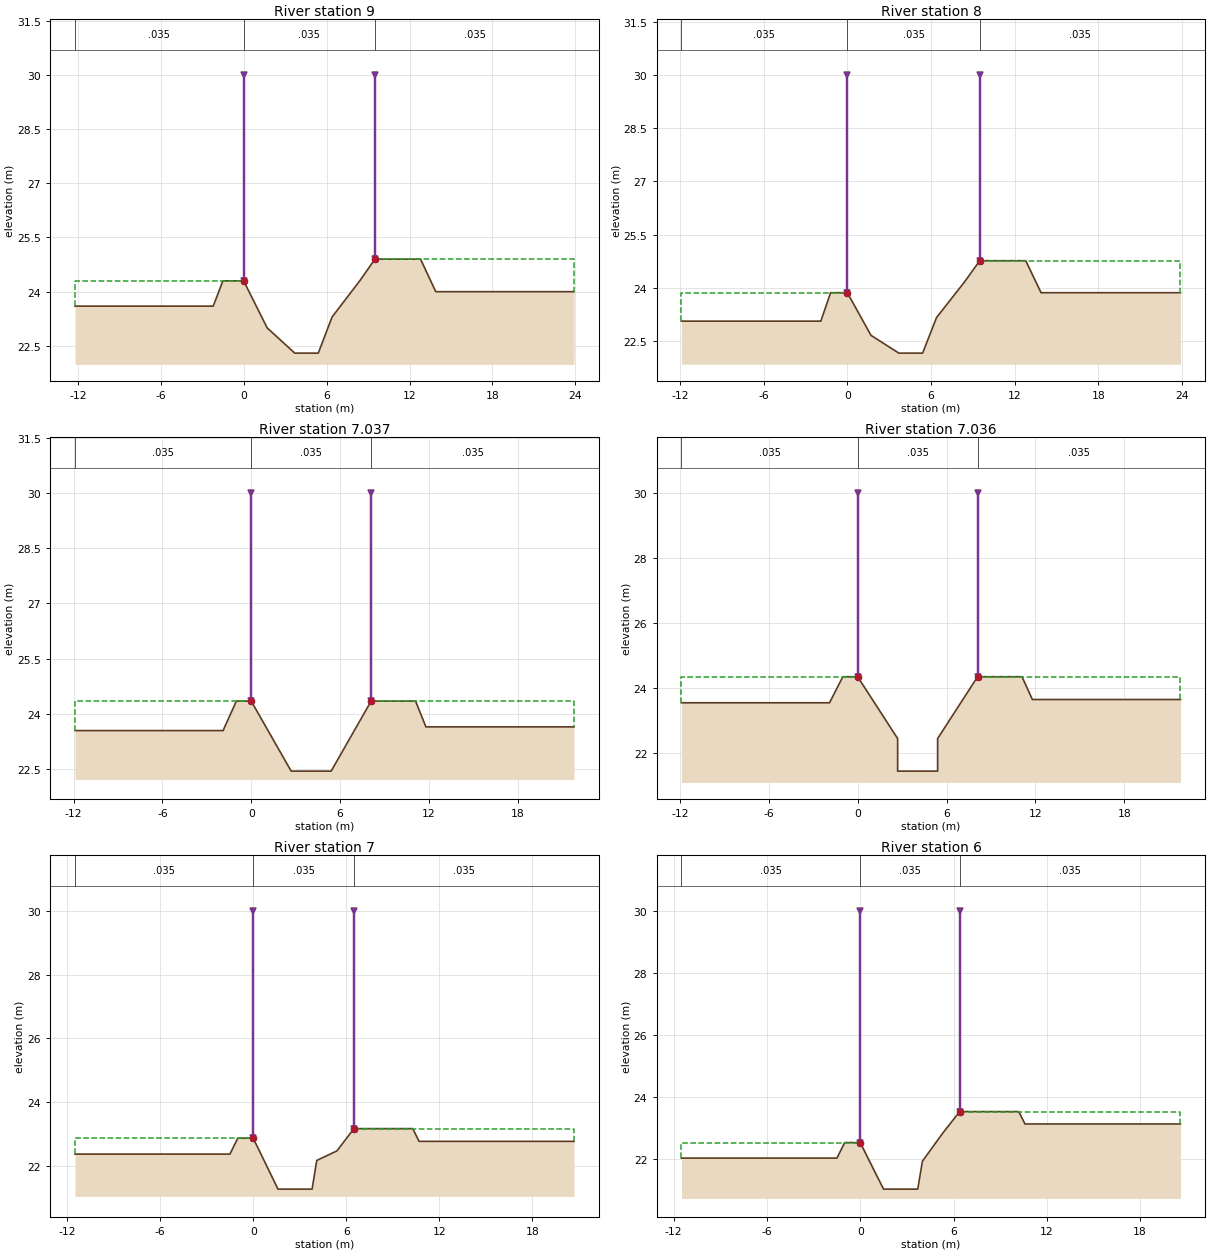
Type RM Length L Ch R = 1 ,9       ,50,50,50
#Sta/Elev= 13
   -12.2    23.6    -2.2    23.6    -1.5    24.3       0    24.3     1.7      23
     3.7    22.3     5.4    22.3     6.4    23.3     8.4    24.3     9.5    24.9
    12.8    24.9    13.9      24    23.9      24
#Mann= 3 , 0 , 0
   -12.2    .035       0       0    .035       0     9.5    .035       0
Levee=-1,0,30,-1,9.5,30,,
#XS Ineff= 2 , 0
               0    24.3     9.5            24.9
Permanent Ineff=
       F       F
Bank Sta=0,9.5
XS Rating Curve= 0
Exp/Cntr=.3,.1

Type RM Length L Ch R = 1 ,8       ,13,13,13
#Sta/Elev= 13
   -11.9   23.07    -1.9   23.07    -1.2   23.87       0   23.87     1.7   22.67
     3.7   22.17     5.4   22.17     6.4   23.17     8.4   24.17     9.5   24.77
    12.8   24.77    13.9   23.87    23.9   23.87
#Mann= 3 , 0 , 0
   -11.9    .035       0       0    .035       0     9.5    .035       0
Levee=-1,0,30,-1,9.5,30,,
#XS Ineff= 2 , 0
               0   23.87     9.5           24.77
Permanent Ineff=
       F       F
Bank Sta=0,9.5
XS Rating Curve= 0
Exp/Cntr=.3,.1

Type RM Length L Ch R = 1 ,7.037   ,50,50,50
#Sta/Elev= 10
   -11.9   23.55    -1.9   23.55      -1   24.35       0   24.35     2.7   22.45
     5.4   22.45     8.1   24.35    11.1   24.35    11.8   23.65    21.8   23.65
#Mann= 3 , 0 , 0
   -11.9    .035       0       0    .035       0     8.1    .035       0
Levee=-1,0,30,-1,8.1,30,,
#XS Ineff= 2 , 0
               0   24.35     8.1           24.35
Permanent Ineff=
       F       F
Bank Sta=0,8.1
XS Rating Curve= 0
Exp/Cntr=.3,.1

Type RM Length L Ch R = 1 ,7.036   ,36,36,36
#Sta/Elev= 12
   -11.9   23.55    -1.9   23.55      -1   24.35       0   24.35     2.7   22.45
     2.7   21.45     5.4   21.45     5.4   22.45     8.1   24.35    11.1   24.35
    11.8   23.65    21.8   23.65
#Mann= 3 , 0 , 0
   -11.9    .035       0       0    .035       0     8.1    .035       0
Levee=-1,0,30,-1,8.1,30,,
#XS Ineff= 2 , 0
               0   24.35     8.1           24.35
Permanent Ineff=
       F       F
Bank Sta=0,8.1
XS Rating Curve= 0
Exp/Cntr=.3,.1

Type RM Length L Ch R = 1 ,7       ,50,50,50
#Sta/Elev= 12
   -11.5   22.36    -1.5   22.36      -1   22.86       0   22.86     1.6   21.26
     3.8   21.26     4.1   22.16     5.4   22.46     6.5   23.16    10.3   23.16
    10.7   22.76    20.7   22.76
#Mann= 3 , 0 , 0
   -11.5    .035       0       0    .035       0     6.5    .035       0
Levee=-1,0,30,-1,6.5,30,,
#XS Ineff= 2 , 0
               0   22.86     6.5           23.16
Permanent Ineff=
       F       F
Bank Sta=0,6.5
XS Rating Curve= 0
Exp/Cntr=.3,.1

Type RM Length L Ch R = 1 ,6       ,33,33,33
#Sta/Elev= 12
   -11.5   22.03    -1.5   22.03      -1   22.53       0   22.53     1.5   21.03
     3.7   21.03       4   21.93     5.3   22.83     6.4   23.53    10.2   23.53
    10.6   23.13    20.6   23.13
#Mann= 3 , 0 , 0
   -11.5    .035       0       0    .035       0     6.4    .035       0
Levee=-1,0,30,-1,6.4,30,,
#XS Ineff= 2 , 0
               0   22.53     6.4           23.53
Permanent Ineff=
       F       F
Bank Sta=0,6.4
XS Rating Curve= 0
Exp/Cntr=.3,.1

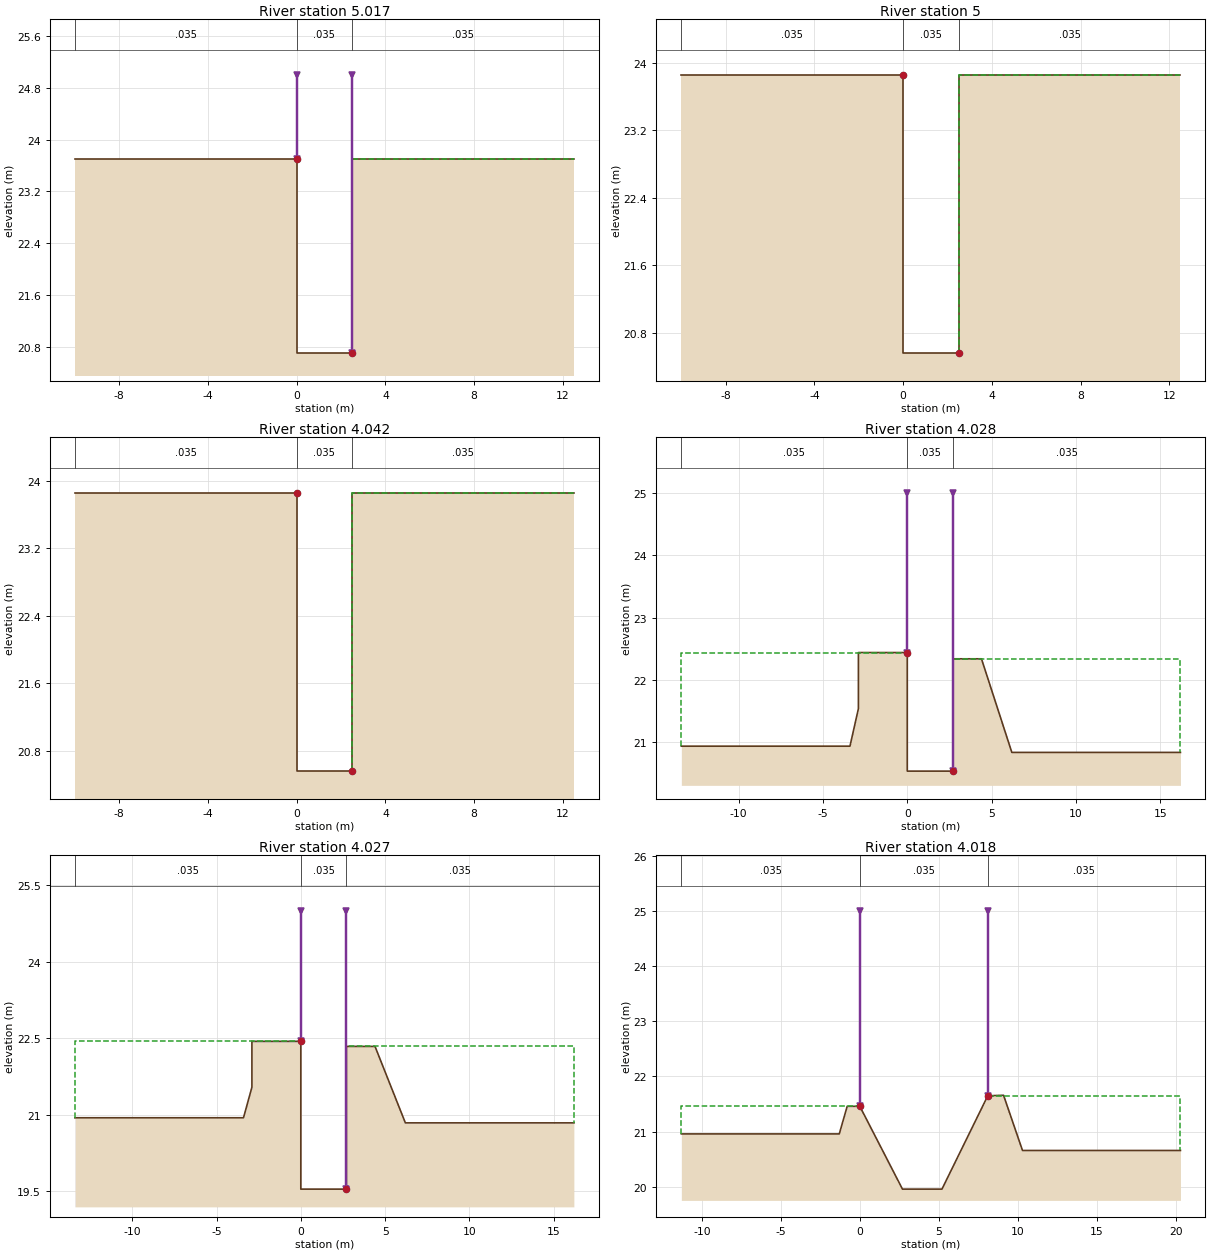
Type RM Length L Ch R = 1 ,5.017   ,17,17,17
#Sta/Elev= 6
     -10    23.7       0    23.7       0    20.7     2.5    20.7     2.5    23.7
    12.5    23.7
#Mann= 3 , 0 , 0
     -10    .035       0       0    .035       0     2.5    .035       0
Levee=-1,0,25,-1,2.5,25,,
#XS Ineff= 2 , 0
               0    23.7     2.5            23.7
Permanent Ineff=
       F       F
Bank Sta=0,2.5
XS Rating Curve= 0
Exp/Cntr=.3,.1

Type RM Length L Ch R = 1 ,5       ,8,8,8
#Sta/Elev= 6
     -10   23.86       0   23.86       0   20.56     2.5   20.56     2.5   23.86
    12.5   23.86
#Mann= 3 , 0 , 0
     -10    .035       0       0    .035       0     2.5    .035       0
#XS Ineff= 2 , 0
               0   23.86     2.5           23.86
Permanent Ineff=
       F       F
Bank Sta=0,2.5
XS Rating Curve= 0
Exp/Cntr=.3,.1

Type RM Length L Ch R = 1 ,4.042   ,14,14,14
#Sta/Elev= 6
     -10   23.86       0   23.86       0   20.56     2.5   20.56     2.5   23.86
    12.5   23.86
#Mann= 3 , 0 , 0
     -10    .035       0       0    .035       0     2.5    .035       0
#XS Ineff= 2 , 0
               0   23.86     2.5           23.86
Permanent Ineff=
       F       F
Bank Sta=0,2.5
XS Rating Curve= 0
Exp/Cntr=.3,.1

Type RM Length L Ch R = 1 ,4.028   ,1,1,1
#Sta/Elev= 11
   -13.4   20.94    -3.4   20.94    -2.9   21.54    -2.9   22.44       0   22.44
       0   20.54     2.7   20.54     2.7   22.34     4.4   22.34     6.2   20.84
    16.2   20.84
#Mann= 3 , 0 , 0
   -13.4    .035       0       0    .035       0     2.7    .035       0
Levee=-1,0,25,-1,2.7,25,,
#XS Ineff= 2 , 0
               0   22.44     2.7           22.34
Permanent Ineff=
       F       F
Bank Sta=0,2.7
XS Rating Curve= 0
Exp/Cntr=.3,.1

Type RM Length L Ch R = 1 ,4.027   ,9,9,9
#Sta/Elev= 13
   -13.4   20.94    -3.4   20.94    -2.9   21.54    -2.9   22.44       0   22.44
       0   20.54       0   19.54     2.7   19.54     2.7   20.54     2.7   22.34
     4.4   22.34     6.2   20.84    16.2   20.84
#Mann= 3 , 0 , 0
   -13.4    .035       0       0    .035       0     2.7    .035       0
Levee=-1,0,25,-1,2.7,25,,
#XS Ineff= 2 , 0
               0   22.44     2.7           22.34
Permanent Ineff=
       F       F
Bank Sta=0,2.7
XS Rating Curve= 0
Exp/Cntr=.3,.1

Type RM Length L Ch R = 1 ,4.018   ,18,18,18
#Sta/Elev= 10
   -11.3   20.96    -1.3   20.96     -.8   21.46       0   21.46     2.7   19.96
     5.2   19.96     8.1   21.65     9.1   21.66    10.3   20.66    20.3   20.66
#Mann= 3 , 0 , 0
   -11.3    .035       0       0    .035       0     8.1    .035       0
Levee=-1,0,25,-1,8.1,25,,
#XS Ineff= 2 , 0
               0   21.46     8.1           21.65
Permanent Ineff=
       F       F
Bank Sta=0,8.1
XS Rating Curve= 0
Exp/Cntr=.3,.1

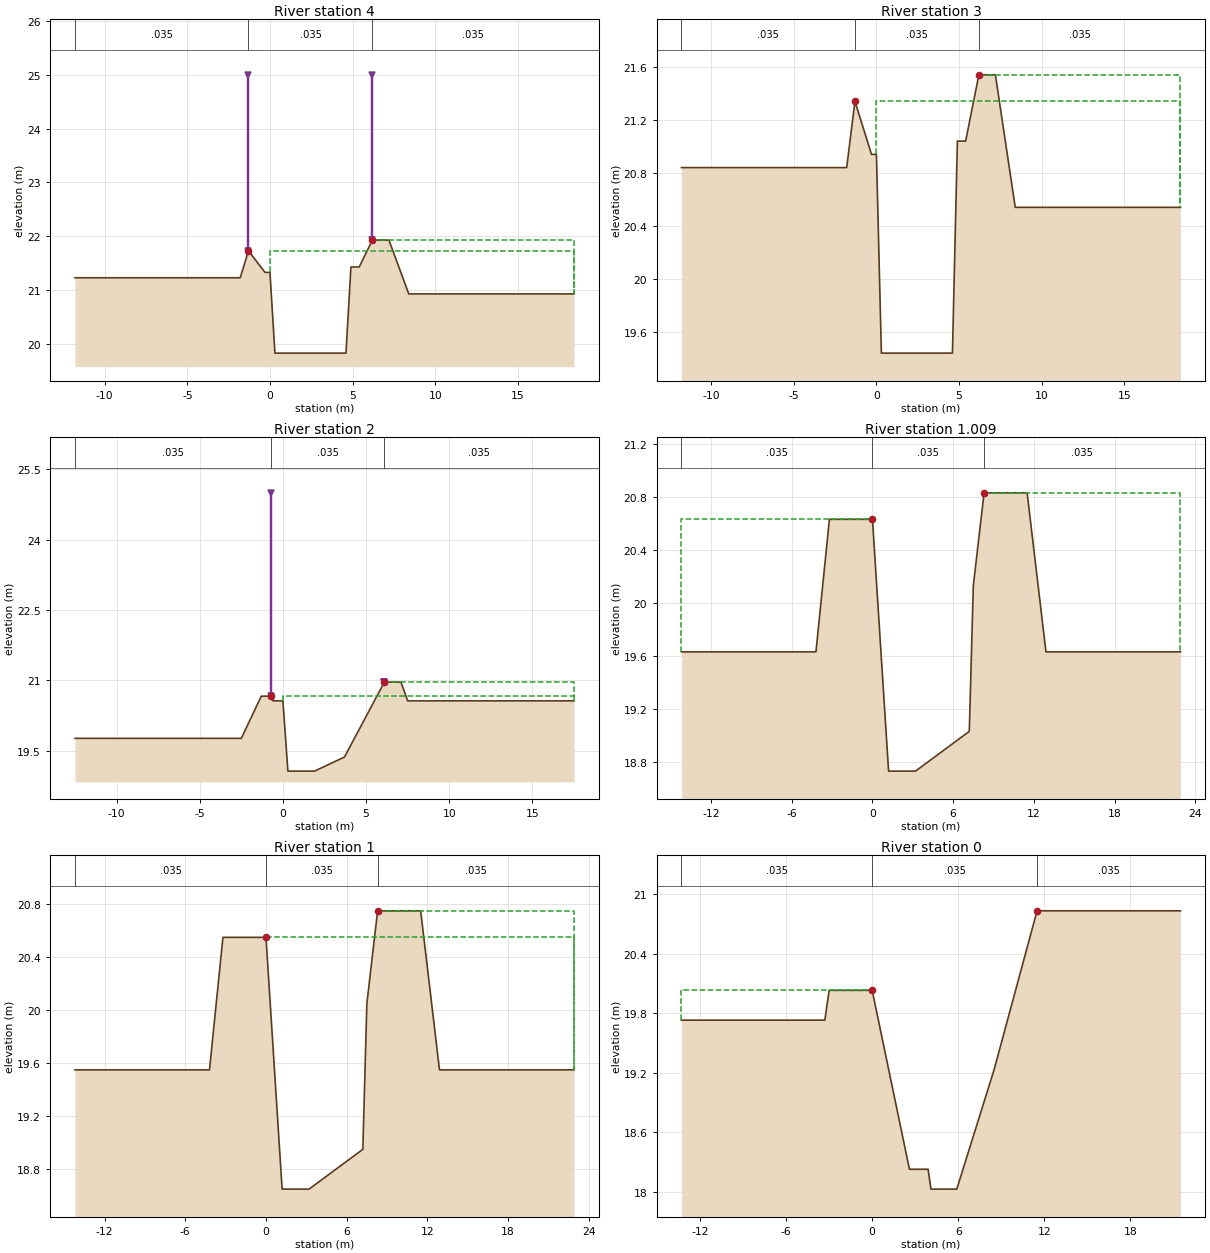
Type RM Length L Ch R = 1 ,4       ,50,50,50
#Sta/Elev= 13
   -11.8   21.23    -1.8   21.23    -1.3   21.73     -.3   21.33       0   21.33
      .3   19.83     4.6   19.83     4.9   21.43     5.4   21.43     6.2   21.93
     7.2   21.93     8.4   20.93    18.4   20.93
#Mann= 3 , 0 , 0
   -11.8    .035       0    -1.3    .035       0     6.2    .035       0
Levee=-1,-1.3,25,-1,6.2,25,,
#XS Ineff= 2 , 0
       0    -1.3   21.73     6.2       0   21.93
Permanent Ineff=
       F       F
Bank Sta=-1.3,6.2
XS Rating Curve= 0
Exp/Cntr=.3,.1

Type RM Length L Ch R = 1 ,3       ,50,50,50
#Sta/Elev= 13
   -11.8   20.84    -1.8   20.84    -1.3   21.34     -.3   20.94       0   20.94
      .3   19.44     4.6   19.44     4.9   21.04     5.4   21.04     6.2   21.54
     7.2   21.54     8.4   20.54    18.4   20.54
#Mann= 3 , 0 , 0
   -11.8    .035       0    -1.3    .035       0     6.2    .035       0
#XS Ineff= 2 , 0
       0    -1.3   21.34     6.2       0   21.54
Permanent Ineff=
       F       F
Bank Sta=-1.3,6.2
XS Rating Curve= 0
Exp/Cntr=.3,.1

Type RM Length L Ch R = 1 ,2       ,41,41,41
#Sta/Elev= 13
   -12.5   19.76    -2.5   19.76    -1.3   20.66     -.7   20.66     -.6   20.56
       0   20.56      .3   19.06     1.9   19.06     3.7   19.36     6.1   20.96
     7.1   20.96     7.5   20.56    17.5   20.56
#Mann= 3 , 0 , 0
   -12.5    .035       0     -.7    .035       0     6.1    .035       0
Levee=-1,-.7,25,-1,6.1,20.96,,
#XS Ineff= 2 , 0
       0     -.7   20.66     6.1       0   20.96
Permanent Ineff=
       F       F
Bank Sta=-.7,6.1
XS Rating Curve= 0
Exp/Cntr=.3,.1

Type RM Length L Ch R = 1 ,1.009   ,9,9,9
#Sta/Elev= 12
   -14.2   19.63    -4.2   19.63    -3.2   20.63       0   20.63     1.2   18.73
     3.2   18.73     7.2   19.03     7.5   20.13     8.3   20.83    11.5   20.83
    12.9   19.63    22.9   19.63
#Mann= 3 , 0 , 0
   -14.2    .035       0       0    .035       0     8.3    .035       0
#XS Ineff= 2 , 0
               0   20.63     8.3           20.83
Permanent Ineff=
       F       F
Bank Sta=0,8.3
XS Rating Curve= 0
Exp/Cntr=.3,.1

Type RM Length L Ch R = 1 ,1       ,50,50,50
#Sta/Elev= 12
   -14.2   19.55    -4.2   19.55    -3.2   20.55       0   20.55     1.2   18.65
     3.2   18.65     7.2   18.95     7.5   20.05     8.3   20.75    11.5   20.75
    12.9   19.55    22.9   19.55
#Mann= 3 , 0 , 0
   -14.2    .035       0       0    .035       0     8.3    .035       0
#XS Ineff= 2 , 0
       0       0   20.55     8.3       0   20.75
Permanent Ineff=
       F       F
Bank Sta=0,8.3
XS Rating Curve= 0
Exp/Cntr=.3,.1

Type RM Length L Ch R = 1 ,0       ,0,0,0
#Sta/Elev= 11
   -13.3   19.73    -3.3   19.73      -3   20.03       0   20.03     2.6   18.23
     3.9   18.23     4.1   18.03     5.9   18.03     8.5   19.23    11.5   20.83
    21.5   20.83
#Mann= 3 , 0 , 0
   -13.3    .035       0       0    .035       0    11.5    .035       0
#XS Ineff= 2 , 0
               0   20.03    11.5           20.83
Permanent Ineff=
       F       F
Bank Sta=0,11.5
XS Rating Curve= 0
Exp/Cntr=.3,.1

Chan Stop Cuts=-1