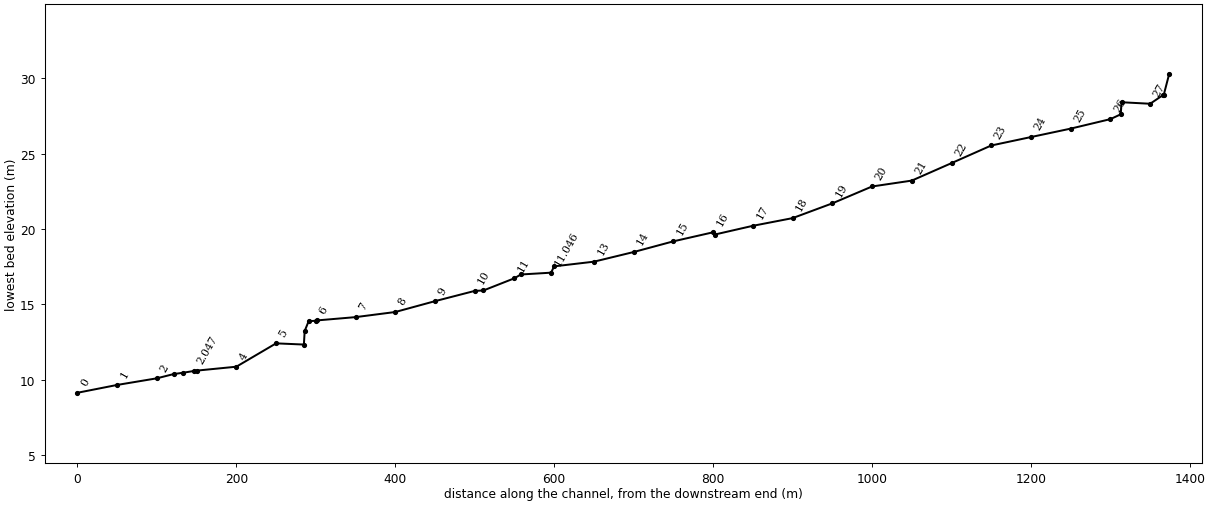
--- wdc.prj (project) ---

Proj Title=wondo-ch
Current Plan=p01
Default Exp/Contr=.3,.1
SI Units
Geom File=g01
Flow File=f01
Plan File=p01
Y Axis Title=Elevation
X Axis Title(PF)=Main Channel Distance
X Axis Title(XS)=Station
BEGIN DESCRIPTION:
           BACK WATER COMPUTATION
      APPLICATION OF HEC-2 BY Samju Construction Engineering
      wondo-ch: 10,20,30,50,80 yr
END DESCRIPTION:
DSS Export Rating Curves= 0
DSS Export Rating Curve Sorted= 0
DSS Export Volume Flow Curves= 0
DXF OffsetX= 0
DXF OffsetY= 0
DXF ScaleX= 1
DXF ScaleY= 10

--- wdc.p01 (plan) ---

Plan Title=Imported Plan 01
Version=Version 3.0.1  Mar 2001
Short Identifier=Imported Pla
Geom File=g01
Flow File=f01
Subcritical Flow
K Sum by GR= 0
Std Step Tol= 0.003
Critical Tol= 0.003
Num of Std Step Trials= 20
Max Error Tol= 0.1
Flow Tol Ratio= 0.001
Split Flow NTrial= 30
Split Flow Tol= 0.02
Split Flow Ratio= 0.02
Log Output Level= 0
Friction Slope Method= 1
Unsteady Friction Slope Method= 2
Parabolic Critical Depth
Global Vel Dist= 0 , 0 , 0
Global Log Level= 0
CheckData=True
Encroach Param=-1 ,0,0, 0
Computation Interval=1HOUR
Output Interval=1HOUR
Run HTab= 0
Run UNet= 0
Run PostProcess= 0
UNET Theta= 1
UNET ZTol= 0.02
UNET ZSATol= 0.1
UNET MxIter= 20
UNET MaxInSteps= 20
UNET DtIC= 0
UNET DtMin= 0
UNET MaxCRTS= 20
UNET WFStab= 2
UNET SFStab= 1
UNET WFX= 1
UNET SFX= 1
UNET Convert EG Bridges=-1
UNET Use Existing IB Tables=-1
Instantaneous Interval=1HOUR
Write IC File= 0
Write Velocity= 0
Write Detailed= 0

--- wdc.f01 (steady flow) ---

Flow Title=Imported Flow 01
Version=Version 3.0.1  Mar 2001
Number of Profiles= 5
Profile Names=10yr,20yr,30yr,50yr,80yr
River Rch & RM=RIVER-1,Reach-1         ,27.024
   17.79   19.38   20.43   21.75   22.97
Boundary for River Rch & Prof#=RIVER-1,Reach-1         , 1
Up Type= 0
Dn Type= 3
Dn Slope=.015
Boundary for River Rch & Prof#=RIVER-1,Reach-1         , 2
Up Type= 0
Dn Type= 3
Dn Slope=.015
Boundary for River Rch & Prof#=RIVER-1,Reach-1         , 3
Up Type= 0
Dn Type= 3
Dn Slope=.015
Boundary for River Rch & Prof#=RIVER-1,Reach-1         , 4
Up Type= 0
Dn Type= 3
Dn Slope=.015
Boundary for River Rch & Prof#=RIVER-1,Reach-1         , 5
Up Type= 0
Dn Type= 3
Dn Slope=.015
DSS Import GetInterval= 0
DSS Import GetPeak= 0
DSS Import FillOption= 0

--- wdc.g01 (geometry) ---

Geom Title=Imported Geom 01
Version=Version 3.0.1  Mar 2001

River Reach=RIVER-1         ,Reach-1
Reach XY= 2
              .5             .95              .5             .05

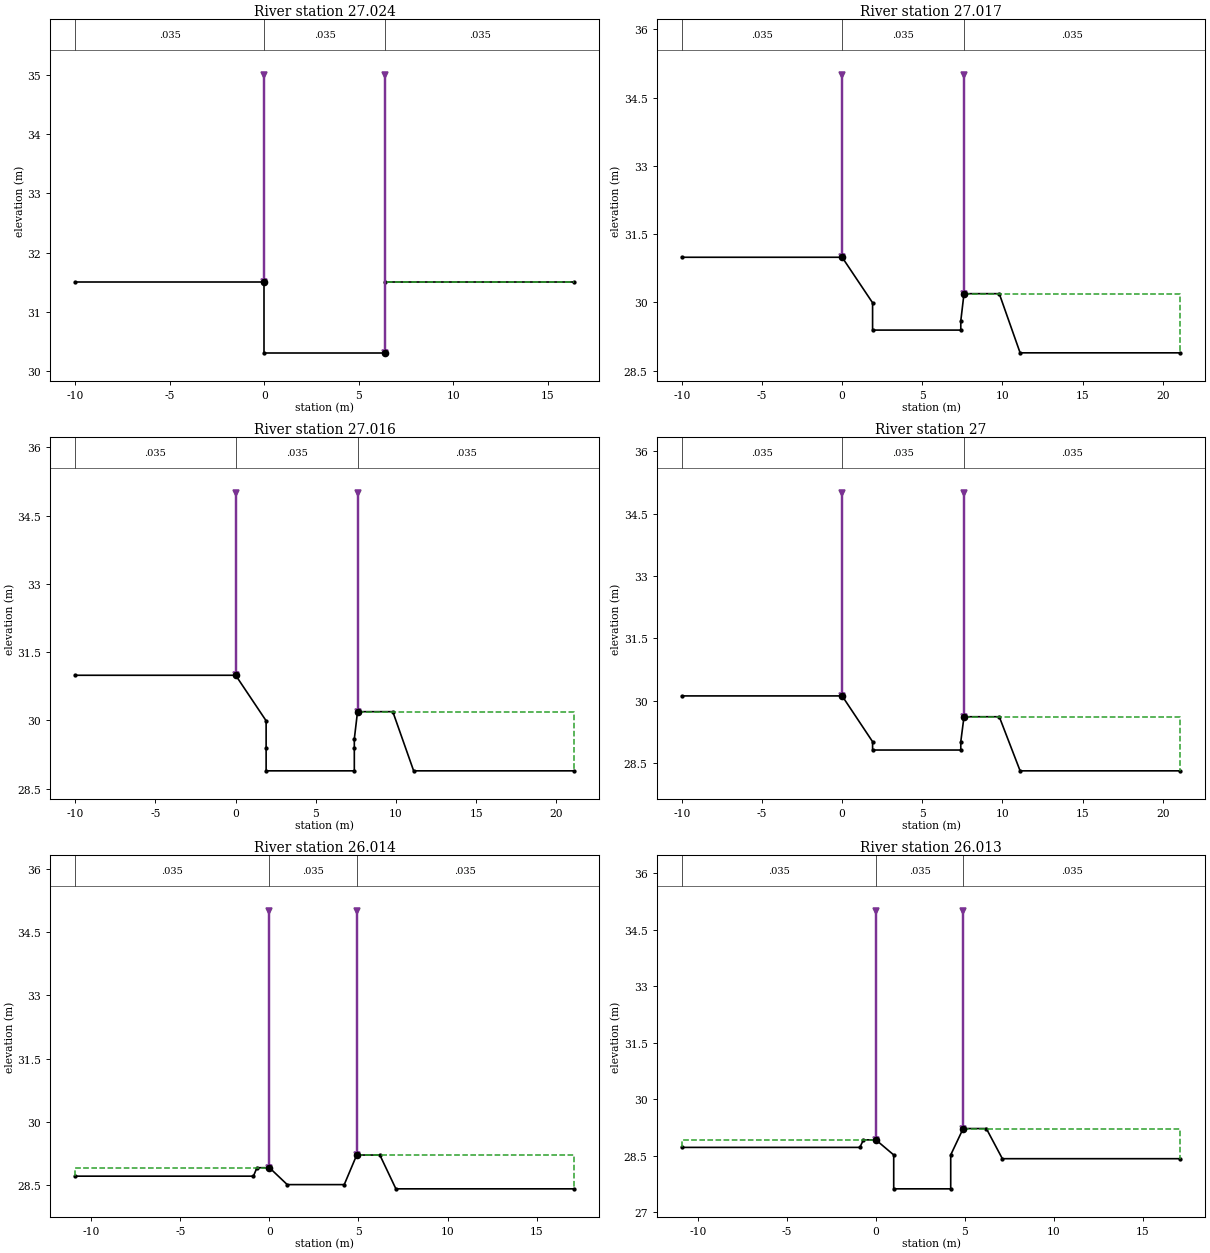
Type RM Length L Ch R = 1 ,27.024  ,7,7,7
#Sta/Elev= 6
     -10   31.51       0   31.51       0   30.31     6.4   30.31     6.4   31.51
    16.4   31.51
#Mann= 3 , 0 , 0
     -10    .035       0       0    .035       0     6.4    .035       0
Levee=-1,0,35,-1,6.4,35,,
#XS Ineff= 2 , 0
               0   31.51     6.4           31.51
Permanent Ineff=
       F       F
Bank Sta=0,6.4
XS Rating Curve= 0
Exp/Cntr=.3,.1

Type RM Length L Ch R = 1 ,27.017  ,1,1,1
#Sta/Elev= 10
     -10   30.99       0   30.99     1.9   29.99     1.9   29.39     7.4   29.39
     7.4   29.59     7.6   30.19     9.8   30.19    11.1   28.89    21.1   28.89
#Mann= 3 , 0 , 0
     -10    .035       0       0    .035       0     7.6    .035       0
Levee=-1,0,35,-1,7.6,35,,
#XS Ineff= 2 , 0
               0   30.99     7.6           30.19
Permanent Ineff=
       F       F
Bank Sta=0,7.6
XS Rating Curve= 0
Exp/Cntr=.3,.1

Type RM Length L Ch R = 1 ,27.016  ,16,16,16
#Sta/Elev= 12
     -10   30.99       0   30.99     1.9   29.99     1.9   29.39     1.9   28.89
     7.4   28.89     7.4   29.39     7.4   29.59     7.6   30.19     9.8   30.19
    11.1   28.89    21.1   28.89
#Mann= 3 , 0 , 0
     -10    .035       0       0    .035       0     7.6    .035       0
Levee=-1,0,35,-1,7.6,35,,
#XS Ineff= 2 , 0
               0   30.99     7.6           30.19
Permanent Ineff=
       F       F
Bank Sta=0,7.6
XS Rating Curve= 0
Exp/Cntr=.3,.1

Type RM Length L Ch R = 1 ,27      ,36,36,36
#Sta/Elev= 10
     -10   30.12       0   30.12     1.9   29.02     1.9   28.82     7.4   28.82
     7.4   29.02     7.6   29.62     9.8   29.62    11.1   28.32    21.1   28.32
#Mann= 3 , 0 , 0
     -10    .035       0       0    .035       0     7.6    .035       0
Levee=-1,0,35,-1,7.6,35,,
#XS Ineff= 2 , 0
               0   30.12     7.6           29.62
Permanent Ineff=
       F       F
Bank Sta=0,7.6
XS Rating Curve= 0
Exp/Cntr=.3,.1

Type RM Length L Ch R = 1 ,26.014  ,1,1,1
#Sta/Elev= 10
   -10.9   28.72     -.9   28.72     -.7   28.92       0   28.92       1   28.52
     4.2   28.52     4.9   29.22     6.2   29.22     7.1   28.42    17.1   28.42
#Mann= 3 , 0 , 0
   -10.9    .035       0       0    .035       0     4.9    .035       0
Levee=-1,0,35,-1,4.9,35,,
#XS Ineff= 2 , 0
               0   28.92     4.9           29.22
Permanent Ineff=
       F       F
Bank Sta=0,4.9
XS Rating Curve= 0
Exp/Cntr=.3,.1

Type RM Length L Ch R = 1 ,26.013  ,13,13,13
#Sta/Elev= 12
   -10.9   28.72     -.9   28.72     -.7   28.92       0   28.92       1   28.52
       1   27.62     4.2   27.62     4.2   28.52     4.9   29.22     6.2   29.22
     7.1   28.42    17.1   28.42
#Mann= 3 , 0 , 0
   -10.9    .035       0       0    .035       0     4.9    .035       0
Levee=-1,0,35,-1,4.9,35,,
#XS Ineff= 2 , 0
               0   28.92     4.9           29.22
Permanent Ineff=
       F       F
Bank Sta=0,4.9
XS Rating Curve= 0
Exp/Cntr=.3,.1

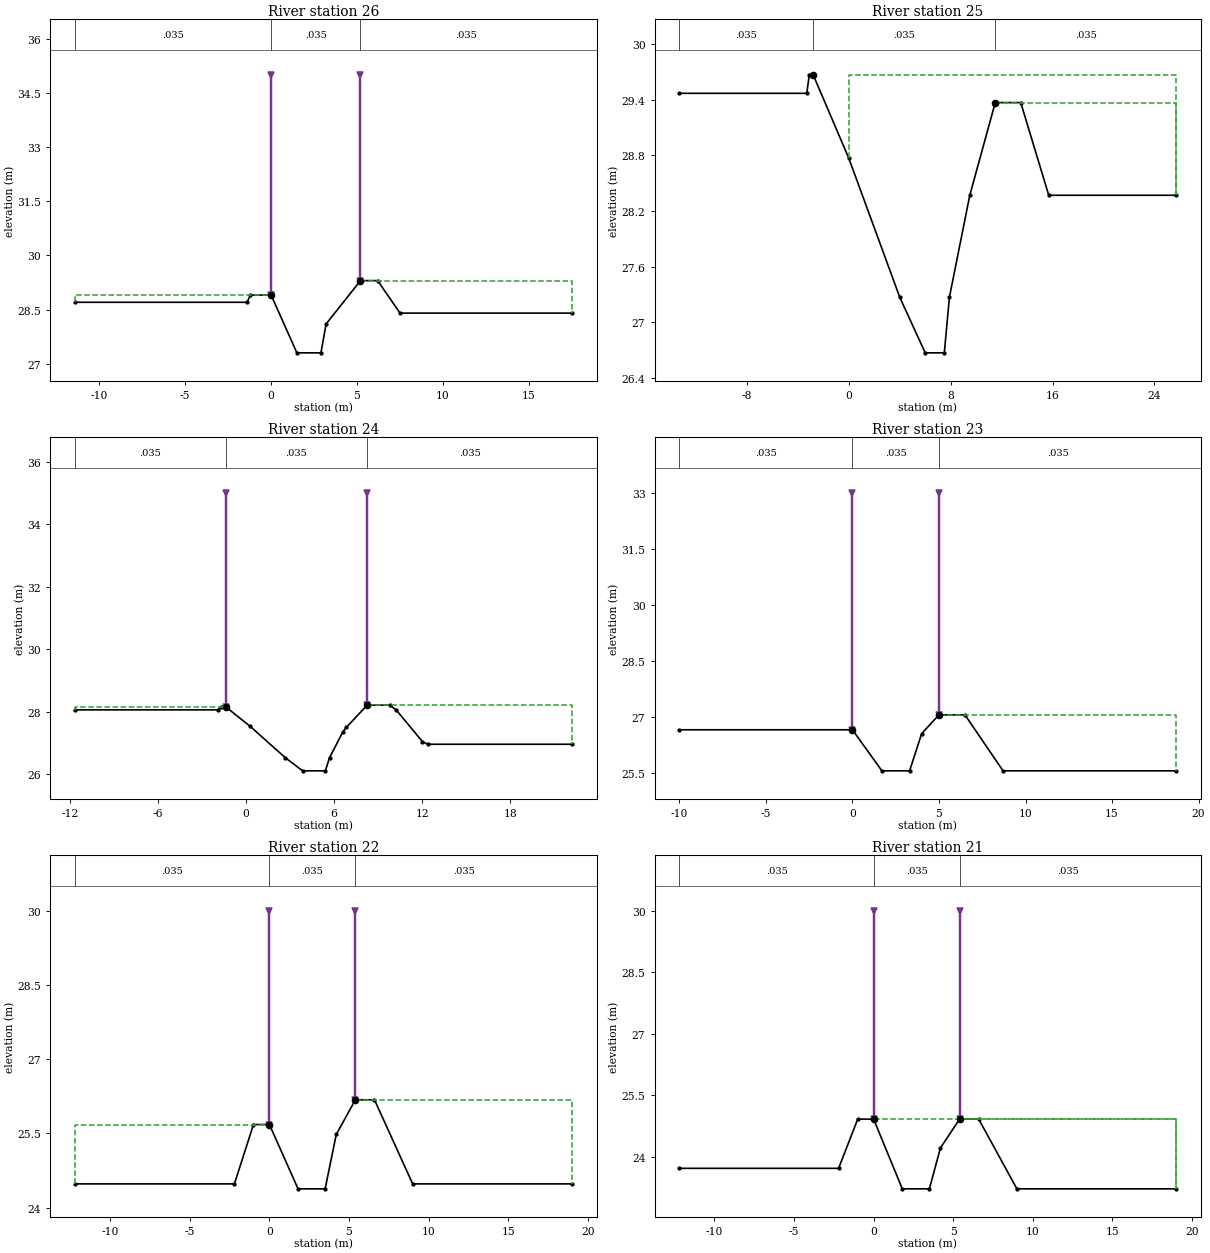
Type RM Length L Ch R = 1 ,26      ,50,50,50
#Sta/Elev= 11
   -11.4    28.7    -1.4    28.7    -1.2    28.9       0    28.9     1.5    27.3
     2.9    27.3     3.2    28.1     5.2    29.3     6.2    29.3     7.5    28.4
    17.5    28.4
#Mann= 3 , 0 , 0
   -11.4    .035       0       0    .035       0     5.2    .035       0
Levee=-1,0,35,-1,5.2,35,,
#XS Ineff= 2 , 0
               0    28.9     5.2            29.3
Permanent Ineff=
       F       F
Bank Sta=0,5.2
XS Rating Curve= 0
Exp/Cntr=.3,.1

Type RM Length L Ch R = 1 ,25      ,50,50,50
#Sta/Elev= 14
   -13.3   29.47    -3.3   29.47    -3.1   29.67    -2.8   29.67       0   28.77
       4   27.27       6   26.67     7.5   26.67     7.9   27.27     9.5   28.37
    11.5   29.37    13.5   29.37    15.7   28.37    25.7   28.37
#Mann= 3 , 0 , 0
   -13.3    .035       0    -2.8    .035       0    11.5    .035       0
#XS Ineff= 2 , 0
       0    -2.8   29.67    11.5       0   29.37
Permanent Ineff=
       F       F
Bank Sta=-2.8,11.5
XS Rating Curve= 0
Exp/Cntr=.3,.1

Type RM Length L Ch R = 1 ,24      ,50,50,50
#Sta/Elev= 17
  -11.65   28.06  -1.888   28.06  -1.693   28.16    -1.4   28.16     .27  27.535
   2.657  26.535    3.85   26.11     5.4   26.11   5.685  26.531   6.574  27.339
   6.825  27.498    8.25   28.21   9.777   28.21  10.215  28.064  12.018  27.043
  12.376   26.96    22.2   26.96
#Mann= 3 , 0 , 0
  -11.65    .035       0    -1.4    .035       0    8.25    .035       0
Levee=-1,-1.4,35,-1,8.25,35,,
#XS Ineff= 2 , 0
            -1.4   28.16    8.25           28.21
Permanent Ineff=
       F       F
Bank Sta=-1.4,8.25
XS Rating Curve= 0
Exp/Cntr=.3,.1

Type RM Length L Ch R = 1 ,23      ,50,50,50
#Sta/Elev= 9
     -10   26.65       0   26.65     1.7   25.55     3.3   25.55       4   26.55
       5   27.05     6.5   27.05     8.7   25.55    18.7   25.55
#Mann= 3 , 0 , 0
     -10    .035       0       0    .035       0       5    .035       0
Levee=-1,0,33,-1,5,33,,
#XS Ineff= 2 , 0
               0   26.65       5           27.05
Permanent Ineff=
       F       F
Bank Sta=0,5
XS Rating Curve= 0
Exp/Cntr=.3,.1

Type RM Length L Ch R = 1 ,22      ,50,50,50
#Sta/Elev= 11
   -12.2   24.48    -2.2   24.48      -1   25.68       0   25.68     1.8   24.38
     3.5   24.38     4.2   25.48     5.4   26.18     6.6   26.18       9   24.48
      19   24.48
#Mann= 3 , 0 , 0
   -12.2    .035       0       0    .035       0     5.4    .035       0
Levee=-1,0,30,-1,5.4,30,,
#XS Ineff= 2 , 0
               0   25.68     5.4           26.18
Permanent Ineff=
       F       F
Bank Sta=0,5.4
XS Rating Curve= 0
Exp/Cntr=.3,.1

Type RM Length L Ch R = 1 ,21      ,50,50,50
#Sta/Elev= 11
   -12.2   23.72    -2.2   23.72      -1   24.92       0   24.92     1.8   23.22
     3.5   23.22     4.2   24.22     5.4   24.92     6.6   24.92       9   23.22
      19   23.22
#Mann= 3 , 0 , 0
   -12.2    .035       0       0    .035       0     5.4    .035       0
Levee=-1,0,30,-1,5.4,30,,
#XS Ineff= 2 , 0
       0       0   24.92     5.4       0   24.92
Permanent Ineff=
       F       F
Bank Sta=0,5.4
XS Rating Curve= 0
Exp/Cntr=.3,.1

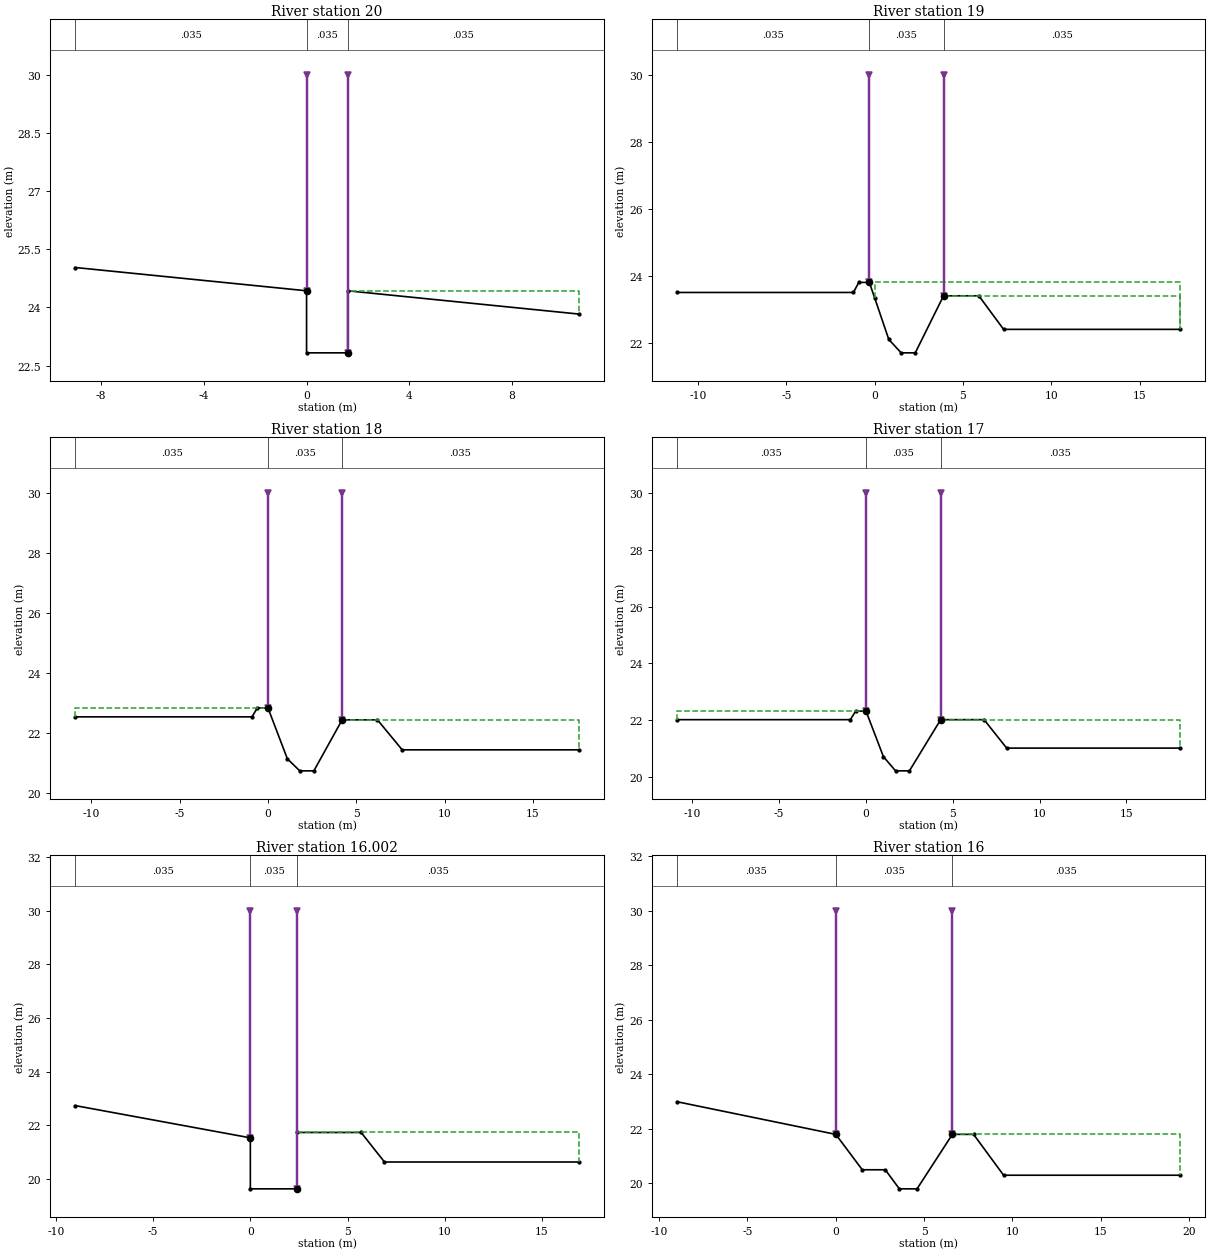
Type RM Length L Ch R = 1 ,20      ,50,50,50
#Sta/Elev= 6
      -9   25.03       0   24.43       0   22.83     1.6   22.83     1.6   24.43
    10.6   23.83
#Mann= 3 , 0 , 0
      -9    .035       0       0    .035       0     1.6    .035       0
Levee=-1,0,30,-1,1.6,30,,
#XS Ineff= 2 , 0
               0   24.43     1.6           24.43
Permanent Ineff=
       F       F
Bank Sta=0,1.6
XS Rating Curve= 0
Exp/Cntr=.3,.1

Type RM Length L Ch R = 1 ,19      ,50,50,50
#Sta/Elev= 12
   -11.2   23.51    -1.2   23.51     -.9   23.81     -.3   23.81       0   23.35
      .8   22.11     1.5   21.71     2.3   21.71     3.9   23.41     5.9   23.41
     7.3   22.41    17.3   22.41
#Mann= 3 , 0 , 0
   -11.2    .035       0     -.3    .035       0     3.9    .035       0
Levee=-1,-.3,30,-1,3.9,30,,
#XS Ineff= 2 , 0
       0     -.3   23.81     3.9       0   23.41
Permanent Ineff=
       F       F
Bank Sta=-.3,3.9
XS Rating Curve= 0
Exp/Cntr=.3,.1

Type RM Length L Ch R = 1 ,18      ,50,50,50
#Sta/Elev= 11
   -10.9   22.53     -.9   22.53     -.6   22.83       0   22.83     1.1   21.13
     1.8   20.73     2.6   20.73     4.2   22.43     6.2   22.43     7.6   21.43
    17.6   21.43
#Mann= 3 , 0 , 0
   -10.9    .035       0       0    .035       0     4.2    .035       0
Levee=-1,0,30,-1,4.2,30,,
#XS Ineff= 2 , 0
               0   22.83     4.2           22.43
Permanent Ineff=
       F       F
Bank Sta=0,4.2
XS Rating Curve= 0
Exp/Cntr=.3,.1

Type RM Length L Ch R = 1 ,17      ,48,48,48
#Sta/Elev= 11
   -10.9   22.02     -.9   22.02     -.6   22.32       0   22.32       1   20.72
     1.7   20.22     2.5   20.22     4.3   22.02     6.8   22.02     8.1   21.02
    18.1   21.02
#Mann= 3 , 0 , 0
   -10.9    .035       0       0    .035       0     4.3    .035       0
Levee=-1,0,30,-1,4.3,30,,
#XS Ineff= 2 , 0
               0   22.32     4.3           22.02
Permanent Ineff=
       F       F
Bank Sta=0,4.3
XS Rating Curve= 0
Exp/Cntr=.3,.1

Type RM Length L Ch R = 1 ,16.002  ,2,2,2
#Sta/Elev= 8
      -9   22.74       0   21.54       0   19.64     2.4   19.64     2.4   21.74
     5.7   21.74     6.9   20.64    16.9   20.64
#Mann= 3 , 0 , 0
      -9    .035       0       0    .035       0     2.4    .035       0
Levee=-1,0,30,-1,2.4,30,,
#XS Ineff= 2 , 0
               0   21.54     2.4           21.74
Permanent Ineff=
       F       F
Bank Sta=0,2.4
XS Rating Curve= 0
Exp/Cntr=.3,.1

Type RM Length L Ch R = 1 ,16      ,50,50,50
#Sta/Elev= 10
      -9   22.99       0   21.79     1.5   20.49     2.8   20.49     3.6   19.79
     4.6   19.79     6.6   21.79     7.8   21.79     9.5   20.29    19.5   20.29
#Mann= 3 , 0 , 0
      -9    .035       0       0    .035       0     6.6    .035       0
Levee=-1,0,30,-1,6.6,30,,
#XS Ineff= 2 , 0
               0   21.79     6.6           21.79
Permanent Ineff=
       F       F
Bank Sta=0,6.6
XS Rating Curve= 0
Exp/Cntr=.3,.1

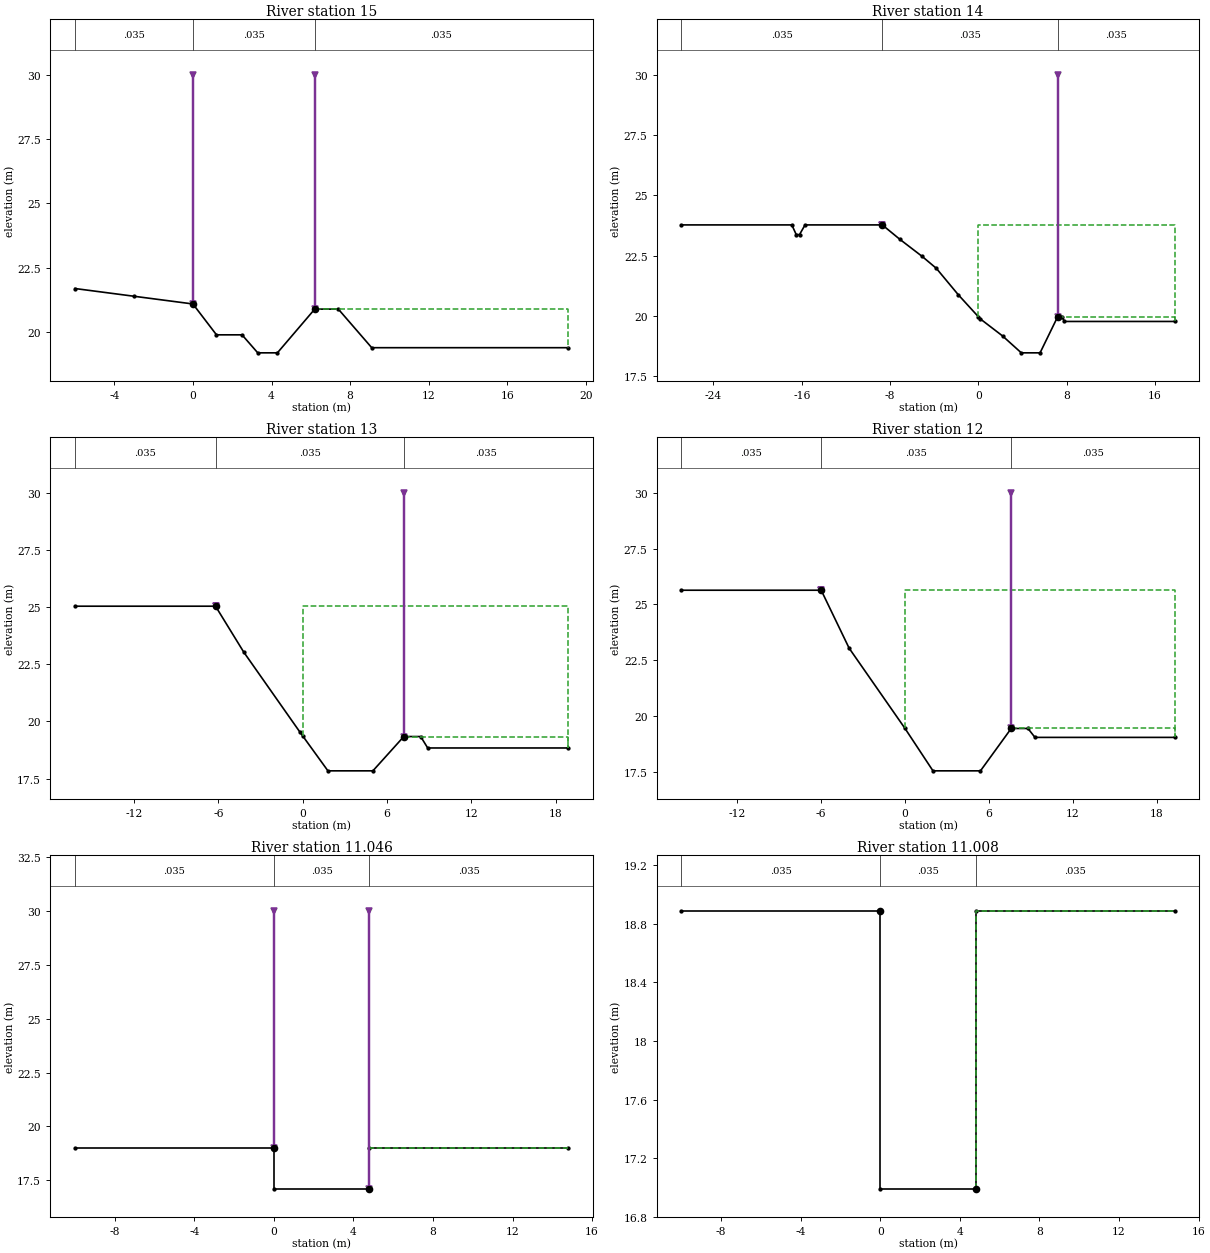
Type RM Length L Ch R = 1 ,15      ,50,50,50
#Sta/Elev= 11
      -6   21.69      -3   21.39       0   21.09     1.2   19.89     2.5   19.89
     3.3   19.19     4.3   19.19     6.2   20.89     7.4   20.89     9.1   19.39
    19.1   19.39
#Mann= 3 , 0 , 0
      -6    .035       0       0    .035       0     6.2    .035       0
Levee=-1,0,30,-1,6.2,30,,
#XS Ineff= 2 , 0
               0   21.09     6.2           20.89
Permanent Ineff=
       F       F
Bank Sta=0,6.2
XS Rating Curve= 0
Exp/Cntr=.3,.1

Type RM Length L Ch R = 1 ,14      ,50,50,50
#Sta/Elev= 19
   -26.9   23.78   -16.9   23.78   -16.5   23.38   -16.2   23.38   -15.7   23.78
    -8.7   23.78    -7.1   23.18    -5.1   22.48    -3.8   21.98    -1.8   20.88
       0   19.98      .2   19.88     2.2   19.18     3.9   18.48     5.6   18.48
     7.2   19.98     7.6   19.98     7.8   19.78    17.8   19.78
#Mann= 3 , 0 , 0
   -26.9    .035       0    -8.7    .035       0     7.2    .035       0
Levee=-1,-8.7,23.78,-1,7.2,30,,
#XS Ineff= 2 , 0
       0    -8.7   23.78     7.2       0   19.98
Permanent Ineff=
       F       F
Bank Sta=-8.7,7.2
XS Rating Curve= 0
Exp/Cntr=.3,.1

Type RM Length L Ch R = 1 ,13      ,50,50,50
#Sta/Elev= 11
   -16.2   25.04    -6.2   25.04    -4.2   23.04     -.2   19.54       0   19.37
     1.8   17.84       5   17.84     7.2   19.34     8.4   19.34     8.9   18.84
    18.9   18.84
#Mann= 3 , 0 , 0
   -16.2    .035       0    -6.2    .035       0     7.2    .035       0
Levee=-1,-6.2,25.04,-1,7.2,30,,
#XS Ineff= 2 , 0
       0    -6.2   25.04     7.2       0   19.34
Permanent Ineff=
       F       F
Bank Sta=-6.2,7.2
XS Rating Curve= 0
Exp/Cntr=.3,.1

Type RM Length L Ch R = 1 ,12      ,4,4,4
#Sta/Elev= 10
     -16   25.63      -6   25.63      -4   23.03       0   19.43       2   17.53
     5.4   17.53     7.6   19.43     8.8   19.43     9.3   19.03    19.3   19.03
#Mann= 3 , 0 , 0
     -16    .035       0      -6    .035       0     7.6    .035       0
Levee=-1,-6,25.63,-1,7.6,30,,
#XS Ineff= 2 , 0
       0      -6   25.63     7.6       0   19.43
Permanent Ineff=
       F       F
Bank Sta=-6,7.6
XS Rating Curve= 0
Exp/Cntr=.3,.1

Type RM Length L Ch R = 1 ,11.046  ,38,38,38
#Sta/Elev= 6
     -10   19.01       0   19.01       0   17.11     4.8   17.11     4.8   19.01
    14.8   19.01
#Mann= 3 , 0 , 0
     -10    .035       0       0    .035       0     4.8    .035       0
Levee=-1,0,30,-1,4.8,30,,
#XS Ineff= 2 , 0
               0   19.01     4.8           19.01
Permanent Ineff=
       F       F
Bank Sta=0,4.8
XS Rating Curve= 0
Exp/Cntr=.3,.1

Type RM Length L Ch R = 1 ,11.008  ,8,8,8
#Sta/Elev= 6
     -10   18.89       0   18.89       0   16.99     4.8   16.99     4.8   18.89
    14.8   18.89
#Mann= 3 , 0 , 0
     -10    .035       0       0    .035       0     4.8    .035       0
#XS Ineff= 2 , 0
               0   18.89     4.8           18.89
Permanent Ineff=
       F       F
Bank Sta=0,4.8
XS Rating Curve= 0
Exp/Cntr=.3,.1

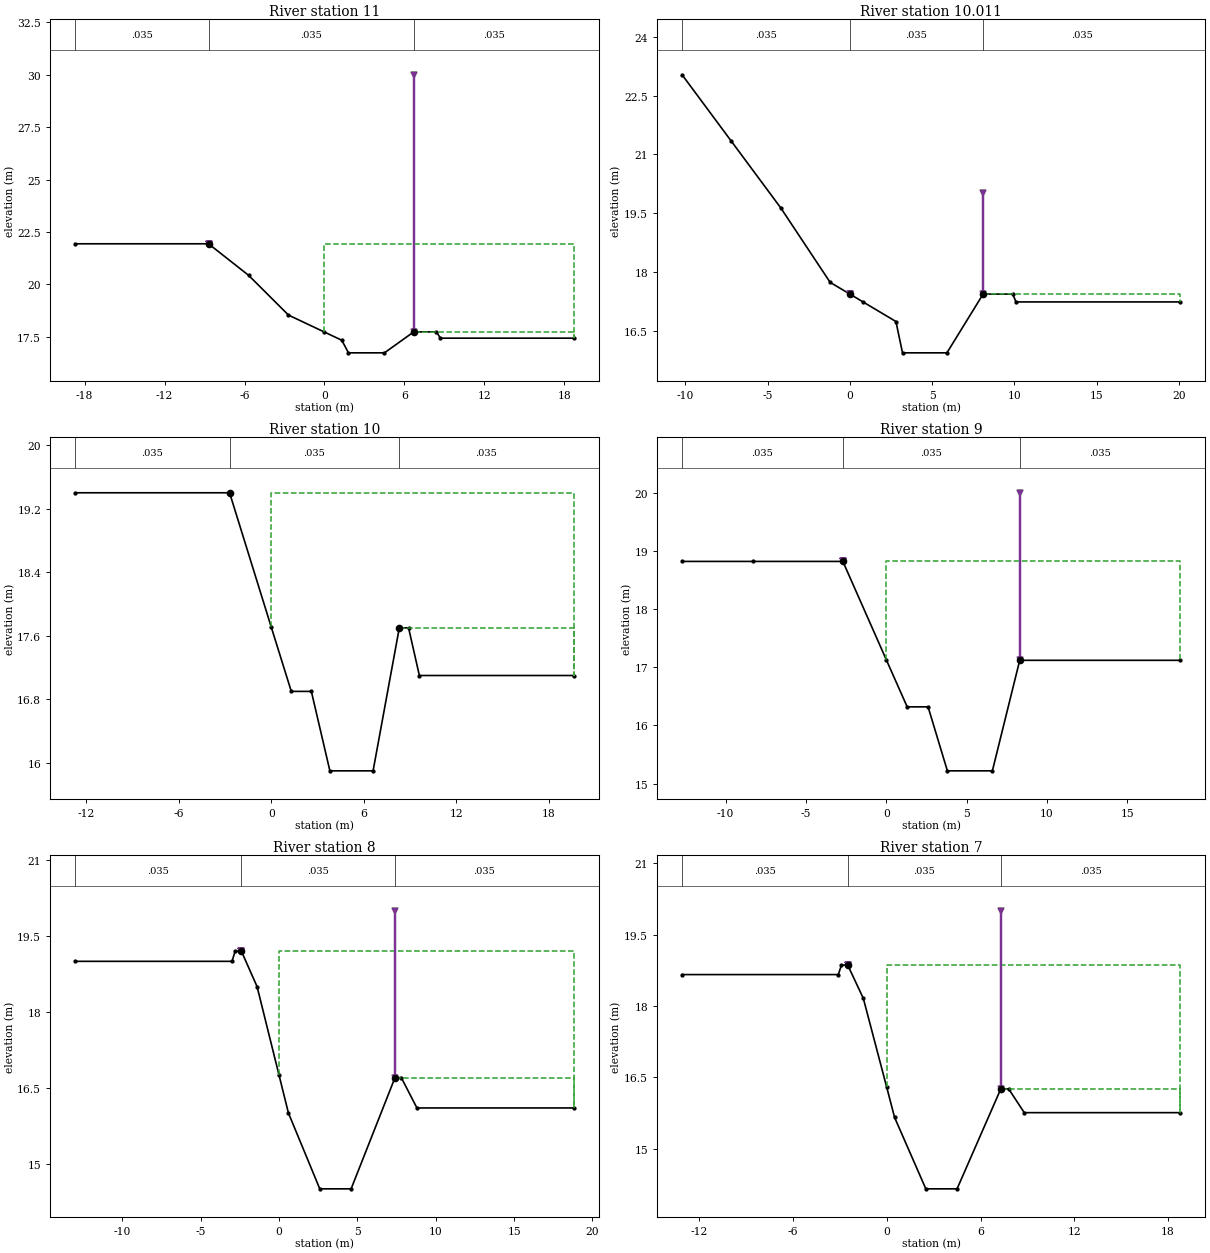
Type RM Length L Ch R = 1 ,11      ,39,39,39
#Sta/Elev= 12
   -18.7   21.94    -8.7   21.94    -5.7   20.44    -2.7   18.54       0   17.73
     1.3   17.34     1.8   16.74     4.5   16.74     6.7   17.74     8.4   17.74
     8.7   17.44    18.7   17.44
#Mann= 3 , 0 , 0
   -18.7    .035       0    -8.7    .035       0     6.7    .035       0
Levee=-1,-8.7,21.94,-1,6.7,30,,
#XS Ineff= 2 , 0
       0    -8.7   21.94     6.7       0   17.74
Permanent Ineff=
       F       F
Bank Sta=-8.7,6.7
XS Rating Curve= 0
Exp/Cntr=.3,.1

Type RM Length L Ch R = 1 ,10.011  ,11,11,11
#Sta/Elev= 13
   -10.2   23.03    -7.2   21.33    -4.2   19.63    -1.2   17.73       0   17.43
      .8   17.23     2.8   16.73     3.2   15.93     5.9   15.93     8.1   17.43
     9.9   17.43    10.1   17.23    20.1   17.23
#Mann= 3 , 0 , 0
   -10.2    .035       0       0    .035       0     8.1    .035       0
Levee=-1,0,17.43,-1,8.1,20,,
#XS Ineff= 2 , 0
               0   17.43     8.1           17.43
Permanent Ineff=
       F       F
Bank Sta=0,8.1
XS Rating Curve= 0
Exp/Cntr=.3,.1

Type RM Length L Ch R = 1 ,10      ,50,50,50
#Sta/Elev= 11
   -12.7    19.4    -2.7    19.4       0   17.71     1.3    16.9     2.6    16.9
     3.8    15.9     6.6    15.9     8.3    17.7     8.9    17.7     9.6    17.1
    19.6    17.1
#Mann= 3 , 0 , 0
   -12.7    .035       0    -2.7    .035       0     8.3    .035       0
#XS Ineff= 2 , 0
       0    -2.7    19.4     8.3       0    17.7
Permanent Ineff=
       F       F
Bank Sta=-2.7,8.3
XS Rating Curve= 0
Exp/Cntr=.3,.1

Type RM Length L Ch R = 1 ,9       ,50,50,50
#Sta/Elev= 10
   -12.7   18.82    -8.3   18.82    -2.7   18.82       0   17.13     1.3   16.32
     2.6   16.32     3.8   15.22     6.6   15.22     8.3   17.12    18.3   17.12
#Mann= 3 , 0 , 0
   -12.7    .035       0    -2.7    .035       0     8.3    .035       0
Levee=-1,-2.7,18.82,-1,8.3,20,,
#XS Ineff= 2 , 0
       0    -2.7   18.82     8.3       0   17.12
Permanent Ineff=
       F       F
Bank Sta=-2.7,8.3
XS Rating Curve= 0
Exp/Cntr=.3,.1

Type RM Length L Ch R = 1 ,8       ,50,50,50
#Sta/Elev= 13
     -13      19      -3      19    -2.8    19.2    -2.4    19.2    -1.4    18.5
       0   16.75      .6      16     2.6    14.5     4.6    14.5     7.4    16.7
     7.8    16.7     8.8    16.1    18.8    16.1
#Mann= 3 , 0 , 0
     -13    .035       0    -2.4    .035       0     7.4    .035       0
Levee=-1,-2.4,19.2,-1,7.4,20,,
#XS Ineff= 2 , 0
       0    -2.4    19.2     7.4       0    16.7
Permanent Ineff=
       F       F
Bank Sta=-2.4,7.4
XS Rating Curve= 0
Exp/Cntr=.3,.1

Type RM Length L Ch R = 1 ,7       ,49,49,49
#Sta/Elev= 13
   -13.1   18.66    -3.1   18.66    -2.9   18.86    -2.5   18.86    -1.5   18.16
       0   16.29      .5   15.66     2.5   14.16     4.5   14.16     7.3   16.26
     7.8   16.26     8.8   15.76    18.8   15.76
#Mann= 3 , 0 , 0
   -13.1    .035       0    -2.5    .035       0     7.3    .035       0
Levee=-1,-2.5,18.86,-1,7.3,20,,
#XS Ineff= 2 , 0
       0    -2.5   18.86     7.3       0   16.26
Permanent Ineff=
       F       F
Bank Sta=-2.5,7.3
XS Rating Curve= 0
Exp/Cntr=.3,.1

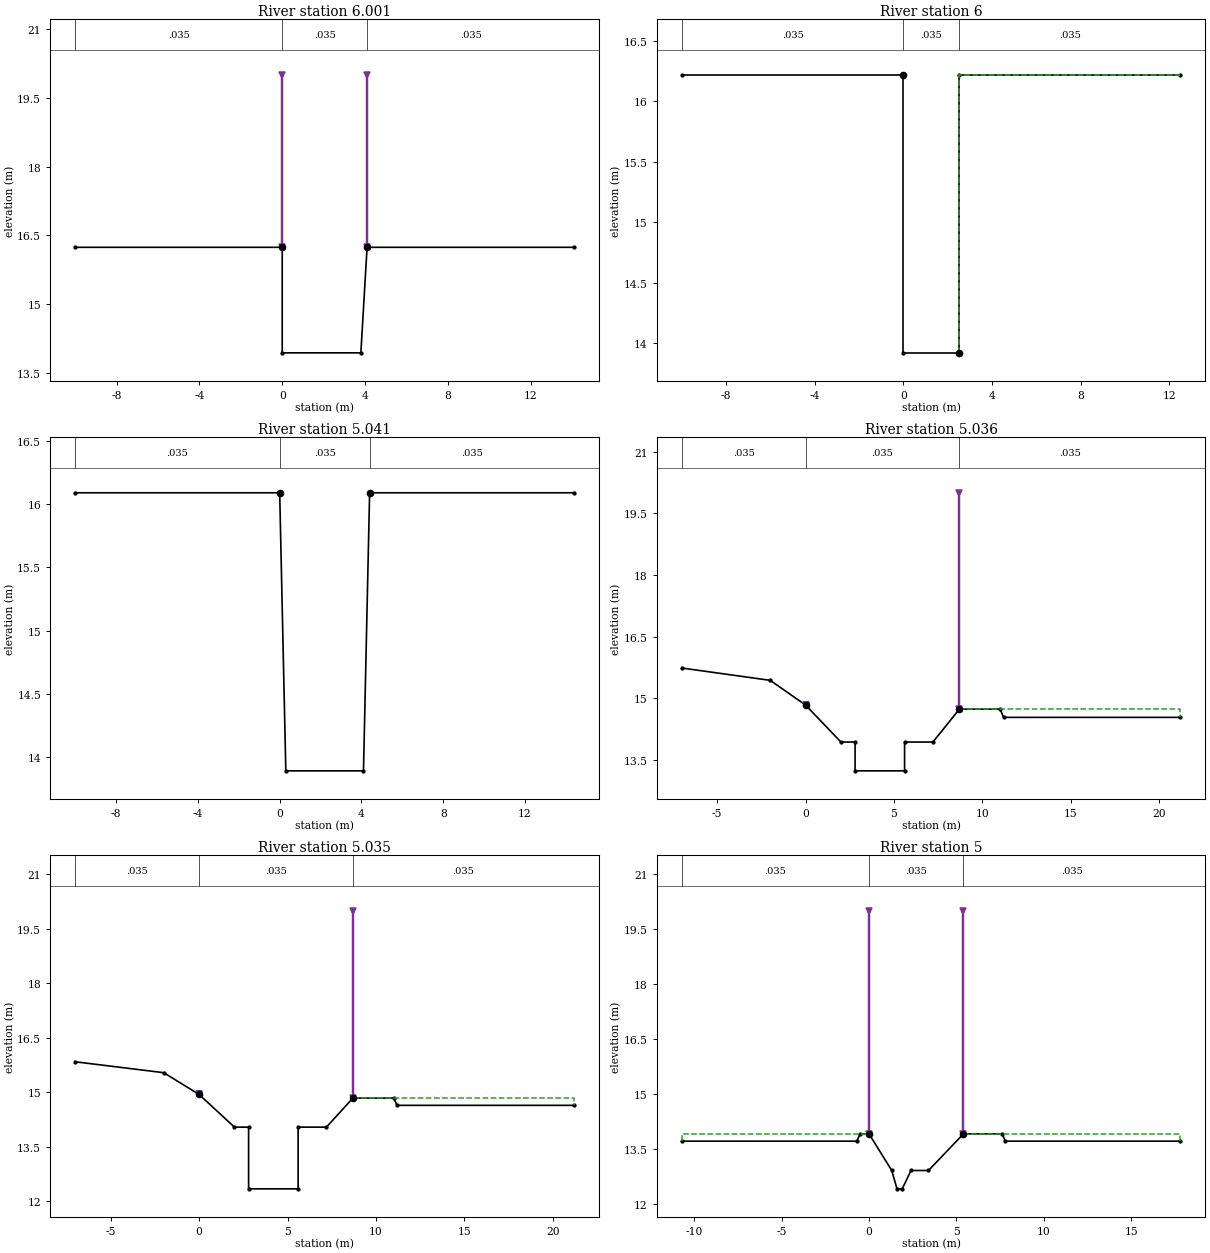
Type RM Length L Ch R = 1 ,6.001   ,1,1,1
#Sta/Elev= 6
     -10   16.24       0   16.24       0   13.94     3.8   13.94     4.1   16.24
    14.1   16.24
#Mann= 3 , 0 , 0
     -10    .035       0       0    .035       0     4.1    .035       0
Levee=-1,0,20,-1,4.1,20,,
#XS Ineff= 2 , 0
               0   16.24     4.1           16.24
Permanent Ineff=
       F       F
Bank Sta=0,4.1
XS Rating Curve= 0
Exp/Cntr=.3,.1

Type RM Length L Ch R = 1 ,6       ,9,9,9
#Sta/Elev= 6
     -10   16.22       0   16.22       0   13.92     2.5   13.92     2.5   16.22
    12.5   16.22
#Mann= 3 , 0 , 0
     -10    .035       0       0    .035       0     2.5    .035       0
#XS Ineff= 2 , 0
               0   16.22     2.5           16.22
Permanent Ineff=
       F       F
Bank Sta=0,2.5
XS Rating Curve= 0
Exp/Cntr=.3,.1

Type RM Length L Ch R = 1 ,5.041   ,5,5,5
#Sta/Elev= 6
     -10   16.09       0   16.09      .3   13.89     4.1   13.89     4.4   16.09
    14.4   16.09
#Mann= 3 , 0 , 0
     -10    .035       0       0    .035       0     4.4    .035       0
#XS Ineff= 2 , 0
               0   16.09     4.4           16.09
Permanent Ineff=
       F       F
Bank Sta=0,4.4
XS Rating Curve= 0
Exp/Cntr=.3,.1

Type RM Length L Ch R = 1 ,5.036   ,1,1,1
#Sta/Elev= 13
      -7   15.74      -2   15.44       0   14.84       2   13.94     2.8   13.94
     2.8   13.24     5.6   13.24     5.6   13.94     7.2   13.94     8.7   14.74
      11   14.74    11.2   14.54    21.2   14.54
#Mann= 3 , 0 , 0
      -7    .035       0       0    .035       0     8.7    .035       0
Levee=-1,0,14.84,-1,8.7,20,,
#XS Ineff= 2 , 0
               0   14.84     8.7           14.74
Permanent Ineff=
       F       F
Bank Sta=0,8.7
XS Rating Curve= 0
Exp/Cntr=.3,.1

Type RM Length L Ch R = 1 ,5.035   ,35,35,35
#Sta/Elev= 13
      -7   15.84      -2   15.54       0   14.94       2   14.04     2.8   14.04
     2.8   12.34     5.6   12.34     5.6   14.04     7.2   14.04     8.7   14.84
      11   14.84    11.2   14.64    21.2   14.64
#Mann= 3 , 0 , 0
      -7    .035       0       0    .035       0     8.7    .035       0
Levee=-1,0,14.94,-1,8.7,20,,
#XS Ineff= 2 , 0
               0   14.94     8.7           14.84
Permanent Ineff=
       F       F
Bank Sta=0,8.7
XS Rating Curve= 0
Exp/Cntr=.3,.1

Type RM Length L Ch R = 1 ,5       ,50,50,50
#Sta/Elev= 13
   -10.7   13.72     -.7   13.72     -.5   13.92       0   13.92     1.3   12.92
     1.6   12.42     1.9   12.42     2.4   12.92     3.4   12.92     5.4   13.92
     7.6   13.92     7.8   13.72    17.8   13.72
#Mann= 3 , 0 , 0
   -10.7    .035       0       0    .035       0     5.4    .035       0
Levee=-1,0,20,-1,5.4,20,,
#XS Ineff= 2 , 0
               0   13.92     5.4           13.92
Permanent Ineff=
       F       F
Bank Sta=0,5.4
XS Rating Curve= 0
Exp/Cntr=.3,.1

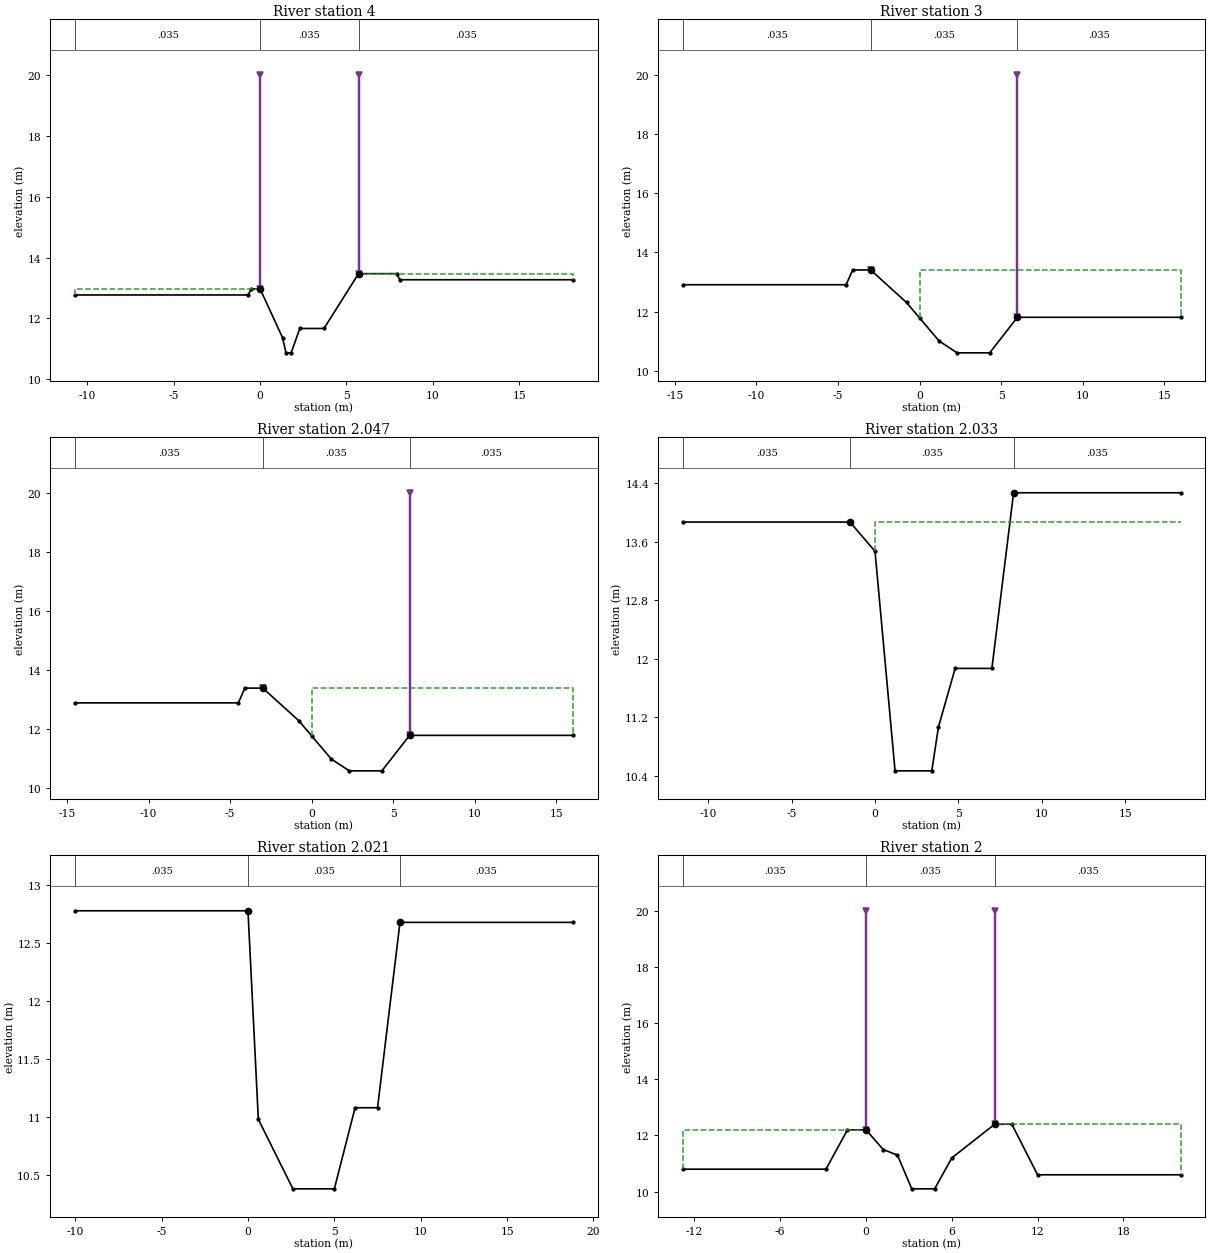
Type RM Length L Ch R = 1 ,4       ,50,50,50
#Sta/Elev= 13
   -10.7   12.77     -.7   12.77     -.5   12.97       0   12.97     1.3   11.37
     1.5   10.87     1.8   10.87     2.3   11.67     3.7   11.67     5.7   13.47
     7.9   13.47     8.1   13.27    18.1   13.27
#Mann= 3 , 0 , 0
   -10.7    .035       0       0    .035       0     5.7    .035       0
Levee=-1,0,20,-1,5.7,20,,
#XS Ineff= 2 , 0
               0   12.97     5.7           13.47
Permanent Ineff=
       F       F
Bank Sta=0,5.7
XS Rating Curve= 0
Exp/Cntr=.3,.1

Type RM Length L Ch R = 1 ,3       ,3,3,3
#Sta/Elev= 11
   -14.5   12.91    -4.5   12.91    -4.1   13.41      -3   13.41     -.8   12.31
       0   11.79     1.2   11.01     2.3   10.61     4.3   10.61       6   11.81
      16   11.81
#Mann= 3 , 0 , 0
   -14.5    .035       0      -3    .035       0       6    .035       0
Levee=-1,-3,13.41,-1,6,20,,
#XS Ineff= 2 , 0
       0      -3   13.41       6       0   11.81
Permanent Ineff=
       F       F
Bank Sta=-3,6
XS Rating Curve= 0
Exp/Cntr=.3,.1

Type RM Length L Ch R = 1 ,2.047   ,14,14,14
#Sta/Elev= 11
   -14.5   12.89    -4.5   12.89    -4.1   13.39      -3   13.39     -.8   12.29
       0   11.77     1.2   10.99     2.3   10.59     4.3   10.59       6   11.79
      16   11.79
#Mann= 3 , 0 , 0
   -14.5    .035       0      -3    .035       0       6    .035       0
Levee=-1,-3,13.39,-1,6,20,,
#XS Ineff= 2 , 0
       0      -3   13.39       6       0   11.79
Permanent Ineff=
       F       F
Bank Sta=-3,6
XS Rating Curve= 0
Exp/Cntr=.3,.1

Type RM Length L Ch R = 1 ,2.033   ,12,12,12
#Sta/Elev= 10
   -11.5   13.87    -1.5   13.87       0   13.47     1.2   10.47     3.4   10.47
     3.8   11.07     4.8   11.87       7   11.87     8.3   14.27    18.3   14.27
#Mann= 3 , 0 , 0
   -11.5    .035       0    -1.5    .035       0     8.3    .035       0
#XS Ineff= 2 , 0
       0    -1.5   13.87     8.3       0   14.27
Permanent Ineff=
       F       F
Bank Sta=-1.5,8.3
XS Rating Curve= 0
Exp/Cntr=.3,.1

Type RM Length L Ch R = 1 ,2.021   ,21,21,21
#Sta/Elev= 9
     -10   12.78       0   12.78      .6   10.98     2.6   10.38       5   10.38
     6.2   11.08     7.5   11.08     8.8   12.68    18.8   12.68
#Mann= 3 , 0 , 0
     -10    .035       0       0    .035       0     8.8    .035       0
#XS Ineff= 2 , 0
               0   12.78     8.8           12.68
Permanent Ineff=
       F       F
Bank Sta=0,8.8
XS Rating Curve= 0
Exp/Cntr=.3,.1

Type RM Length L Ch R = 1 ,2       ,50,50,50
#Sta/Elev= 13
   -12.8    10.8    -2.8    10.8    -1.3    12.2       0    12.2     1.2    11.5
     2.2    11.3     3.2    10.1     4.8    10.1       6    11.2       9    12.4
    10.2    12.4      12    10.6      22    10.6
#Mann= 3 , 0 , 0
   -12.8    .035       0       0    .035       0       9    .035       0
Levee=-1,0,20,-1,9,20,,
#XS Ineff= 2 , 0
               0    12.2       9            12.4
Permanent Ineff=
       F       F
Bank Sta=0,9
XS Rating Curve= 0
Exp/Cntr=.3,.1

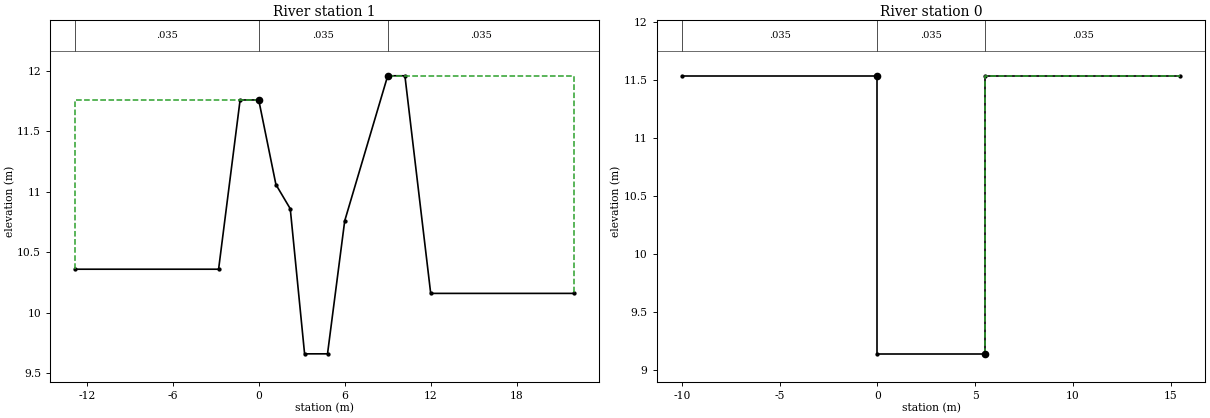
Type RM Length L Ch R = 1 ,1       ,50,50,50
#Sta/Elev= 13
   -12.8   10.36    -2.8   10.36    -1.3   11.76       0   11.76     1.2   11.06
     2.2   10.86     3.2    9.66     4.8    9.66       6   10.76       9   11.96
    10.2   11.96      12   10.16      22   10.16
#Mann= 3 , 0 , 0
   -12.8    .035       0       0    .035       0       9    .035       0
#XS Ineff= 2 , 0
               0   11.76       9           11.96
Permanent Ineff=
       F       F
Bank Sta=0,9
XS Rating Curve= 0
Exp/Cntr=.3,.1

Type RM Length L Ch R = 1 ,0       ,0,0,0
#Sta/Elev= 6
     -10   11.54       0   11.54       0    9.14     5.5    9.14     5.5   11.54
    15.5   11.54
#Mann= 3 , 0 , 0
     -10    .035       0       0    .035       0     5.5    .035       0
#XS Ineff= 2 , 0
               0   11.54     5.5           11.54
Permanent Ineff=
       F       F
Bank Sta=0,5.5
XS Rating Curve= 0
Exp/Cntr=.3,.1

Chan Stop Cuts=-1