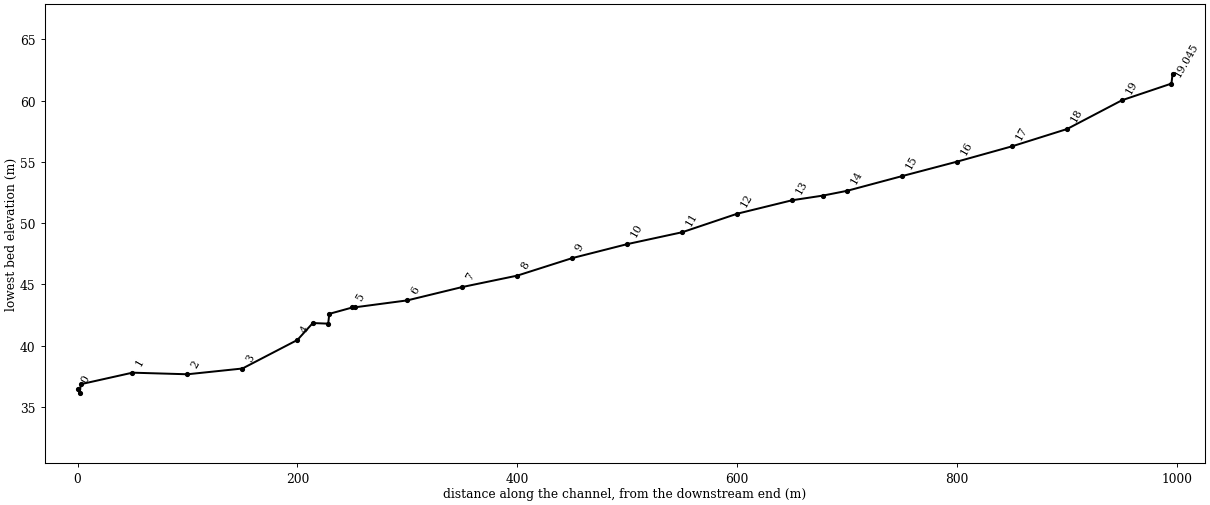
--- enc.prj (project) ---

Proj Title=eupne-ch
Current Plan=p01
Default Exp/Contr=.3,.1
SI Units
Geom File=g01
Flow File=f01
Plan File=p01
Y Axis Title=Elevation
X Axis Title(PF)=Main Channel Distance
X Axis Title(XS)=Station
BEGIN DESCRIPTION:
           BACK WATER COMPUTATION
      APPLICATION OF HEC-2 BY Samju Construction Engineering
      À¾³»Ãµ(ÁÖÆ÷¸é): 30,50,80,100,150³âºóµµ °³¼öÀü
END DESCRIPTION:
DSS Export Rating Curves= 0
DSS Export Rating Curve Sorted= 0
DSS Export Volume Flow Curves= 0
DXF OffsetX= 0
DXF OffsetY= 0
DXF ScaleX= 1
DXF ScaleY= 10

--- enc.p01 (plan) ---

Plan Title=Imported Plan 01
Version=Version 3.0.1  Mar 2001
Short Identifier=Imported Pla
Geom File=g01
Flow File=f01
Subcritical Flow
K Sum by GR= 0
Std Step Tol= 0.003
Critical Tol= 0.003
Num of Std Step Trials= 20
Max Error Tol= 0.1
Flow Tol Ratio= 0.001
Split Flow NTrial= 30
Split Flow Tol= 0.02
Split Flow Ratio= 0.02
Log Output Level= 0
Friction Slope Method= 1
Unsteady Friction Slope Method= 2
Parabolic Critical Depth
Global Vel Dist= 0 , 0 , 0
Global Log Level= 0
CheckData=True
Encroach Param=-1 ,0,0, 0
Computation Interval=1HOUR
Output Interval=1HOUR
Run HTab= 0
Run UNet= 0
Run PostProcess= 0
UNET Theta= 1
UNET ZTol= 0.02
UNET ZSATol= 0.1
UNET MxIter= 20
UNET MaxInSteps= 20
UNET DtIC= 0
UNET DtMin= 0
UNET MaxCRTS= 20
UNET WFStab= 2
UNET SFStab= 1
UNET WFX= 1
UNET SFX= 1
UNET Convert EG Bridges=-1
UNET Use Existing IB Tables=-1
Instantaneous Interval=1HOUR
Write IC File= 0
Write Velocity= 0
Write Detailed= 0

--- enc.f01 (steady flow) ---

Flow Title=Imported Flow 01
Version=Version 3.0.1  Mar 2001
Number of Profiles= 5
Profile Names=10yr,20yr,30yr,50yr,80yr
River Rch & RM=RIVER-1,Reach-1         ,19.046
   14.82   16.34   17.22   18.34   19.37
Boundary for River Rch & Prof#=RIVER-1,Reach-1         , 1
Up Type= 0
Dn Type= 3
Dn Slope=.027
Boundary for River Rch & Prof#=RIVER-1,Reach-1         , 2
Up Type= 0
Dn Type= 3
Dn Slope=.027
Boundary for River Rch & Prof#=RIVER-1,Reach-1         , 3
Up Type= 0
Dn Type= 3
Dn Slope=.027
Boundary for River Rch & Prof#=RIVER-1,Reach-1         , 4
Up Type= 0
Dn Type= 3
Dn Slope=.027
Boundary for River Rch & Prof#=RIVER-1,Reach-1         , 5
Up Type= 0
Dn Type= 3
Dn Slope=.027
DSS Import GetInterval= 0
DSS Import GetPeak= 0
DSS Import FillOption= 0

--- enc.g01 (geometry) ---

Geom Title=Imported Geom 01
Version=Version 3.0.1  Mar 2001

River Reach=RIVER-1         ,Reach-1
Reach XY= 2
              .5             .95              .5             .05

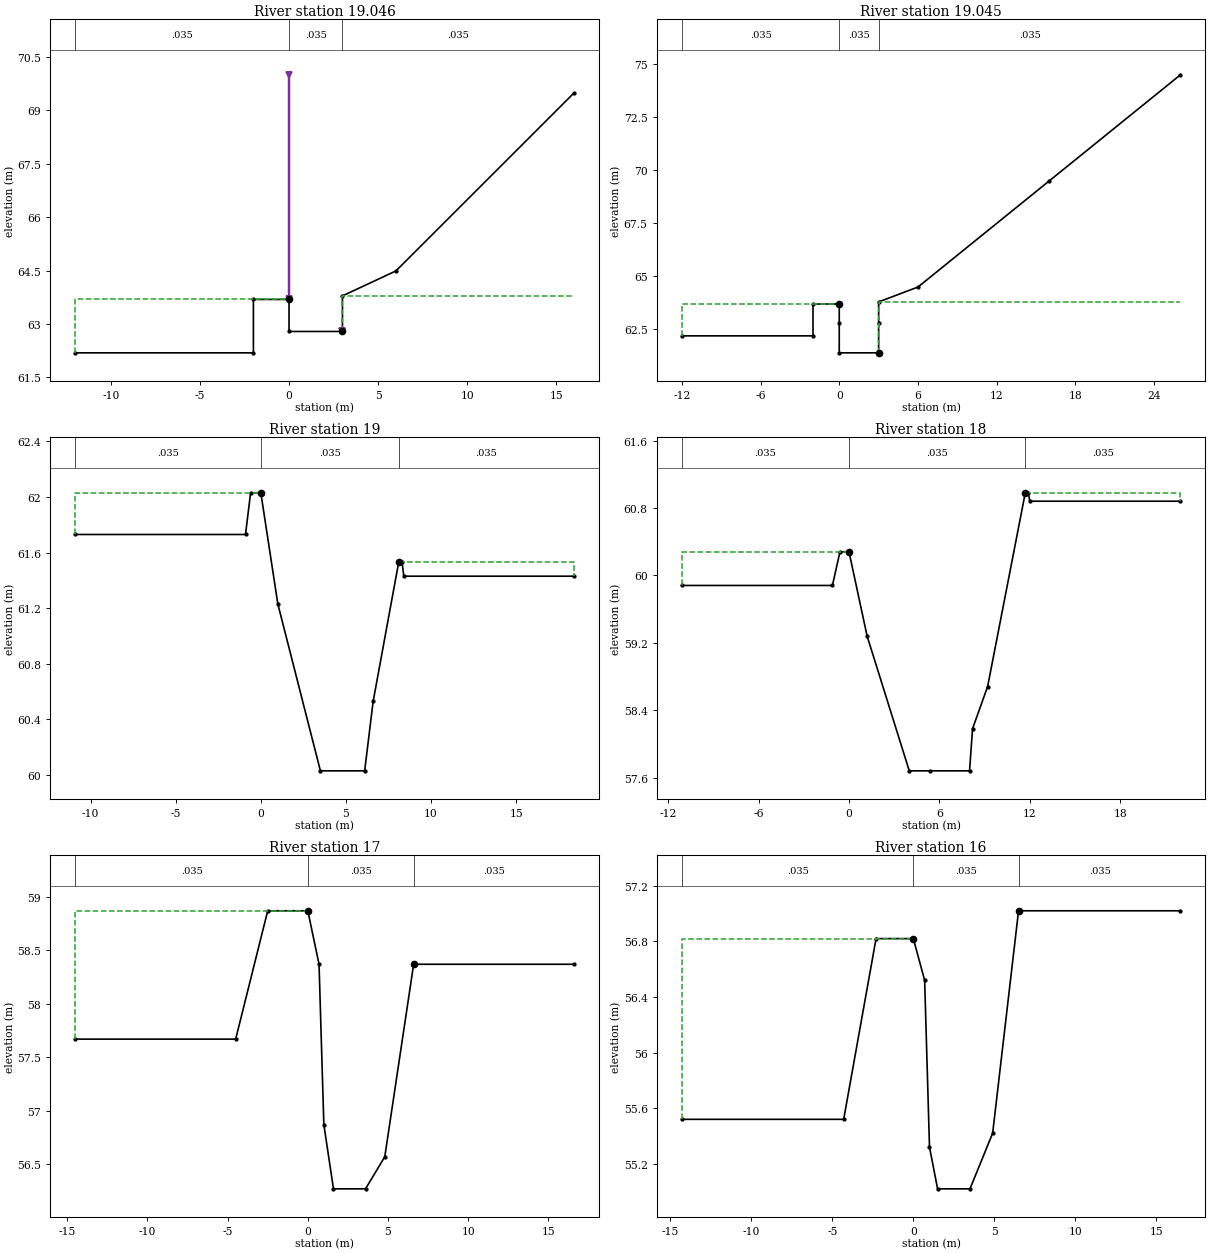
Type RM Length L Ch R = 1 ,19.046  ,1,1,1
#Sta/Elev= 9
     -12   62.19      -2   62.19      -2   63.69       0   63.69       0   62.79
       3   62.79       3   63.79       6   64.49      16   69.49
#Mann= 3 , 0 , 0
     -12    .035       0       0    .035       0       3    .035       0
Levee=-1,0,70,-1,3,62.79,,
#XS Ineff= 2 , 0
               0   63.69       3           63.79
Permanent Ineff=
       F       F
Bank Sta=0,3
XS Rating Curve= 0
Exp/Cntr=.3,.1

Type RM Length L Ch R = 1 ,19.045  ,45,45,45
#Sta/Elev= 12
     -12   62.19      -2   62.19      -2   63.69       0   63.69       0   62.79
       0   61.39       3   61.39       3   62.79       3   63.79       6   64.49
      16   69.49      26   74.49
#Mann= 3 , 0 , 0
     -12    .035       0       0    .035       0       3    .035       0
#XS Ineff= 2 , 0
               0   63.69       3           63.79
Permanent Ineff=
       F       F
Bank Sta=0,3
XS Rating Curve= 0
Exp/Cntr=.3,.1

Type RM Length L Ch R = 1 ,19      ,50,50,50
#Sta/Elev= 12
   -10.9   61.73     -.9   61.73     -.6   62.03       0   62.03       1   61.23
     3.5   60.03     6.1   60.03     6.6   60.53     8.1   61.53     8.3   61.53
     8.4   61.43    18.4   61.43
#Mann= 3 , 0 , 0
   -10.9    .035       0       0    .035       0     8.1    .035       0
#XS Ineff= 2 , 0
               0   62.03     8.1           61.53
Permanent Ineff=
       F       F
Bank Sta=0,8.1
XS Rating Curve= 0
Exp/Cntr=.3,.1

Type RM Length L Ch R = 1 ,18      ,50,50,50
#Sta/Elev= 14
   -11.1   59.88    -1.1   59.88     -.6   60.28       0   60.28     1.2   59.28
       4   57.68     5.4   57.68       8   57.68     8.2   58.18     9.2   58.68
    11.7   60.98    11.9   60.98      12   60.88      22   60.88
#Mann= 3 , 0 , 0
   -11.1    .035       0       0    .035       0    11.7    .035       0
#XS Ineff= 2 , 0
               0   60.28    11.7           60.98
Permanent Ineff=
       F       F
Bank Sta=0,11.7
XS Rating Curve= 0
Exp/Cntr=.3,.1

Type RM Length L Ch R = 1 ,17      ,50,50,50
#Sta/Elev= 11
   -14.5   57.67    -4.5   57.67    -2.5   58.87       0   58.87      .7   58.37
       1   56.87     1.6   56.27     3.6   56.27     4.8   56.57     6.6   58.37
    16.6   58.37
#Mann= 3 , 0 , 0
   -14.5    .035       0       0    .035       0     6.6    .035       0
#XS Ineff= 2 , 0
               0   58.87     6.6           58.37
Permanent Ineff=
       F       F
Bank Sta=0,6.6
XS Rating Curve= 0
Exp/Cntr=.3,.1

Type RM Length L Ch R = 1 ,16      ,50,50,50
#Sta/Elev= 11
   -14.3   55.52    -4.3   55.52    -2.3   56.82       0   56.82      .7   56.52
       1   55.32     1.5   55.02     3.5   55.02     4.9   55.42     6.5   57.02
    16.5   57.02
#Mann= 3 , 0 , 0
   -14.3    .035       0       0    .035       0     6.5    .035       0
#XS Ineff= 2 , 0
               0   56.82     6.5           57.02
Permanent Ineff=
       F       F
Bank Sta=0,6.5
XS Rating Curve= 0
Exp/Cntr=.3,.1

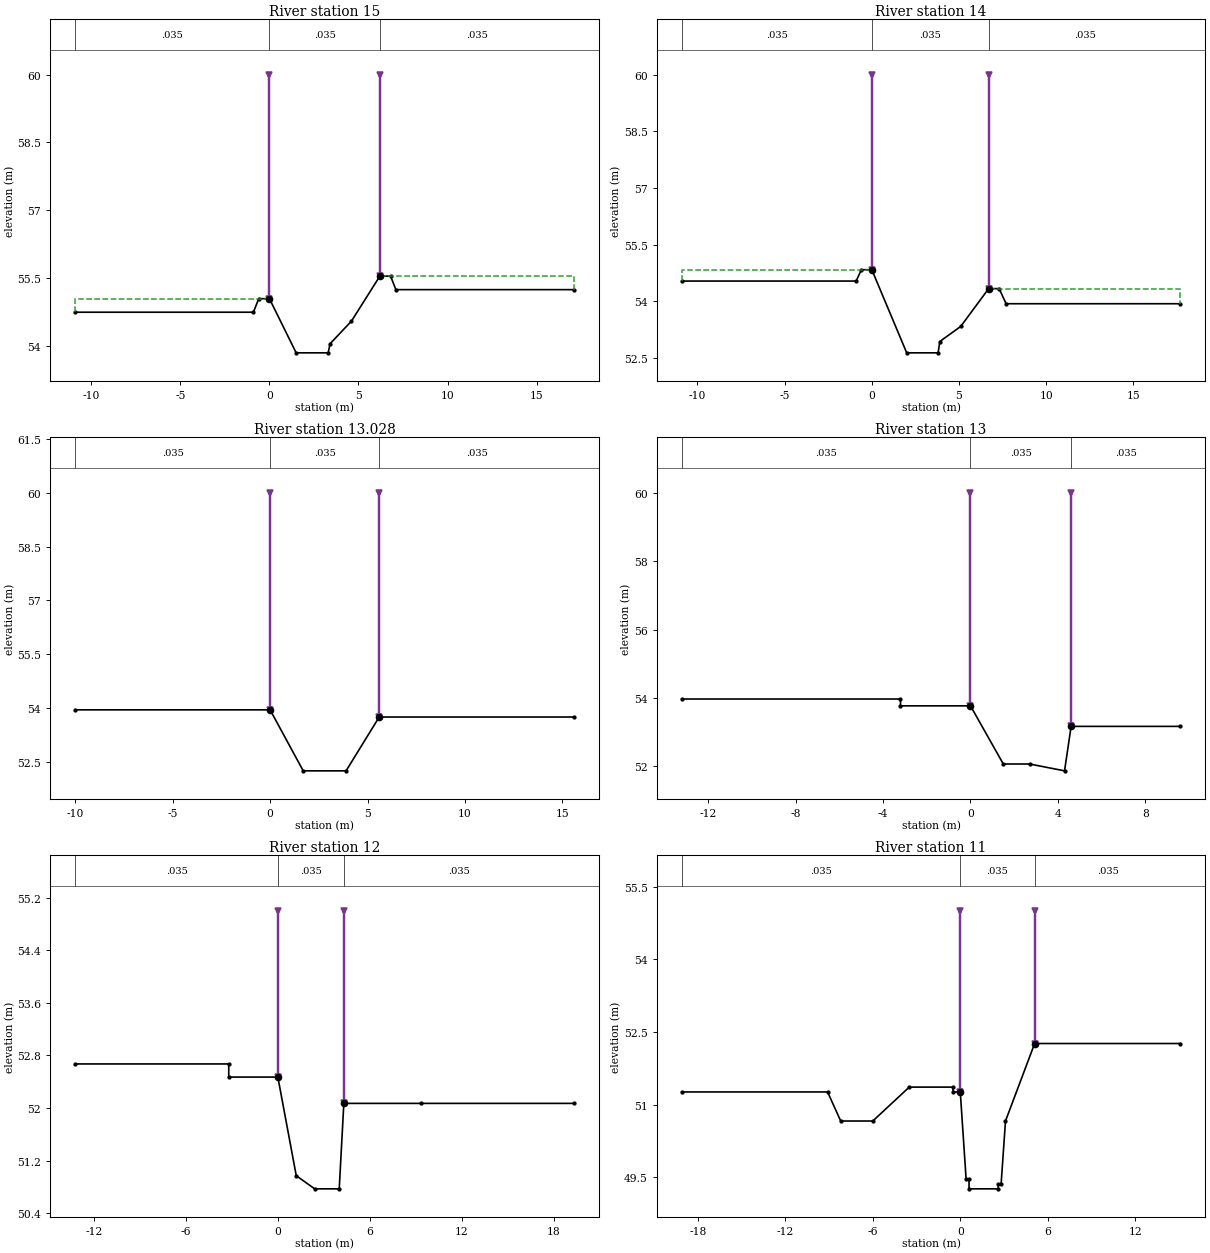
Type RM Length L Ch R = 1 ,15      ,50,50,50
#Sta/Elev= 12
   -10.9   54.74     -.9   54.74     -.6   55.04       0   55.04     1.5   53.84
     3.3   53.84     3.4   54.04     4.6   54.54     6.2   55.54     6.8   55.54
     7.1   55.24    17.1   55.24
#Mann= 3 , 0 , 0
   -10.9    .035       0       0    .035       0     6.2    .035       0
Levee=-1,0,60,-1,6.2,60,,
#XS Ineff= 2 , 0
               0   55.04     6.2           55.54
Permanent Ineff=
       F       F
Bank Sta=0,6.2
XS Rating Curve= 0
Exp/Cntr=.3,.1

Type RM Length L Ch R = 1 ,14      ,22,22,22
#Sta/Elev= 12
   -10.9   54.54     -.9   54.54     -.6   54.84       0   54.84       2   52.64
     3.8   52.64     3.9   52.94     5.1   53.34     6.7   54.34     7.3   54.34
     7.7   53.94    17.7   53.94
#Mann= 3 , 0 , 0
   -10.9    .035       0       0    .035       0     6.7    .035       0
Levee=-1,0,60,-1,6.7,60,,
#XS Ineff= 2 , 0
               0   54.84     6.7           54.34
Permanent Ineff=
       F       F
Bank Sta=0,6.7
XS Rating Curve= 0
Exp/Cntr=.3,.1

Type RM Length L Ch R = 1 ,13.028  ,28,28,28
#Sta/Elev= 6
     -10   53.95       0   53.95     1.7   52.25     3.9   52.25     5.6   53.75
    15.6   53.75
#Mann= 3 , 0 , 0
     -10    .035       0       0    .035       0     5.6    .035       0
Levee=-1,0,60,-1,5.6,60,,
#XS Ineff= 2 , 0
               0   53.95     5.6           53.75
Permanent Ineff=
       F       F
Bank Sta=0,5.6
XS Rating Curve= 0
Exp/Cntr=.3,.1

Type RM Length L Ch R = 1 ,13      ,50,50,50
#Sta/Elev= 9
   -13.2   53.97    -3.2   53.97    -3.2   53.77       0   53.77     1.5   52.07
     2.7   52.07     4.3   51.87     4.6   53.17     9.6   53.17
#Mann= 3 , 0 , 0
   -13.2    .035       0       0    .035       0     4.6    .035       0
Levee=-1,0,60,-1,4.6,60,,
#XS Ineff= 2 , 0
               0   53.77     4.6           53.17
Permanent Ineff=
       F       F
Bank Sta=0,4.6
XS Rating Curve= 0
Exp/Cntr=.3,.1

Type RM Length L Ch R = 1 ,12      ,50,50,50
#Sta/Elev= 10
   -13.2   52.67    -3.2   52.67    -3.2   52.47       0   52.47     1.2   50.97
     2.4   50.77       4   50.77     4.3   52.07     9.3   52.07    19.3   52.07
#Mann= 3 , 0 , 0
   -13.2    .035       0       0    .035       0     4.3    .035       0
Levee=-1,0,55,-1,4.3,55,,
#XS Ineff= 2 , 0
               0   52.47     4.3           52.07
Permanent Ineff=
       F       F
Bank Sta=0,4.3
XS Rating Curve= 0
Exp/Cntr=.3,.1

Type RM Length L Ch R = 1 ,11      ,50,50,50
#Sta/Elev= 17
   -19.1   51.26    -9.1   51.26    -8.2   50.66      -6   50.66    -3.5   51.36
     -.5   51.36     -.5   51.26       0   51.26      .4   49.46      .6   49.46
      .6   49.26     2.6   49.26     2.6   49.36     2.8   49.36     3.1   50.66
     5.1   52.26    15.1   52.26
#Mann= 3 , 0 , 0
   -19.1    .035       0       0    .035       0     5.1    .035       0
Levee=-1,0,55,-1,5.1,55,,
#XS Ineff= 2 , 0
               0   51.26     5.1           52.26
Permanent Ineff=
       F       F
Bank Sta=0,5.1
XS Rating Curve= 0
Exp/Cntr=.3,.1

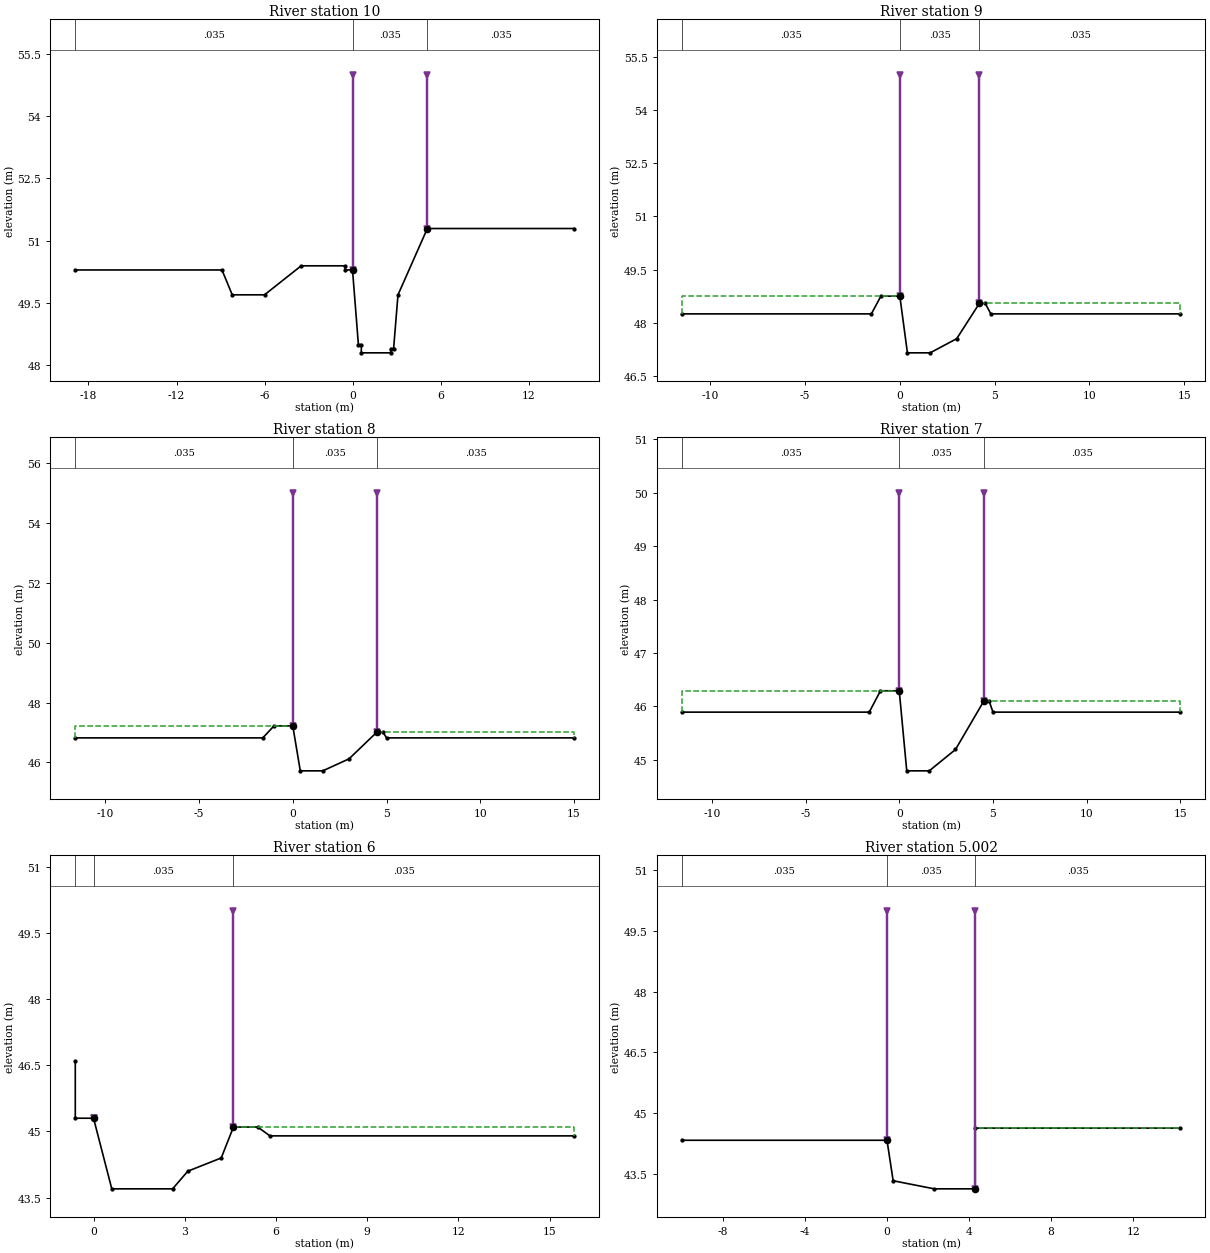
Type RM Length L Ch R = 1 ,10      ,50,50,50
#Sta/Elev= 17
   -18.9   50.29    -8.9   50.29    -8.2   49.69      -6   49.69    -3.5   50.39
     -.5   50.39     -.5   50.29       0   50.29      .4   48.49      .6   48.49
      .6   48.29     2.6   48.29     2.6   48.39     2.8   48.39     3.1   49.69
     5.1   51.29    15.1   51.29
#Mann= 3 , 0 , 0
   -18.9    .035       0       0    .035       0     5.1    .035       0
Levee=-1,0,55,-1,5.1,55,,
#XS Ineff= 2 , 0
               0   50.29     5.1           51.29
Permanent Ineff=
       F       F
Bank Sta=0,5.1
XS Rating Curve= 0
Exp/Cntr=.3,.1

Type RM Length L Ch R = 1 ,9       ,50,50,50
#Sta/Elev= 11
   -11.5   48.25    -1.5   48.25      -1   48.75       0   48.75      .4   47.15
     1.6   47.15       3   47.55     4.2   48.55     4.5   48.55     4.8   48.25
    14.8   48.25
#Mann= 3 , 0 , 0
   -11.5    .035       0       0    .035       0     4.2    .035       0
Levee=-1,0,55,-1,4.2,55,,
#XS Ineff= 2 , 0
               0   48.75     4.2           48.55
Permanent Ineff=
       F       F
Bank Sta=0,4.2
XS Rating Curve= 0
Exp/Cntr=.3,.1

Type RM Length L Ch R = 1 ,8       ,50,50,50
#Sta/Elev= 11
   -11.6   46.82    -1.6   46.82      -1   47.22       0   47.22      .4   45.72
     1.6   45.72       3   46.12     4.5   47.02     4.8   47.02       5   46.82
      15   46.82
#Mann= 3 , 0 , 0
   -11.6    .035       0       0    .035       0     4.5    .035       0
Levee=-1,0,55,-1,4.5,55,,
#XS Ineff= 2 , 0
               0   47.22     4.5           47.02
Permanent Ineff=
       F       F
Bank Sta=0,4.5
XS Rating Curve= 0
Exp/Cntr=.3,.1

Type RM Length L Ch R = 1 ,7       ,50,50,50
#Sta/Elev= 11
   -11.6   45.89    -1.6   45.89      -1   46.29       0   46.29      .4   44.79
     1.6   44.79       3   45.19     4.5   46.09     4.8   46.09       5   45.89
      15   45.89
#Mann= 3 , 0 , 0
   -11.6    .035       0       0    .035       0     4.5    .035       0
Levee=-1,0,50,-1,4.5,50,,
#XS Ineff= 2 , 0
               0   46.29     4.5           46.09
Permanent Ineff=
       F       F
Bank Sta=0,4.5
XS Rating Curve= 0
Exp/Cntr=.3,.1

Type RM Length L Ch R = 1 ,6       ,48,48,48
#Sta/Elev= 11
     -.6    46.6     -.6    45.3       0    45.3      .6    43.7     2.6    43.7
     3.1    44.1     4.2    44.4     4.6    45.1     5.4    45.1     5.8    44.9
    15.8    44.9
#Mann= 3 , 0 , 0
     -.6    .035       0       0    .035       0     4.6    .035       0
Levee=-1,0,45.3,-1,4.6,50,,
#XS Ineff= 2 , 0
               0    45.3     4.6            45.1
Permanent Ineff=
       F       F
Bank Sta=0,4.6
XS Rating Curve= 0
Exp/Cntr=.3,.1

Type RM Length L Ch R = 1 ,5.002   ,2,2,2
#Sta/Elev= 7
     -10   44.33       0   44.33      .3   43.33     2.3   43.13     4.3   43.13
     4.3   44.63    14.3   44.63
#Mann= 3 , 0 , 0
     -10    .035       0       0    .035       0     4.3    .035       0
Levee=-1,0,50,-1,4.3,50,,
#XS Ineff= 2 , 0
               0   44.33     4.3           44.63
Permanent Ineff=
       F       F
Bank Sta=0,4.3
XS Rating Curve= 0
Exp/Cntr=.3,.1

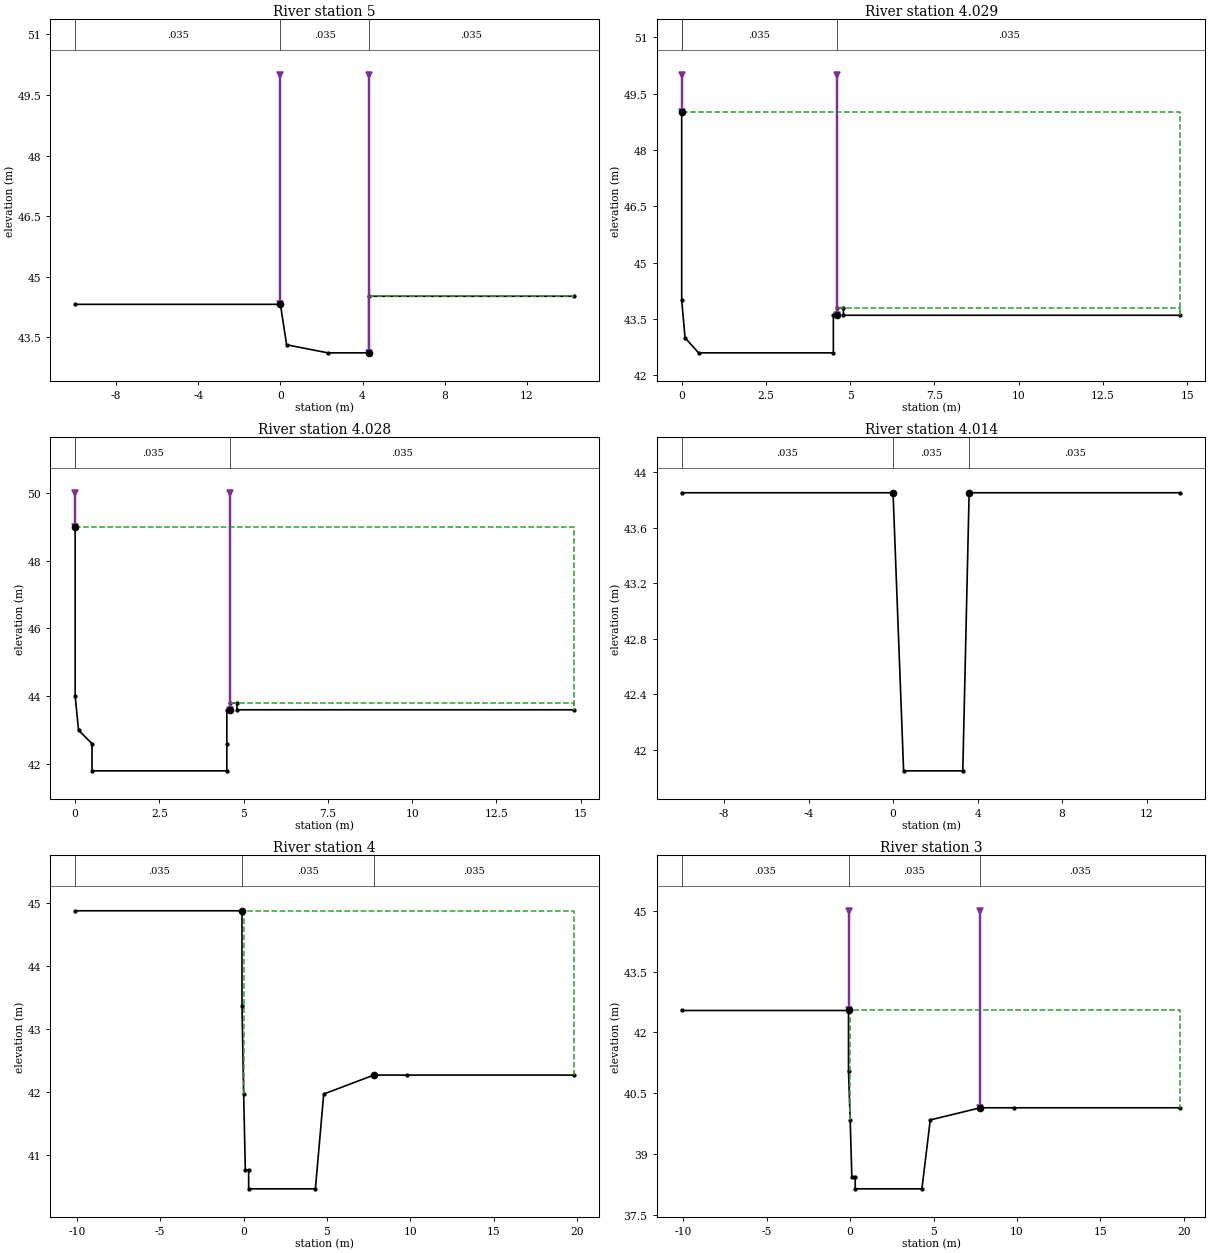
Type RM Length L Ch R = 1 ,5       ,21,21,21
#Sta/Elev= 7
     -10   44.32       0   44.32      .3   43.32     2.3   43.12     4.3   43.12
     4.3   44.52    14.3   44.52
#Mann= 3 , 0 , 0
     -10    .035       0       0    .035       0     4.3    .035       0
Levee=-1,0,50,-1,4.3,50,,
#XS Ineff= 2 , 0
               0   44.32     4.3           44.52
Permanent Ineff=
       F       F
Bank Sta=0,4.3
XS Rating Curve= 0
Exp/Cntr=.3,.1

Type RM Length L Ch R = 1 ,4.029   ,1,1,1
#Sta/Elev= 11
       0      49       0      44      .1      43      .5    42.6     4.5    42.6
     4.5    43.6     4.6    43.6     4.6    43.8     4.8    43.8     4.8    43.6
    14.8    43.6
#Mann= 3 , 0 , 0
       0    .035       0       0    .035       0     4.6    .035       0
Levee=-1,0,50,-1,4.6,50,,
#XS Ineff= 2 , 0
               0      49     4.6            43.8
Permanent Ineff=
       F       F
Bank Sta=0,4.6
XS Rating Curve= 0
Exp/Cntr=.3,.1

Type RM Length L Ch R = 1 ,4.028   ,14,14,14
#Sta/Elev= 13
       0      49       0      44      .1      43      .5    42.6      .5    41.8
     4.5    41.8     4.5    42.6     4.5    43.6     4.6    43.6     4.6    43.8
     4.8    43.8     4.8    43.6    14.8    43.6
#Mann= 3 , 0 , 0
       0    .035       0       0    .035       0     4.6    .035       0
Levee=-1,0,50,-1,4.6,50,,
#XS Ineff= 2 , 0
               0      49     4.6            43.8
Permanent Ineff=
       F       F
Bank Sta=0,4.6
XS Rating Curve= 0
Exp/Cntr=.3,.1

Type RM Length L Ch R = 1 ,4.014   ,14,14,14
#Sta/Elev= 6
     -10   43.85       0   43.85      .5   41.85     3.3   41.85     3.6   43.85
    13.6   43.85
#Mann= 3 , 0 , 0
     -10    .035       0       0    .035       0     3.6    .035       0
#XS Ineff= 2 , 0
               0   43.85     3.6           43.85
Permanent Ineff=
       F       F
Bank Sta=0,3.6
XS Rating Curve= 0
Exp/Cntr=.3,.1

Type RM Length L Ch R = 1 ,4       ,50,50,50
#Sta/Elev= 12
   -10.1   44.87     -.1   44.87     -.1   43.37       0   41.97      .1   40.77
      .3   40.77      .3   40.47     4.3   40.47     4.8   41.97     7.8   42.27
     9.8   42.27    19.8   42.27
#Mann= 3 , 0 , 0
   -10.1    .035       0     -.1    .035       0     7.8    .035       0
#XS Ineff= 2 , 0
       0     -.1   44.87     7.8       0   42.27
Permanent Ineff=
       F       F
Bank Sta=-.1,7.8
XS Rating Curve= 0
Exp/Cntr=.3,.1

Type RM Length L Ch R = 1 ,3       ,50,50,50
#Sta/Elev= 12
   -10.1   42.54     -.1   42.54     -.1   41.04       0   39.84      .1   38.44
      .3   38.44      .3   38.14     4.3   38.14     4.8   39.84     7.8   40.14
     9.8   40.14    19.8   40.14
#Mann= 3 , 0 , 0
   -10.1    .035       0     -.1    .035       0     7.8    .035       0
Levee=-1,-.1,45,-1,7.8,45,,
#XS Ineff= 2 , 0
       0     -.1   42.54     7.8       0   40.14
Permanent Ineff=
       F       F
Bank Sta=-.1,7.8
XS Rating Curve= 0
Exp/Cntr=.3,.1

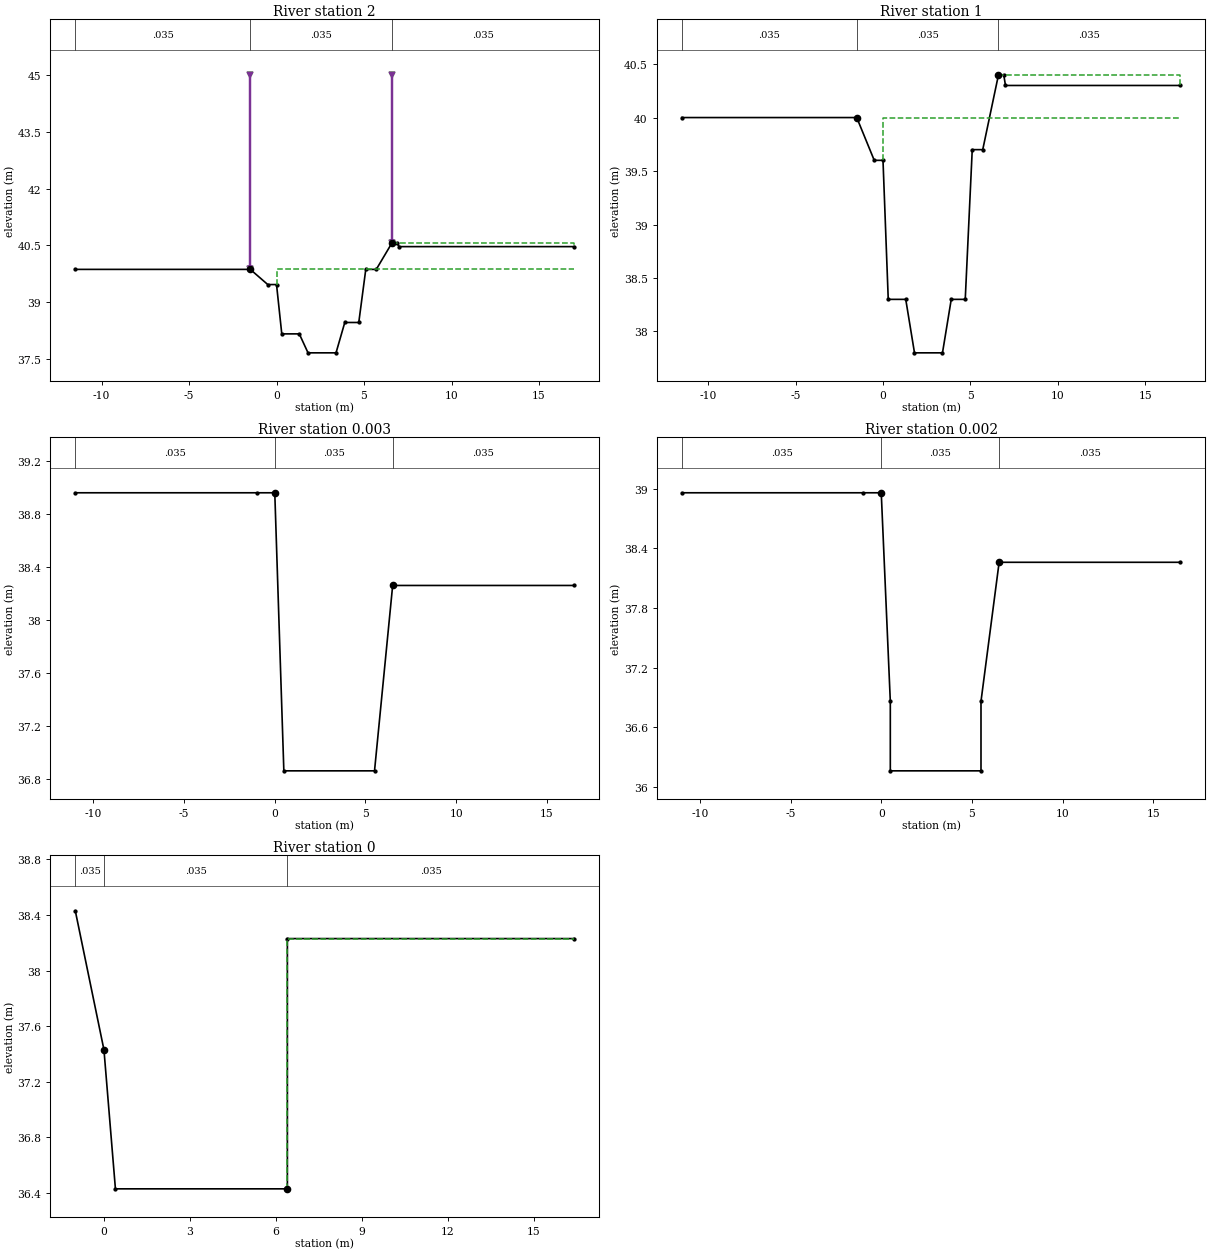
Type RM Length L Ch R = 1 ,2       ,50,50,50
#Sta/Elev= 16
   -11.5   39.87    -1.5   39.87     -.5   39.47       0   39.47      .3   38.17
     1.3   38.17     1.8   37.67     3.4   37.67     3.9   38.47     4.7   38.47
     5.1   39.87     5.7   39.87     6.6   40.57     6.9   40.57       7   40.47
      17   40.47
#Mann= 3 , 0 , 0
   -11.5    .035       0    -1.5    .035       0     6.6    .035       0
Levee=-1,-1.5,45,-1,6.6,45,,
#XS Ineff= 2 , 0
       0    -1.5   39.87     6.6       0   40.57
Permanent Ineff=
       F       F
Bank Sta=-1.5,6.6
XS Rating Curve= 0
Exp/Cntr=.3,.1

Type RM Length L Ch R = 1 ,1       ,47,47,47
#Sta/Elev= 16
   -11.5      40    -1.5      40     -.5    39.6       0    39.6      .3    38.3
     1.3    38.3     1.8    37.8     3.4    37.8     3.9    38.3     4.7    38.3
     5.1    39.7     5.7    39.7     6.6    40.4     6.9    40.4       7    40.3
      17    40.3
#Mann= 3 , 0 , 0
   -11.5    .035       0    -1.5    .035       0     6.6    .035       0
#XS Ineff= 2 , 0
       0    -1.5      40     6.6       0    40.4
Permanent Ineff=
       F       F
Bank Sta=-1.5,6.6
XS Rating Curve= 0
Exp/Cntr=.3,.1

Type RM Length L Ch R = 1 ,0.003   ,1,1,1
#Sta/Elev= 7
     -11   38.96      -1   38.96       0   38.96      .5   36.86     5.5   36.86
     6.5   38.26    16.5   38.26
#Mann= 3 , 0 , 0
     -11    .035       0       0    .035       0     6.5    .035       0
#XS Ineff= 2 , 0
               0   38.96     6.5           38.26
Permanent Ineff=
       F       F
Bank Sta=0,6.5
XS Rating Curve= 0
Exp/Cntr=.3,.1

Type RM Length L Ch R = 1 ,0.002   ,2,2,2
#Sta/Elev= 9
     -11   38.96      -1   38.96       0   38.96      .5   36.86      .5   36.16
     5.5   36.16     5.5   36.86     6.5   38.26    16.5   38.26
#Mann= 3 , 0 , 0
     -11    .035       0       0    .035       0     6.5    .035       0
#XS Ineff= 2 , 0
               0   38.96     6.5           38.26
Permanent Ineff=
       F       F
Bank Sta=0,6.5
XS Rating Curve= 0
Exp/Cntr=.3,.1

Type RM Length L Ch R = 1 ,0       ,0,0,0
#Sta/Elev= 6
      -1   38.43       0   37.43      .4   36.43     6.4   36.43     6.4   38.23
    16.4   38.23
#Mann= 3 , 0 , 0
      -1    .035       0       0    .035       0     6.4    .035       0
#XS Ineff= 2 , 0
               0   37.43     6.4           38.23
Permanent Ineff=
       F       F
Bank Sta=0,6.4
XS Rating Curve= 0
Exp/Cntr=.3,.1

Chan Stop Cuts=-1