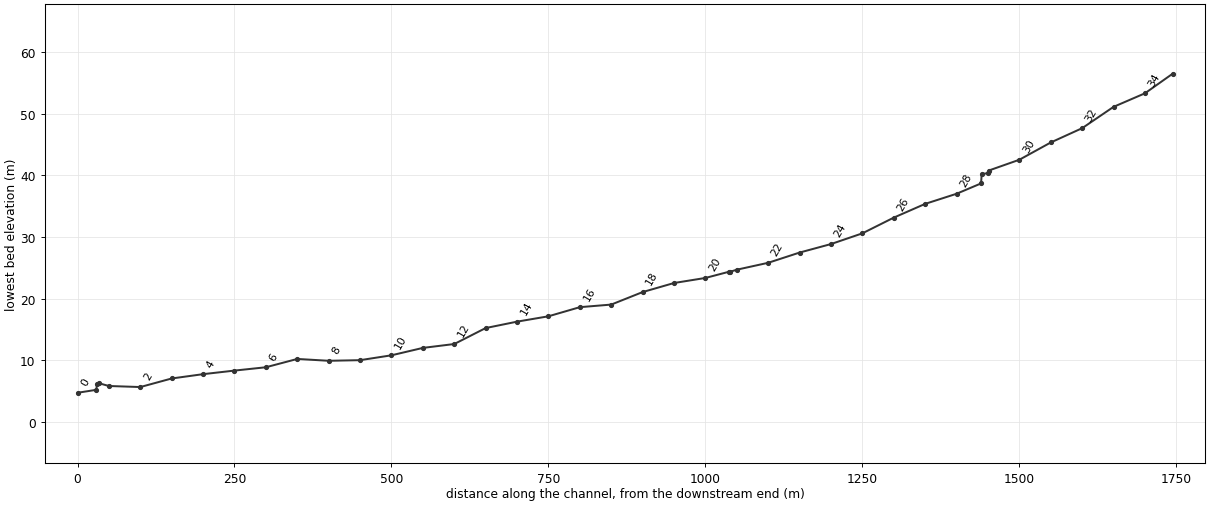
--- ksc.prj (project) ---

Proj Title=kwansan-ch
Current Plan=p01
Default Exp/Contr=.3,.1
SI Units
Geom File=g01
Flow File=f01
Plan File=p01
Y Axis Title=Elevation
X Axis Title(PF)=Main Channel Distance
X Axis Title(XS)=Station
BEGIN DESCRIPTION:
           BACK WATER COMPUTATION
      APPLICATION OF HEC-2 BY Samju Construction Engineering
      kwansan-ch: 10,20,30,50,80 yr
END DESCRIPTION:
DSS Export Rating Curves= 0
DSS Export Rating Curve Sorted= 0
DSS Export Volume Flow Curves= 0
DXF OffsetX= 0
DXF OffsetY= 0
DXF ScaleX= 1
DXF ScaleY= 10

--- ksc.p01 (plan) ---

Plan Title=Imported Plan 01
Version=Version 3.0.1  Mar 2001
Short Identifier=Imported Pla
Geom File=g01
Flow File=f01
Subcritical Flow
K Sum by GR= 0
Std Step Tol= 0.01
Critical Tol= 0.01
Num of Std Step Trials= 20
Max Error Tol= 0.3
Flow Tol Ratio= 0.001
Split Flow NTrial= 30
Split Flow Tol= 0.02
Split Flow Ratio= 0.02
Log Output Level= 0
Friction Slope Method= 1
Unsteady Friction Slope Method= 2
Parabolic Critical Depth
Global Vel Dist= 0 , 0 , 0
Global Log Level= 0
CheckData=True
Encroach Param=-1 ,0,0, 0
Computation Interval=1HOUR
Output Interval=1HOUR
Run HTab= 0
Run UNet= 0
Run PostProcess= 0
UNET Theta= 1
UNET ZTol= 0.02
UNET ZSATol= 0.1
UNET MxIter= 20
UNET MaxInSteps= 20
UNET DtIC= 0
UNET DtMin= 0
UNET MaxCRTS= 20
UNET WFStab= 2
UNET SFStab= 1
UNET WFX= 1
UNET SFX= 1
UNET Convert EG Bridges=-1
UNET Use Existing IB Tables=-1
Instantaneous Interval=1HOUR
Write IC File= 0
Write Velocity= 0
Write Detailed= 0

--- ksc.f01 (steady flow) ---

Flow Title=Imported Flow 01
Version=Version 3.0.1  Mar 2001
Number of Profiles= 5
Profile Names=10yr,20yr,30yr,50yr,80yr
River Rch & RM=RIVER-1,Reach-1         ,34.044
    10.9   12.01   12.65   13.47   14.22
River Rch & RM=RIVER-1,Reach-1         ,18
   21.32   23.49   24.77   26.37   27.85
River Rch & RM=KWANSAN,KWANSAN         ,34.044
    10.9   12.01   12.65   13.47   14.22
River Rch & RM=KWANSAN,KWANSAN         ,18
   21.32   23.49   24.77   26.37   27.85
Boundary for River Rch & Prof#=KWANSAN,KWANSAN         , 1
Up Type= 0
Dn Type= 3
Dn Slope=.03
Boundary for River Rch & Prof#=KWANSAN,KWANSAN         , 2
Up Type= 0
Dn Type= 3
Dn Slope=.03
Boundary for River Rch & Prof#=KWANSAN,KWANSAN         , 3
Up Type= 0
Dn Type= 3
Dn Slope=.03
Boundary for River Rch & Prof#=KWANSAN,KWANSAN         , 4
Up Type= 0
Dn Type= 3
Dn Slope=.03
Boundary for River Rch & Prof#=KWANSAN,KWANSAN         , 5
Up Type= 0
Dn Type= 3
Dn Slope=.03
DSS Import GetInterval= 0
DSS Import GetPeak= 0
DSS Import FillOption= 0

--- ksc.g01 (geometry) ---

Geom Title=Imported Geom 01
Version=Version 3.0.1  Mar 2001

River Reach=KWANSAN         ,KWANSAN
Reach XY= 2
              .5             .95              .5             .05

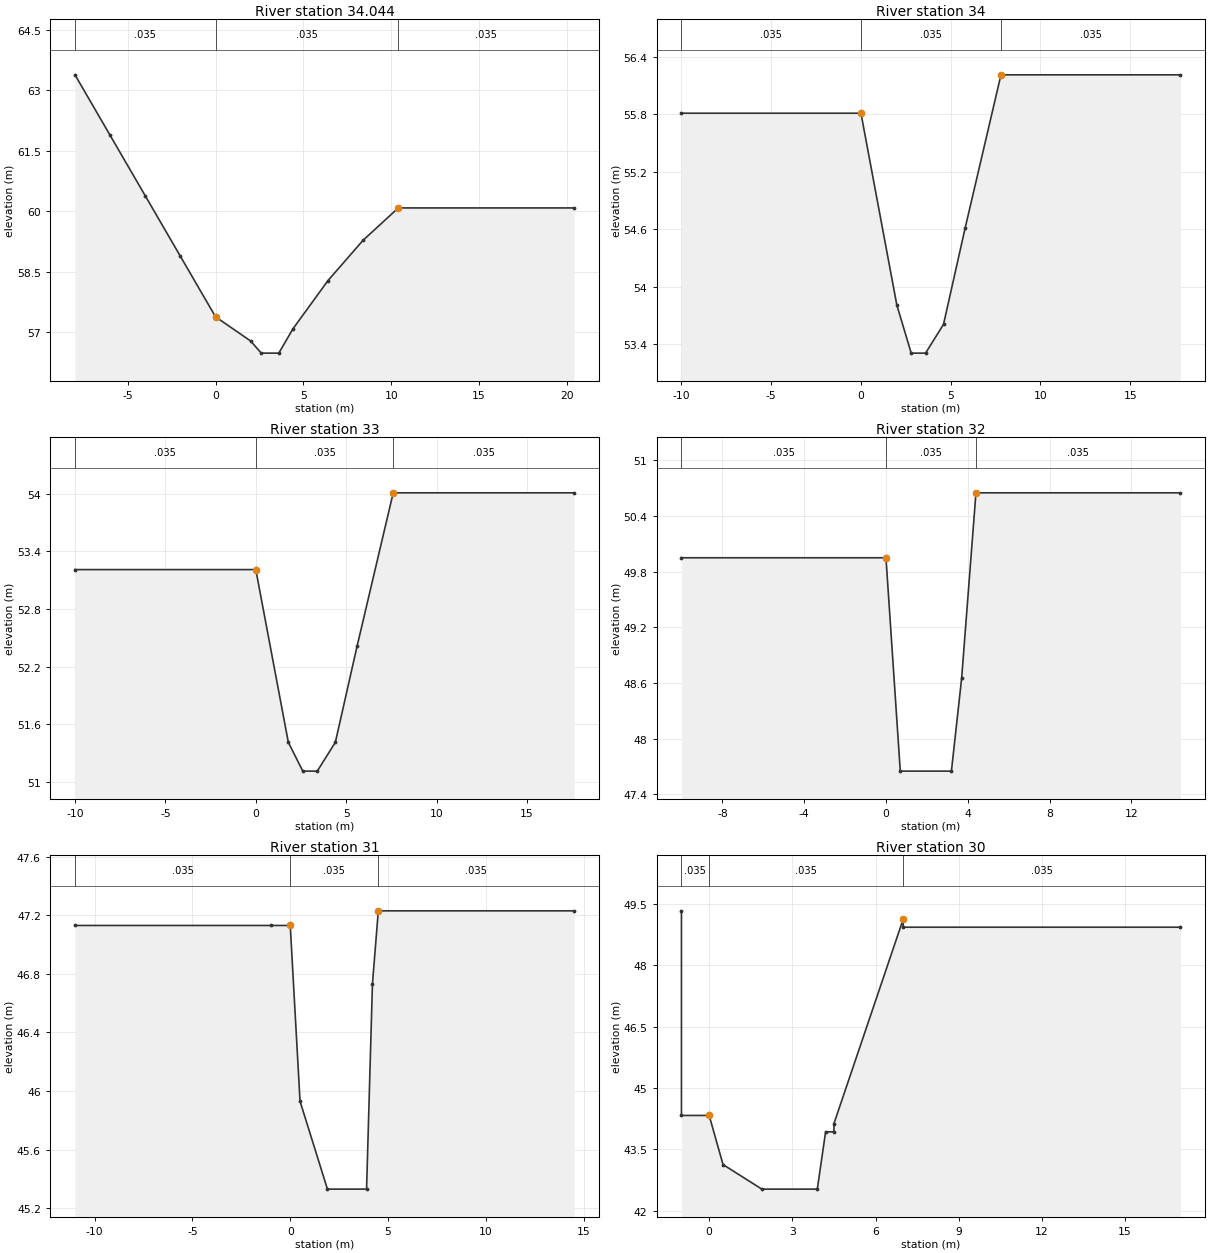
Type RM Length L Ch R = 1 ,34.044  ,44,44,44
#Sta/Elev= 13
      -8   63.38      -6   61.88      -4   60.38      -2   58.88       0   57.38
       2   56.78     2.6   56.48     3.6   56.48     4.4   57.08     6.4   58.28
     8.4   59.28    10.4   60.08    20.4   60.08
#Mann= 3 , 0 , 0
      -8    .035       0       0    .035       0    10.4    .035       0
#XS Ineff= 2 , 0
               0   57.38    10.4           60.08
Permanent Ineff=
       F       F
Bank Sta=0,10.4
XS Rating Curve= 0
Exp/Cntr=.3,.1

Type RM Length L Ch R = 1 ,34      ,50,50,50
#Sta/Elev= 9
     -10   55.81       0   55.81       2   53.81     2.8   53.31     3.6   53.31
     4.6   53.61     5.8   54.61     7.8   56.21    17.8   56.21
#Mann= 3 , 0 , 0
     -10    .035       0       0    .035       0     7.8    .035       0
#XS Ineff= 2 , 0
               0   55.81     7.8           56.21
Permanent Ineff=
       F       F
Bank Sta=0,7.8
XS Rating Curve= 0
Exp/Cntr=.3,.1

Type RM Length L Ch R = 1 ,33      ,50,50,50
#Sta/Elev= 9
     -10   53.21       0   53.21     1.8   51.41     2.6   51.11     3.4   51.11
     4.4   51.41     5.6   52.41     7.6   54.01    17.6   54.01
#Mann= 3 , 0 , 0
     -10    .035       0       0    .035       0     7.6    .035       0
#XS Ineff= 2 , 0
               0   53.21     7.6           54.01
Permanent Ineff=
       F       F
Bank Sta=0,7.6
XS Rating Curve= 0
Exp/Cntr=.3,.1

Type RM Length L Ch R = 1 ,32      ,50,50,50
#Sta/Elev= 7
     -10   49.95       0   49.95      .7   47.65     3.2   47.65     3.7   48.65
     4.4   50.65    14.4   50.65
#Mann= 3 , 0 , 0
     -10    .035       0       0    .035       0     4.4    .035       0
#XS Ineff= 2 , 0
               0   49.95     4.4           50.65
Permanent Ineff=
       F       F
Bank Sta=0,4.4
XS Rating Curve= 0
Exp/Cntr=.3,.1

Type RM Length L Ch R = 1 ,31      ,50,50,50
#Sta/Elev= 9
     -11   47.13      -1   47.13       0   47.13      .5   45.93     1.9   45.33
     3.9   45.33     4.2   46.73     4.5   47.23    14.5   47.23
#Mann= 3 , 0 , 0
     -11    .035       0       0    .035       0     4.5    .035       0
#XS Ineff= 2 , 0
               0   47.13     4.5           47.23
Permanent Ineff=
       F       F
Bank Sta=0,4.5
XS Rating Curve= 0
Exp/Cntr=.3,.1

Type RM Length L Ch R = 1 ,30      ,49,49,49
#Sta/Elev= 12
      -1   49.33      -1   44.33       0   44.33      .5   43.13     1.9   42.53
     3.9   42.53     4.2   43.93     4.5   43.93     4.5   44.13       7   49.13
       7   48.93      17   48.93
#Mann= 3 , 0 , 0
      -1    .035       0       0    .035       0       7    .035       0
#XS Ineff= 2 , 0
               0   44.33       7           48.93
Permanent Ineff=
       F       F
Bank Sta=0,7
XS Rating Curve= 0
Exp/Cntr=.3,.1

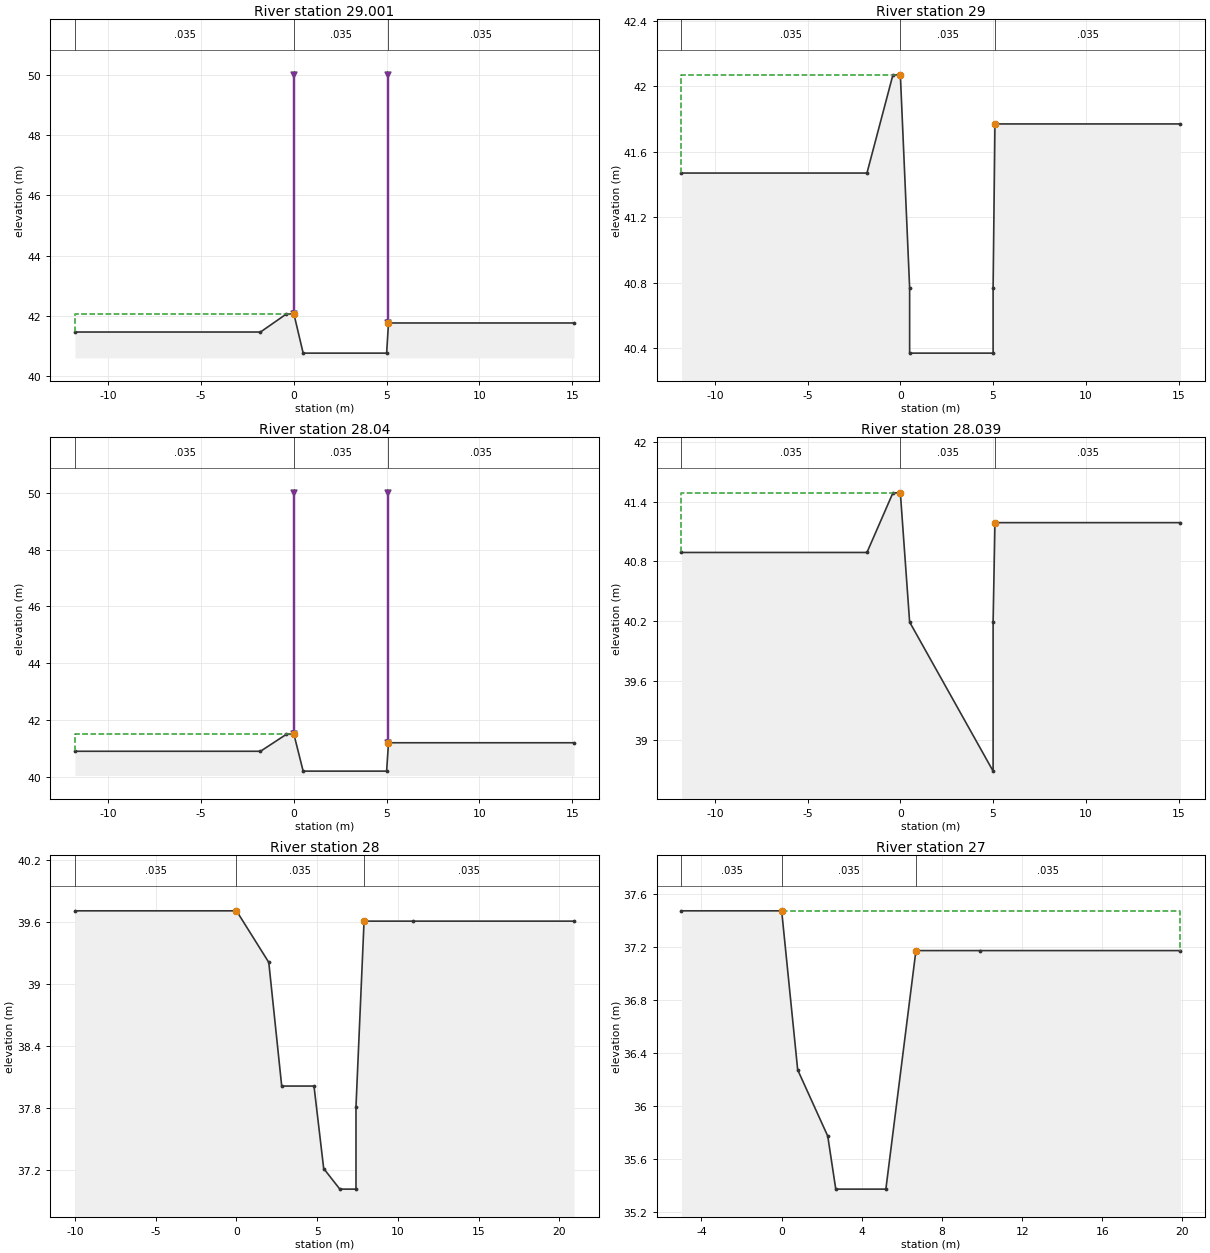
Type RM Length L Ch R = 1 ,29.001  ,1,1,1
#Sta/Elev= 8
   -11.8   41.47    -1.8   41.47     -.4   42.07       0   42.07      .5   40.77
       5   40.77     5.1   41.77    15.1   41.77
#Mann= 3 , 0 , 0
   -11.8    .035       0       0    .035       0     5.1    .035       0
Levee=-1,0,50,-1,5.1,50,,
#XS Ineff= 2 , 0
               0   42.07     5.1           41.77
Permanent Ineff=
       F       F
Bank Sta=0,5.1
XS Rating Curve= 0
Exp/Cntr=.3,.1

Type RM Length L Ch R = 1 ,29      ,10,10,10
#Sta/Elev= 10
   -11.8   41.47    -1.8   41.47     -.4   42.07       0   42.07      .5   40.77
      .5   40.37       5   40.37       5   40.77     5.1   41.77    15.1   41.77
#Mann= 3 , 0 , 0
   -11.8    .035       0       0    .035       0     5.1    .035       0
#XS Ineff= 2 , 0
               0   42.07     5.1           41.77
Permanent Ineff=
       F       F
Bank Sta=0,5.1
XS Rating Curve= 0
Exp/Cntr=.3,.1

Type RM Length L Ch R = 1 ,28.04   ,1,1,1
#Sta/Elev= 8
   -11.8   40.89    -1.8   40.89     -.4   41.49       0   41.49      .5   40.19
       5   40.19     5.1   41.19    15.1   41.19
#Mann= 3 , 0 , 0
   -11.8    .035       0       0    .035       0     5.1    .035       0
Levee=-1,0,50,-1,5.1,50,,
#XS Ineff= 2 , 0
               0   41.49     5.1           41.19
Permanent Ineff=
       F       F
Bank Sta=0,5.1
XS Rating Curve= 0
Exp/Cntr=.3,.1

Type RM Length L Ch R = 1 ,28.039  ,39,39,39
#Sta/Elev= 9
   -11.8   40.89    -1.8   40.89     -.4   41.49       0   41.49      .5   40.19
       5   38.69       5   40.19     5.1   41.19    15.1   41.19
#Mann= 3 , 0 , 0
   -11.8    .035       0       0    .035       0     5.1    .035       0
#XS Ineff= 2 , 0
               0   41.49     5.1           41.19
Permanent Ineff=
       F       F
Bank Sta=0,5.1
XS Rating Curve= 0
Exp/Cntr=.3,.1

Type RM Length L Ch R = 1 ,28      ,50,50,50
#Sta/Elev= 12
     -10   39.71       0   39.71       2   39.21     2.8   38.01     4.8   38.01
     5.4   37.21     6.4   37.01     7.4   37.01     7.4   37.81     7.9   39.61
    10.9   39.61    20.9   39.61
#Mann= 3 , 0 , 0
     -10    .035       0       0    .035       0     7.9    .035       0
#XS Ineff= 2 , 0
               0   39.71     7.9           39.61
Permanent Ineff=
       F       F
Bank Sta=0,7.9
XS Rating Curve= 0
Exp/Cntr=.3,.1

Type RM Length L Ch R = 1 ,27      ,50,50,50
#Sta/Elev= 9
      -5   37.47       0   37.47      .8   36.27     2.3   35.77     2.7   35.37
     5.2   35.37     6.7   37.17     9.9   37.17    19.9   37.17
#Mann= 3 , 0 , 0
      -5    .035       0       0    .035       0     6.7    .035       0
#XS Ineff= 2 , 0
       0       0   37.47     6.7       0   37.17
Permanent Ineff=
       F       F
Bank Sta=0,6.7
XS Rating Curve= 0
Exp/Cntr=.3,.1

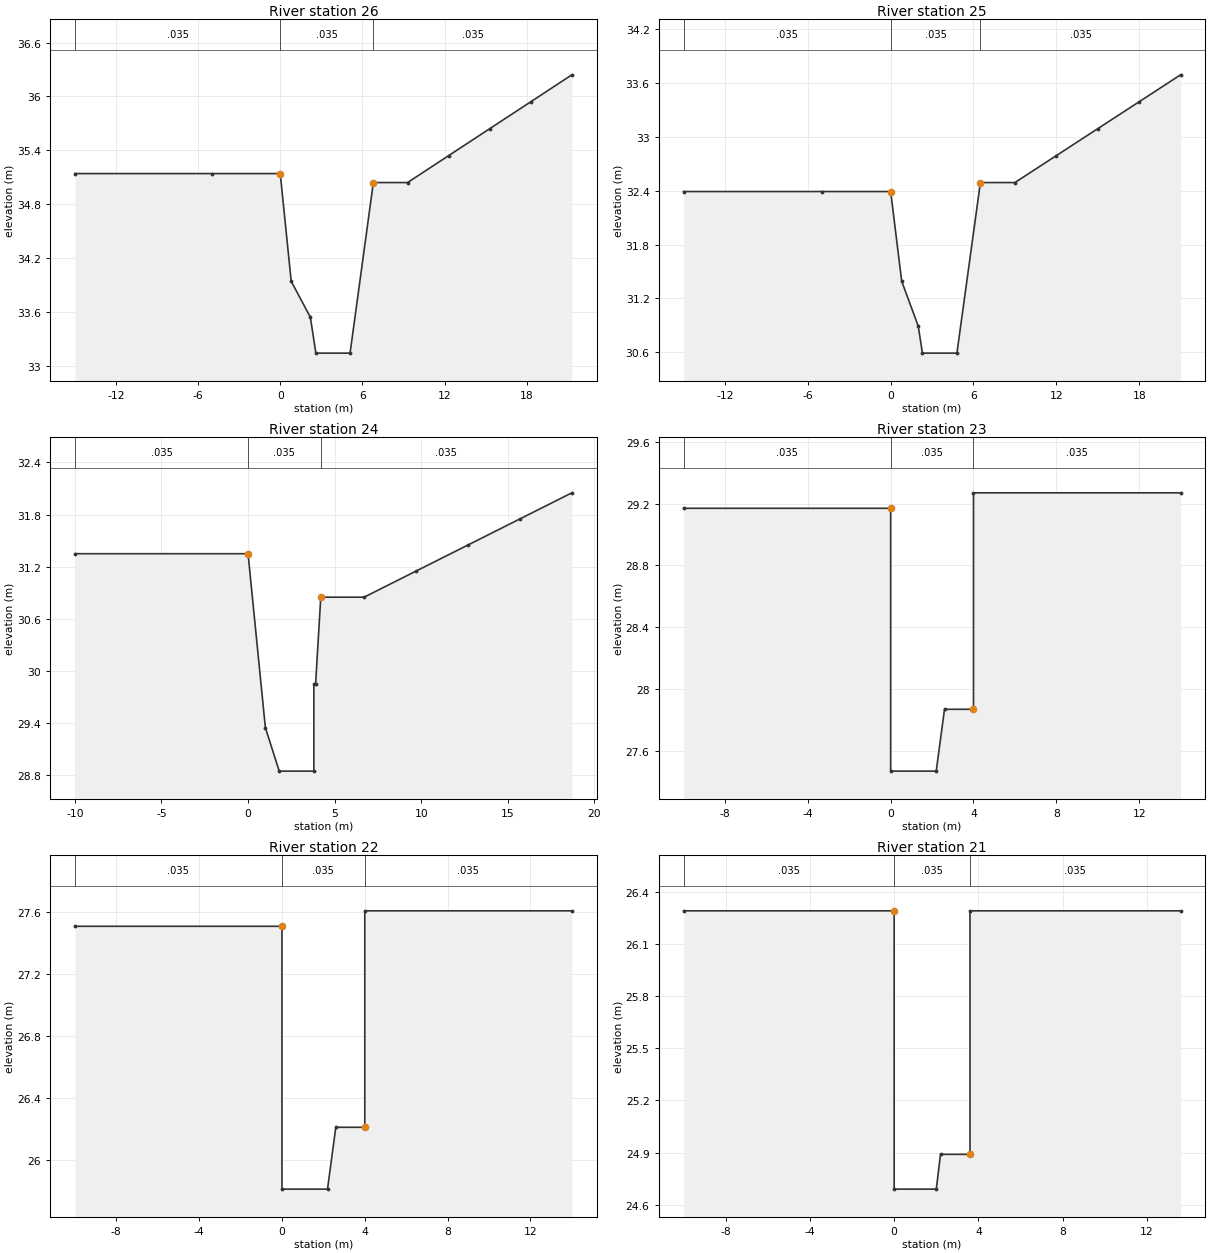
Type RM Length L Ch R = 1 ,26      ,50,50,50
#Sta/Elev= 13
     -15   35.14      -5   35.14       0   35.14      .8   33.94     2.2   33.54
     2.6   33.14     5.1   33.14     6.8   35.04     9.3   35.04    12.3   35.34
    15.3   35.64    18.3   35.94    21.3   36.24
#Mann= 3 , 0 , 0
     -15    .035       0       0    .035       0     6.8    .035       0
#XS Ineff= 2 , 0
               0   35.14     6.8           35.04
Permanent Ineff=
       F       F
Bank Sta=0,6.8
XS Rating Curve= 0
Exp/Cntr=.3,.1

Type RM Length L Ch R = 1 ,25      ,50,50,50
#Sta/Elev= 13
     -15   32.39      -5   32.39       0   32.39      .8   31.39       2   30.89
     2.3   30.59     4.8   30.59     6.5   32.49       9   32.49      12   32.79
      15   33.09      18   33.39      21   33.69
#Mann= 3 , 0 , 0
     -15    .035       0       0    .035       0     6.5    .035       0
#XS Ineff= 2 , 0
               0   32.39     6.5           32.49
Permanent Ineff=
       F       F
Bank Sta=0,6.5
XS Rating Curve= 0
Exp/Cntr=.3,.1

Type RM Length L Ch R = 1 ,24      ,50,50,50
#Sta/Elev= 13
     -10   31.35       0   31.35       1   29.35     1.8   28.85     3.8   28.85
     3.8   29.85     3.9   29.85     4.2   30.85     6.7   30.85     9.7   31.15
    12.7   31.45    15.7   31.75    18.7   32.05
#Mann= 3 , 0 , 0
     -10    .035       0       0    .035       0     4.2    .035       0
#XS Ineff= 2 , 0
               0   31.35     4.2           30.85
Permanent Ineff=
       F       F
Bank Sta=0,4.2
XS Rating Curve= 0
Exp/Cntr=.3,.1

Type RM Length L Ch R = 1 ,23      ,50,50,50
#Sta/Elev= 8
     -10   29.17       0   29.17       0   27.47     2.2   27.47     2.6   27.87
       4   27.87       4   29.27      14   29.27
#Mann= 3 , 0 , 0
     -10    .035       0       0    .035       0       4    .035       0
Bank Sta=0,4
XS Rating Curve= 0
Exp/Cntr=.3,.1

Type RM Length L Ch R = 1 ,22      ,50,50,50
#Sta/Elev= 8
     -10   27.51       0   27.51       0   25.81     2.2   25.81     2.6   26.21
       4   26.21       4   27.61      14   27.61
#Mann= 3 , 0 , 0
     -10    .035       0       0    .035       0       4    .035       0
Bank Sta=0,4
XS Rating Curve= 0
Exp/Cntr=.3,.1

Type RM Length L Ch R = 1 ,21      ,11,11,11
#Sta/Elev= 8
     -10   26.29       0   26.29       0   24.69       2   24.69     2.2   24.89
     3.6   24.89     3.6   26.29    13.6   26.29
#Mann= 3 , 0 , 0
     -10    .035       0       0    .035       0     3.6    .035       0
Bank Sta=0,3.6
XS Rating Curve= 0
Exp/Cntr=.3,.1

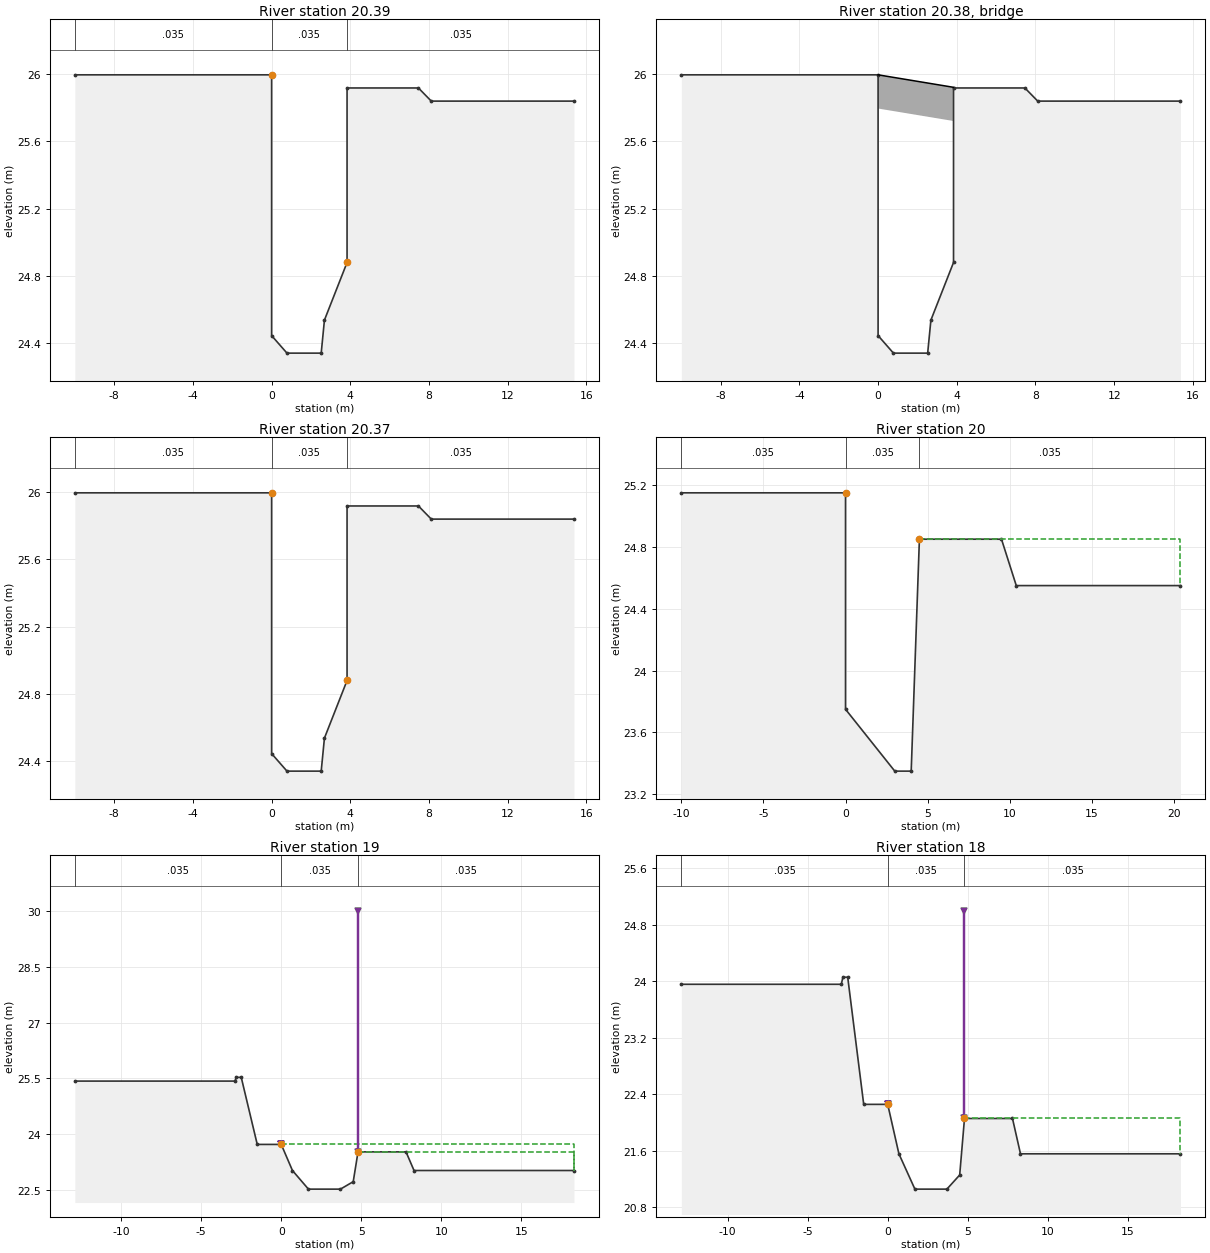
Type RM Length L Ch R = 1 ,20.39   ,2,2,2
#Sta/Elev= 11
     -10  25.994       0  25.994       0  24.446     .78  24.342    2.52  24.342
   2.684  24.538   3.834   24.88   3.834  25.916   7.461  25.916   8.114  25.838
  15.368  25.838
#Mann= 3 , 0 , 0
     -10    .035       0       0    .035       0   3.834    .035       0
Bank Sta=0,3.834
XS Rating Curve= 0
Exp/Cntr=.3,.1

Type RM Length L Ch R = 3 ,20.38   ,,,
Bridge Culvert--1,0,-1,-1, 0
Deck Dist Width WeirC Skew NumUp NumDn MinLoCord MaxHiCord MaxSubmerge Is_Ogee
.01,1.9,1.44,0, 2, 2, , , .95, 0, 0,0,,
       0    3.83
  25.994   25.92
  25.794   25.72
       0    3.83
  25.994   25.92
  25.794   25.72
BR Coef=-1 , 1 , 0 ,, 0 ,,,.8,-1,1.2,0,
WSPro=,,,, 1 ,,,, 0 ,,,, 0 ,,,,-1 ,-1 ,-1 , 0 , 0 , 0 , 0 , 0
BC Design=,, 0 ,, 0 ,,,,,,

Type RM Length L Ch R = 1 ,20.37   ,37,37,37
#Sta/Elev= 11
     -10  25.994       0  25.994       0  24.446     .78  24.342    2.52  24.342
   2.684  24.538   3.834   24.88   3.834  25.916   7.461  25.916   8.114  25.838
  15.368  25.838
#Mann= 3 , 0 , 0
     -10    .035       0       0    .035       0   3.834    .035       0
Bank Sta=0,3.834
XS Rating Curve= 0
Exp/Cntr=.3,.1

Type RM Length L Ch R = 1 ,20      ,50,50,50
#Sta/Elev= 9
     -10   25.15       0   25.15       0   23.75       3   23.35       4   23.35
     4.5   24.85     9.5   24.85    10.4   24.55    20.4   24.55
#Mann= 3 , 0 , 0
     -10    .035       0       0    .035       0     4.5    .035       0
#XS Ineff= 2 , 0
               0   25.15     4.5           24.85
Permanent Ineff=
       F       F
Bank Sta=0,4.5
XS Rating Curve= 0
Exp/Cntr=.3,.1

Type RM Length L Ch R = 1 ,19      ,50,50,50
#Sta/Elev= 14
   -12.9   25.43    -2.9   25.43    -2.8   25.53    -2.5   25.53    -1.5   23.73
       0   23.73      .7   23.03     1.7   22.53     3.7   22.53     4.5   22.73
     4.8   23.53     7.8   23.53     8.3   23.03    18.3   23.03
#Mann= 3 , 0 , 0
   -12.9    .035       0       0    .035       0     4.8    .035       0
Levee=-1,0,23.73,-1,4.8,30,,
#XS Ineff= 2 , 0
       0       0   23.73     4.8       0   23.53
Permanent Ineff=
       F       F
Bank Sta=0,4.8
XS Rating Curve= 0
Exp/Cntr=.3,.1

Type RM Length L Ch R = 1 ,18      ,50,50,50
#Sta/Elev= 14
   -12.9   23.96    -2.9   23.96    -2.8   24.06    -2.5   24.06    -1.5   22.26
       0   22.26      .7   21.56     1.7   21.06     3.7   21.06     4.5   21.26
     4.8   22.06     7.8   22.06     8.3   21.56    18.3   21.56
#Mann= 3 , 0 , 0
   -12.9    .035       0       0    .035       0     4.8    .035       0
Levee=-1,0,22.26,-1,4.8,25,,
#XS Ineff= 2 , 0
               0   22.26     4.8           22.06
Permanent Ineff=
       F       F
Bank Sta=0,4.8
XS Rating Curve= 0
Exp/Cntr=.3,.1

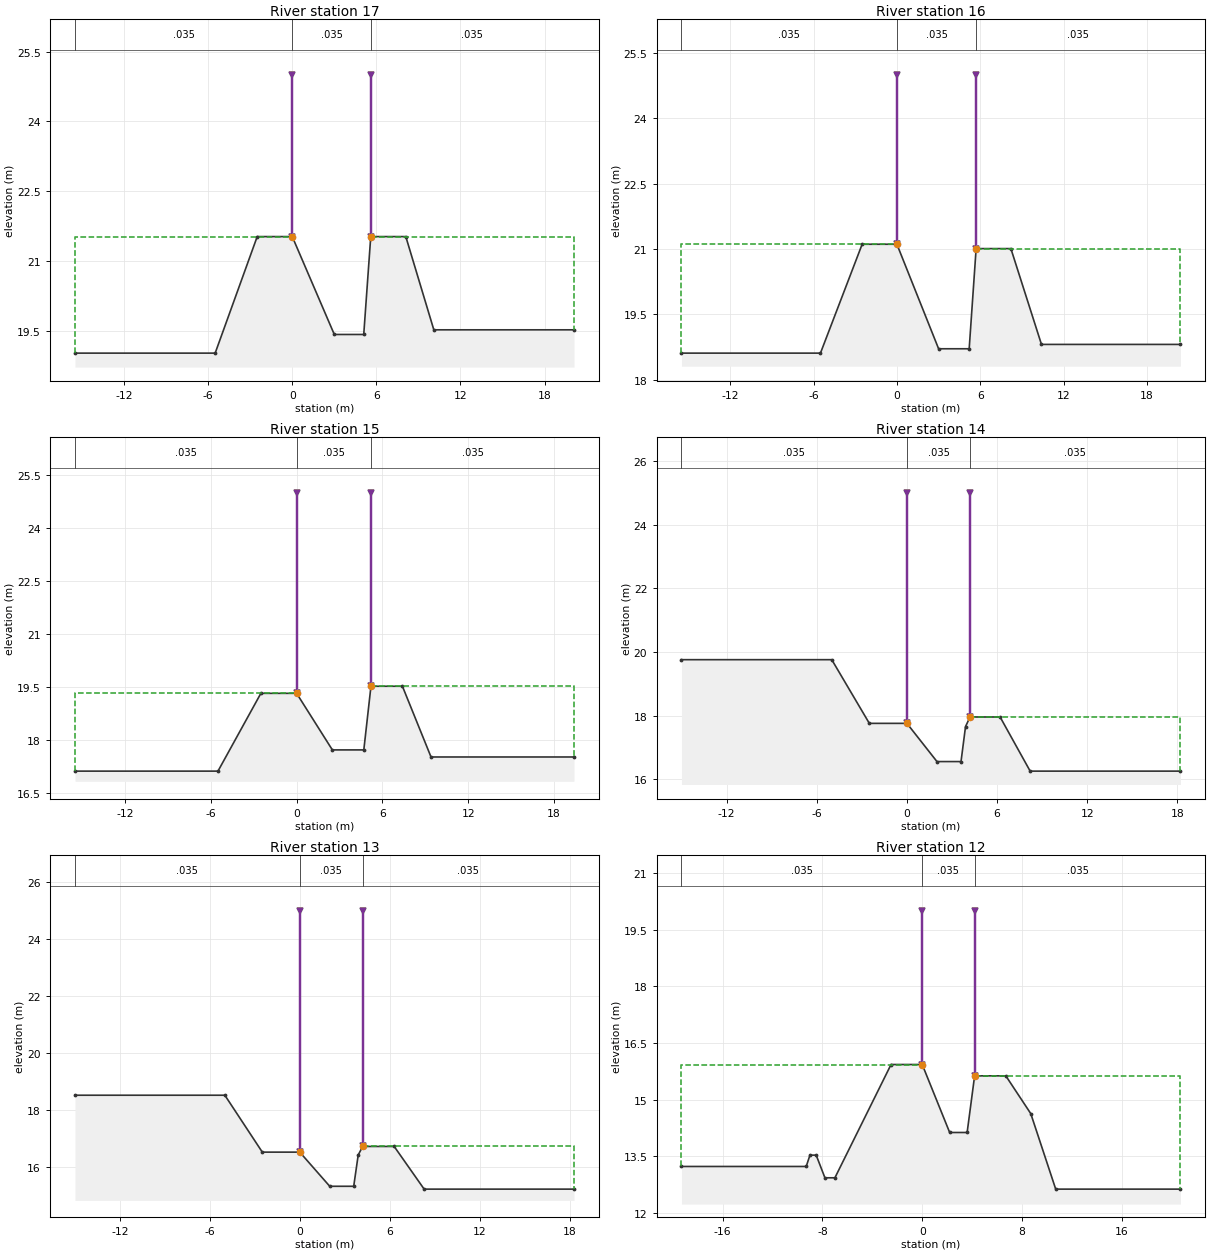
Type RM Length L Ch R = 1 ,17      ,50,50,50
#Sta/Elev= 10
   -15.5   19.03    -5.5   19.03    -2.5   21.53       0   21.53       3   19.43
     5.1   19.43     5.6   21.53     8.1   21.53    10.1   19.53    20.1   19.53
#Mann= 3 , 0 , 0
   -15.5    .035       0       0    .035       0     5.6    .035       0
Levee=-1,0,25,-1,5.6,25,,
#XS Ineff= 2 , 0
               0   21.53     5.6           21.53
Permanent Ineff=
       F       F
Bank Sta=0,5.6
XS Rating Curve= 0
Exp/Cntr=.3,.1

Type RM Length L Ch R = 1 ,16      ,50,50,50
#Sta/Elev= 10
   -15.5   18.61    -5.5   18.61    -2.5   21.11       0   21.11       3   18.71
     5.2   18.71     5.7   21.01     8.2   21.01    10.4   18.81    20.4   18.81
#Mann= 3 , 0 , 0
   -15.5    .035       0       0    .035       0     5.7    .035       0
Levee=-1,0,25,-1,5.7,25,,
#XS Ineff= 2 , 0
               0   21.11     5.7           21.01
Permanent Ineff=
       F       F
Bank Sta=0,5.7
XS Rating Curve= 0
Exp/Cntr=.3,.1

Type RM Length L Ch R = 1 ,15      ,50,50,50
#Sta/Elev= 10
   -15.5   17.13    -5.5   17.13    -2.5   19.33       0   19.33     2.5   17.73
     4.7   17.73     5.2   19.53     7.4   19.53     9.4   17.53    19.4   17.53
#Mann= 3 , 0 , 0
   -15.5    .035       0       0    .035       0     5.2    .035       0
Levee=-1,0,25,-1,5.2,25,,
#XS Ineff= 2 , 0
               0   19.33     5.2           19.53
Permanent Ineff=
       F       F
Bank Sta=0,5.2
XS Rating Curve= 0
Exp/Cntr=.3,.1

Type RM Length L Ch R = 1 ,14      ,50,50,50
#Sta/Elev= 11
     -15   19.76      -5   19.76    -2.5   17.76       0   17.76       2   16.56
     3.6   16.56     3.9   17.66     4.2   17.96     6.2   17.96     8.2   16.26
    18.2   16.26
#Mann= 3 , 0 , 0
     -15    .035       0       0    .035       0     4.2    .035       0
Levee=-1,0,25,-1,4.2,25,,
#XS Ineff= 2 , 0
               0   17.76     4.2           17.96
Permanent Ineff=
       F       F
Bank Sta=0,4.2
XS Rating Curve= 0
Exp/Cntr=.3,.1

Type RM Length L Ch R = 1 ,13      ,50,50,50
#Sta/Elev= 11
     -15   18.52      -5   18.52    -2.5   16.52       0   16.52       2   15.32
     3.6   15.32     3.9   16.42     4.2   16.72     6.3   16.72     8.3   15.22
    18.3   15.22
#Mann= 3 , 0 , 0
     -15    .035       0       0    .035       0     4.2    .035       0
Levee=-1,0,25,-1,4.2,25,,
#XS Ineff= 2 , 0
               0   16.52     4.2           16.72
Permanent Ineff=
       F       F
Bank Sta=0,4.2
XS Rating Curve= 0
Exp/Cntr=.3,.1

Type RM Length L Ch R = 1 ,12      ,50,50,50
#Sta/Elev= 15
   -19.3   13.23    -9.3   13.23      -9   13.53    -8.5   13.53    -7.8   12.93
      -7   12.93    -2.5   15.93       0   15.93     2.2   14.13     3.6   14.13
     4.2   15.63     6.7   15.63     8.7   14.63    10.7   12.63    20.7   12.63
#Mann= 3 , 0 , 0
   -19.3    .035       0       0    .035       0     4.2    .035       0
Levee=-1,0,20,-1,4.2,20,,
#XS Ineff= 2 , 0
               0   15.93     4.2           15.63
Permanent Ineff=
       F       F
Bank Sta=0,4.2
XS Rating Curve= 0
Exp/Cntr=.3,.1

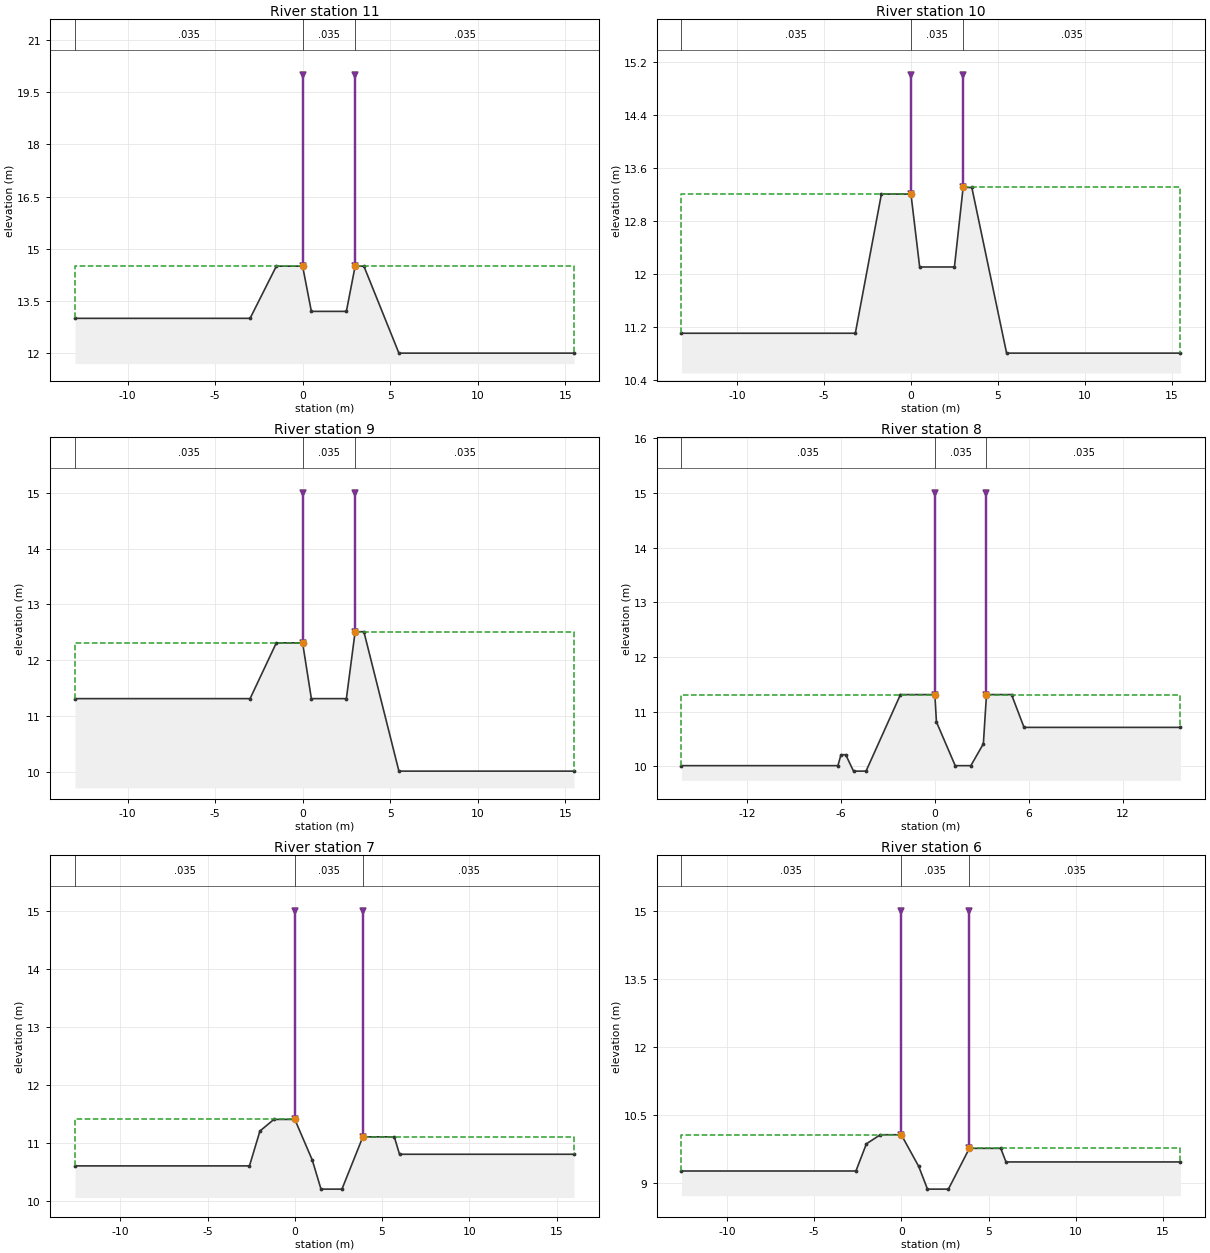
Type RM Length L Ch R = 1 ,11      ,50,50,50
#Sta/Elev= 10
     -13      13      -3      13    -1.5    14.5       0    14.5      .5    13.2
     2.5    13.2       3    14.5     3.5    14.5     5.5      12    15.5      12
#Mann= 3 , 0 , 0
     -13    .035       0       0    .035       0       3    .035       0
Levee=-1,0,20,-1,3,20,,
#XS Ineff= 2 , 0
               0    14.5       3            14.5
Permanent Ineff=
       F       F
Bank Sta=0,3
XS Rating Curve= 0
Exp/Cntr=.3,.1

Type RM Length L Ch R = 1 ,10      ,50,50,50
#Sta/Elev= 10
   -13.2    11.1    -3.2    11.1    -1.7    13.2       0    13.2      .5    12.1
     2.5    12.1       3    13.3     3.5    13.3     5.5    10.8    15.5    10.8
#Mann= 3 , 0 , 0
   -13.2    .035       0       0    .035       0       3    .035       0
Levee=-1,0,15,-1,3,15,,
#XS Ineff= 2 , 0
               0    13.2       3            13.3
Permanent Ineff=
       F       F
Bank Sta=0,3
XS Rating Curve= 0
Exp/Cntr=.3,.1

Type RM Length L Ch R = 1 ,9       ,50,50,50
#Sta/Elev= 10
     -13   11.31      -3   11.31    -1.5   12.31       0   12.31      .5   11.31
     2.5   11.31       3   12.51     3.5   12.51     5.5   10.01    15.5   10.01
#Mann= 3 , 0 , 0
     -13    .035       0       0    .035       0       3    .035       0
Levee=-1,0,15,-1,3,15,,
#XS Ineff= 2 , 0
               0   12.31       3           12.51
Permanent Ineff=
       F       F
Bank Sta=0,3
XS Rating Curve= 0
Exp/Cntr=.3,.1

Type RM Length L Ch R = 1 ,8       ,50,50,50
#Sta/Elev= 16
   -16.2   10.01    -6.2   10.01      -6   10.21    -5.7   10.21    -5.2    9.91
    -4.4    9.91    -2.2   11.31       0   11.31      .1   10.81     1.3   10.01
     2.3   10.01     3.1   10.41     3.3   11.31     4.9   11.31     5.7   10.71
    15.7   10.71
#Mann= 3 , 0 , 0
   -16.2    .035       0       0    .035       0     3.3    .035       0
Levee=-1,0,15,-1,3.3,15,,
#XS Ineff= 2 , 0
               0   11.31     3.3           11.31
Permanent Ineff=
       F       F
Bank Sta=0,3.3
XS Rating Curve= 0
Exp/Cntr=.3,.1

Type RM Length L Ch R = 1 ,7       ,50,50,50
#Sta/Elev= 12
   -12.6   10.61    -2.6   10.61      -2   11.21    -1.2   11.41       0   11.41
       1   10.71     1.5   10.21     2.7   10.21     3.9   11.11     5.7   11.11
       6   10.81      16   10.81
#Mann= 3 , 0 , 0
   -12.6    .035       0       0    .035       0     3.9    .035       0
Levee=-1,0,15,-1,3.9,15,,
#XS Ineff= 2 , 0
               0   11.41     3.9           11.11
Permanent Ineff=
       F       F
Bank Sta=0,3.9
XS Rating Curve= 0
Exp/Cntr=.3,.1

Type RM Length L Ch R = 1 ,6       ,50,50,50
#Sta/Elev= 12
   -12.6    9.26    -2.6    9.26      -2    9.86    -1.2   10.06       0   10.06
       1    9.36     1.5    8.86     2.7    8.86     3.9    9.76     5.7    9.76
       6    9.46      16    9.46
#Mann= 3 , 0 , 0
   -12.6    .035       0       0    .035       0     3.9    .035       0
Levee=-1,0,15,-1,3.9,15,,
#XS Ineff= 2 , 0
               0   10.06     3.9            9.76
Permanent Ineff=
       F       F
Bank Sta=0,3.9
XS Rating Curve= 0
Exp/Cntr=.3,.1

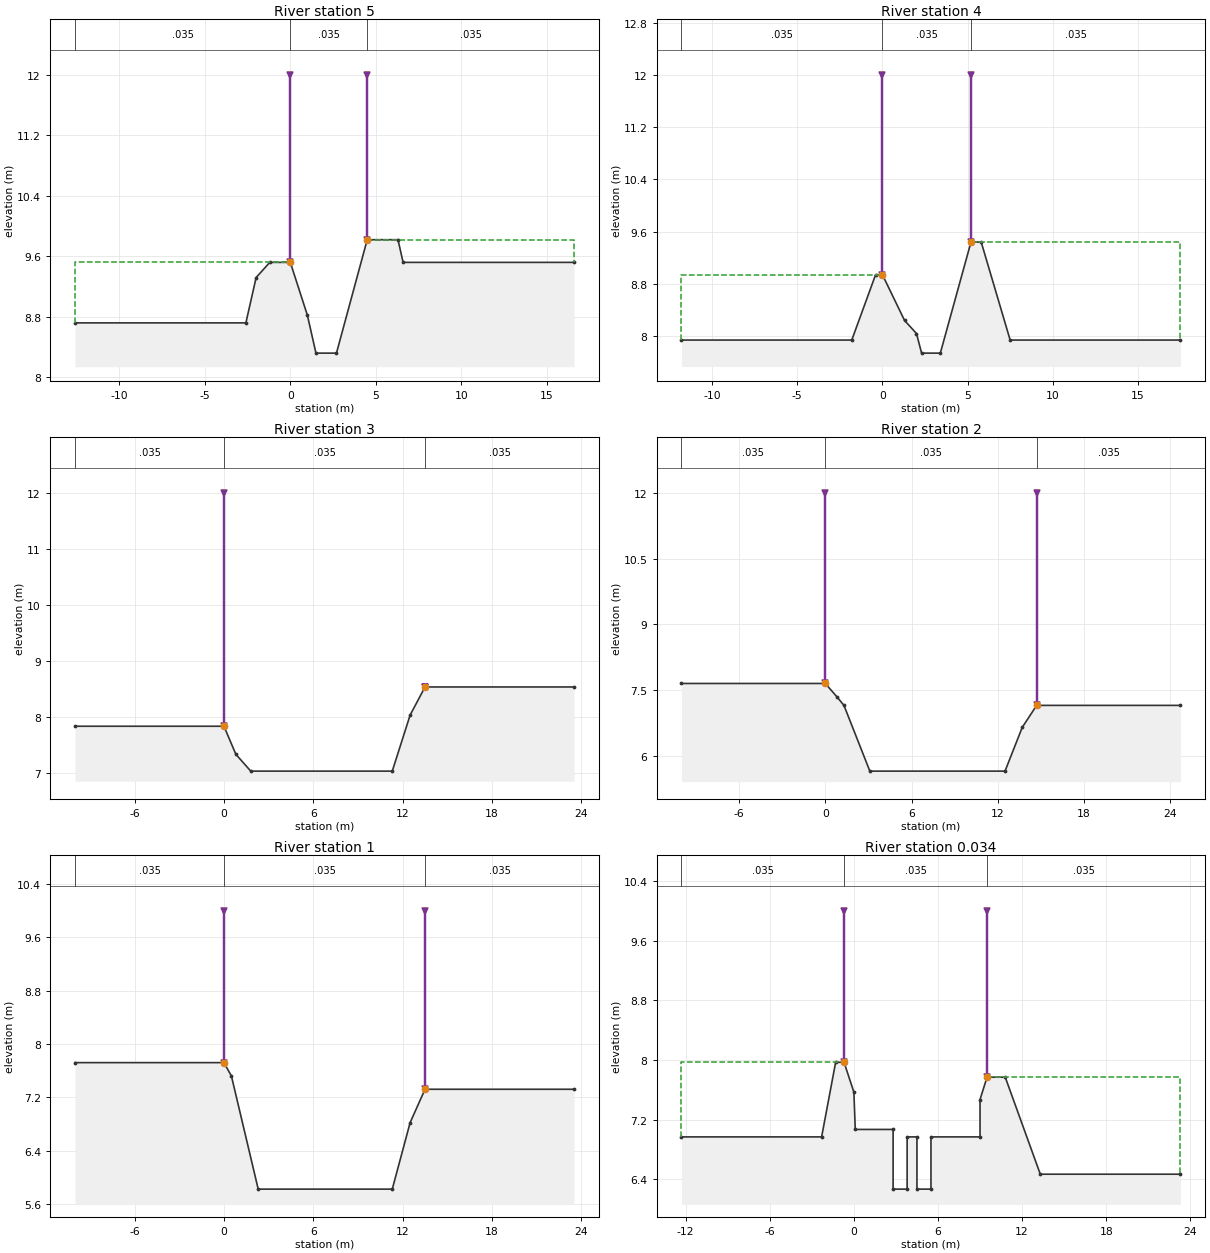
Type RM Length L Ch R = 1 ,5       ,50,50,50
#Sta/Elev= 12
   -12.6    8.72    -2.6    8.72      -2    9.32    -1.2    9.52       0    9.52
       1    8.82     1.5    8.32     2.7    8.32     4.5    9.82     6.3    9.82
     6.6    9.52    16.6    9.52
#Mann= 3 , 0 , 0
   -12.6    .035       0       0    .035       0     4.5    .035       0
Levee=-1,0,12,-1,4.5,12,,
#XS Ineff= 2 , 0
               0    9.52     4.5            9.82
Permanent Ineff=
       F       F
Bank Sta=0,4.5
XS Rating Curve= 0
Exp/Cntr=.3,.1

Type RM Length L Ch R = 1 ,4       ,50,50,50
#Sta/Elev= 12
   -11.8    7.94    -1.8    7.94     -.4    8.94       0    8.94     1.3    8.24
       2    8.04     2.3    7.74     3.4    7.74     5.2    9.44     5.8    9.44
     7.5    7.94    17.5    7.94
#Mann= 3 , 0 , 0
   -11.8    .035       0       0    .035       0     5.2    .035       0
Levee=-1,0,12,-1,5.2,12,,
#XS Ineff= 2 , 0
               0    8.94     5.2            9.44
Permanent Ineff=
       F       F
Bank Sta=0,5.2
XS Rating Curve= 0
Exp/Cntr=.3,.1

Type RM Length L Ch R = 1 ,3       ,50,50,50
#Sta/Elev= 8
     -10    7.84       0    7.84      .8    7.34     1.8    7.04    11.3    7.04
    12.5    8.04    13.5    8.54    23.5    8.54
#Mann= 3 , 0 , 0
     -10    .035       0       0    .035       0    13.5    .035       0
Levee=-1,0,12,-1,13.5,8.54,,
#XS Ineff= 2 , 0
               0    7.84    13.5            8.54
Permanent Ineff=
       F       F
Bank Sta=0,13.5
XS Rating Curve= 0
Exp/Cntr=.3,.1

Type RM Length L Ch R = 1 ,2       ,50,50,50
#Sta/Elev= 9
     -10    7.65       0    7.65      .8    7.35     1.3    7.15     3.1    5.65
    12.5    5.65    13.7    6.65    14.7    7.15    24.7    7.15
#Mann= 3 , 0 , 0
     -10    .035       0       0    .035       0    14.7    .035       0
Levee=-1,0,12,-1,14.7,12,,
#XS Ineff= 2 , 0
               0    7.65    14.7            7.15
Permanent Ineff=
       F       F
Bank Sta=0,14.7
XS Rating Curve= 0
Exp/Cntr=.3,.1

Type RM Length L Ch R = 1 ,1       ,16,16,16
#Sta/Elev= 8
     -10    7.72       0    7.72      .5    7.52     2.3    5.82    11.3    5.82
    12.5    6.82    13.5    7.32    23.5    7.32
#Mann= 3 , 0 , 0
     -10    .035       0       0    .035       0    13.5    .035       0
Levee=-1,0,10,-1,13.5,10,,
#XS Ineff= 2 , 0
               0    7.72    13.5            7.32
Permanent Ineff=
       F       F
Bank Sta=0,13.5
XS Rating Curve= 0
Exp/Cntr=.3,.1

Type RM Length L Ch R = 1 ,0.034   ,3,3,3
#Sta/Elev= 20
   -12.3    6.97    -2.3    6.97    -1.3    7.97     -.7    7.97       0    7.57
      .1    7.07     2.8    7.07     2.8    6.27     3.8    6.27     3.8    6.97
     4.5    6.97     4.5    6.27     5.5    6.27     5.5    6.97       9    6.97
       9    7.47     9.5    7.77    10.8    7.77    13.3    6.47    23.3    6.47
#Mann= 3 , 0 , 0
   -12.3    .035       0     -.7    .035       0     9.5    .035       0
Levee=-1,-.7,10,-1,9.5,10,,
#XS Ineff= 2 , 0
             -.7    7.97     9.5            7.77
Permanent Ineff=
       F       F
Bank Sta=-.7,9.5
XS Rating Curve= 0
Exp/Cntr=.3,.1

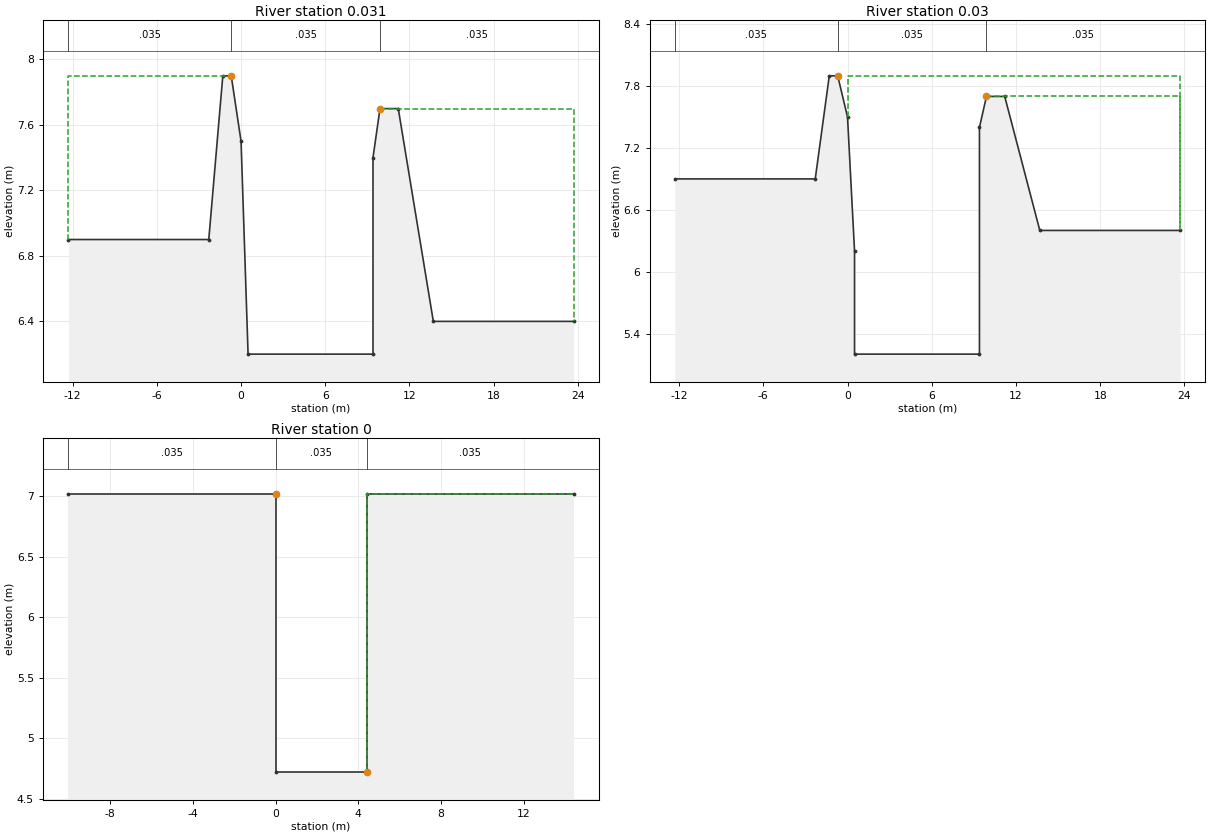
Type RM Length L Ch R = 1 ,0.031   ,1,1,1
#Sta/Elev= 12
   -12.3     6.9    -2.3     6.9    -1.3     7.9     -.7     7.9       0     7.5
      .5     6.2     9.4     6.2     9.4     7.4     9.9     7.7    11.2     7.7
    13.7     6.4    23.7     6.4
#Mann= 3 , 0 , 0
   -12.3    .035       0     -.7    .035       0     9.9    .035       0
#XS Ineff= 2 , 0
             -.7     7.9     9.9             7.7
Permanent Ineff=
       F       F
Bank Sta=-.7,9.9
XS Rating Curve= 0
Exp/Cntr=.3,.1

Type RM Length L Ch R = 1 ,0.03    ,30,30,30
#Sta/Elev= 13
   -12.3     6.9    -2.3     6.9    -1.3     7.9     -.7     7.9       0     7.5
      .5     6.2      .5     5.2     9.4     5.2     9.4     7.4     9.9     7.7
    11.2     7.7    13.7     6.4    23.7     6.4
#Mann= 3 , 0 , 0
   -12.3    .035       0     -.7    .035       0     9.9    .035       0
#XS Ineff= 2 , 0
       0     -.7     7.9     9.9       0     7.7
Permanent Ineff=
       F       F
Bank Sta=-.7,9.9
XS Rating Curve= 0
Exp/Cntr=.3,.1

Type RM Length L Ch R = 1 ,0       ,0,0,0
#Sta/Elev= 6
     -10    7.02       0    7.02       0    4.72     4.4    4.72     4.4    7.02
    14.4    7.02
#Mann= 3 , 0 , 0
     -10    .035       0       0    .035       0     4.4    .035       0
#XS Ineff= 2 , 0
               0    7.02     4.4            7.02
Permanent Ineff=
       F       F
Bank Sta=0,4.4
XS Rating Curve= 0
Exp/Cntr=.3,.1

Chan Stop Cuts=-1