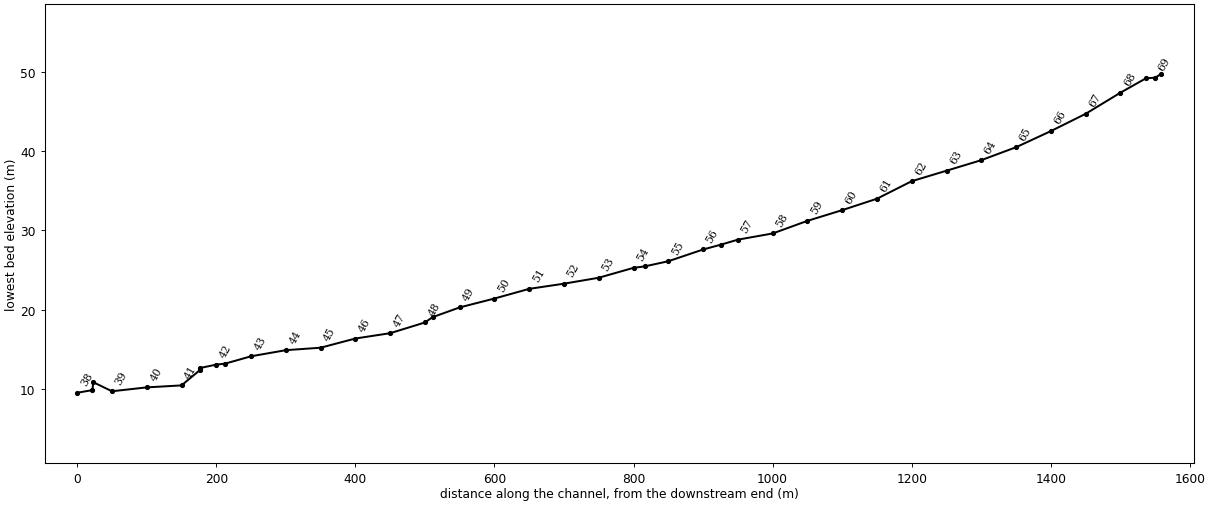
--- SHC.prj (project) ---

Proj Title=songhak-ch
Current Plan=p01
Default Exp/Contr=.3,.1
SI Units
Geom File=g01
Flow File=f01
Plan File=p01
Y Axis Title=Elevation
X Axis Title(PF)=Main Channel Distance
X Axis Title(XS)=Station
BEGIN DESCRIPTION:
           BACK WATER COMPUTATION
      APPLICATION OF HEC-2 BY Samju Construction Engineering
      songhak-ch: 10,20,30,50,80 yr
END DESCRIPTION:
DSS Export Rating Curves= 0
DSS Export Rating Curve Sorted= 0
DSS Export Volume Flow Curves= 0
DXF OffsetX= 0
DXF OffsetY= 0
DXF ScaleX= 1
DXF ScaleY= 10

--- SHC.p01 (plan) ---

Plan Title=Imported Plan 01
Version=Version 3.0.1  Mar 2001
Short Identifier=Imported Pla
Geom File=g01
Flow File=f01
Subcritical Flow
K Sum by GR= 0
Std Step Tol= 0.003
Critical Tol= 0.003
Num of Std Step Trials= 20
Max Error Tol= 0.1
Flow Tol Ratio= 0.001
Split Flow NTrial= 30
Split Flow Tol= 0.02
Split Flow Ratio= 0.02
Log Output Level= 0
Friction Slope Method= 1
Unsteady Friction Slope Method= 2
Parabolic Critical Depth
Global Vel Dist= 0 , 0 , 0
Global Log Level= 0
CheckData=True
Encroach Param=-1 ,0,0, 0
Computation Interval=1HOUR
Output Interval=1HOUR
Run HTab= 0
Run UNet= 0
Run PostProcess= 0
UNET Theta= 1
UNET ZTol= 0.02
UNET ZSATol= 0.1
UNET MxIter= 20
UNET MaxInSteps= 20
UNET DtIC= 0
UNET DtMin= 0
UNET MaxCRTS= 20
UNET WFStab= 2
UNET SFStab= 1
UNET WFX= 1
UNET SFX= 1
UNET Convert EG Bridges=-1
UNET Use Existing IB Tables=-1
Instantaneous Interval=1HOUR
Write IC File= 0
Write Velocity= 0
Write Detailed= 0

--- SHC.f01 (steady flow) ---

Flow Title=Imported Flow 01
Version=Version 3.0.1  Mar 2001
Number of Profiles= 5
Profile Names=10YR,20YR,30YR,50YR,80YR
River Rch & RM=RIVER-1,Reach-1         ,69.009
   14.89    16.4   17.29    18.4   19.43
River Rch & RM=RIVER-1,Reach-1         ,60
   34.84   38.39   40.47   43.09    45.5
River Rch & RM=RIVER-1,Reach-1         ,25
   44.24   48.79   51.45   54.81   57.89
River Rch & RM=SONGHAK,SONGHAK         ,69.009
   14.89    16.4   17.29    18.4   19.43
River Rch & RM=SONGHAK,SONGHAK         ,60
   34.84   38.39   40.47   43.09    45.5
River Rch & RM=SONGHAK,SONGHAK         ,25
   44.24   48.79   51.45   54.81   57.89
Boundary for River Rch & Prof#=SONGHAK,SONGHAK         , 1
Up Type= 0
Dn Type= 3
Dn Slope=.014
Boundary for River Rch & Prof#=SONGHAK,SONGHAK         , 2
Up Type= 0
Dn Type= 3
Dn Slope=.014
Boundary for River Rch & Prof#=SONGHAK,SONGHAK         , 3
Up Type= 0
Dn Type= 3
Dn Slope=.014
Boundary for River Rch & Prof#=SONGHAK,SONGHAK         , 4
Up Type= 0
Dn Type= 3
Dn Slope=.014
Boundary for River Rch & Prof#=SONGHAK,SONGHAK         , 5
Up Type= 0
Dn Type= 3
Dn Slope=.014
DSS Import GetInterval= 0
DSS Import GetPeak= 0
DSS Import FillOption= 0

--- SHC.g01 (geometry) ---

Geom Title=Imported Geom 01
Version=Version 3.0.1  Mar 2001

River Reach=SONGHAK         ,SONGHAK
Reach XY= 2
              .5             .95              .5             .05

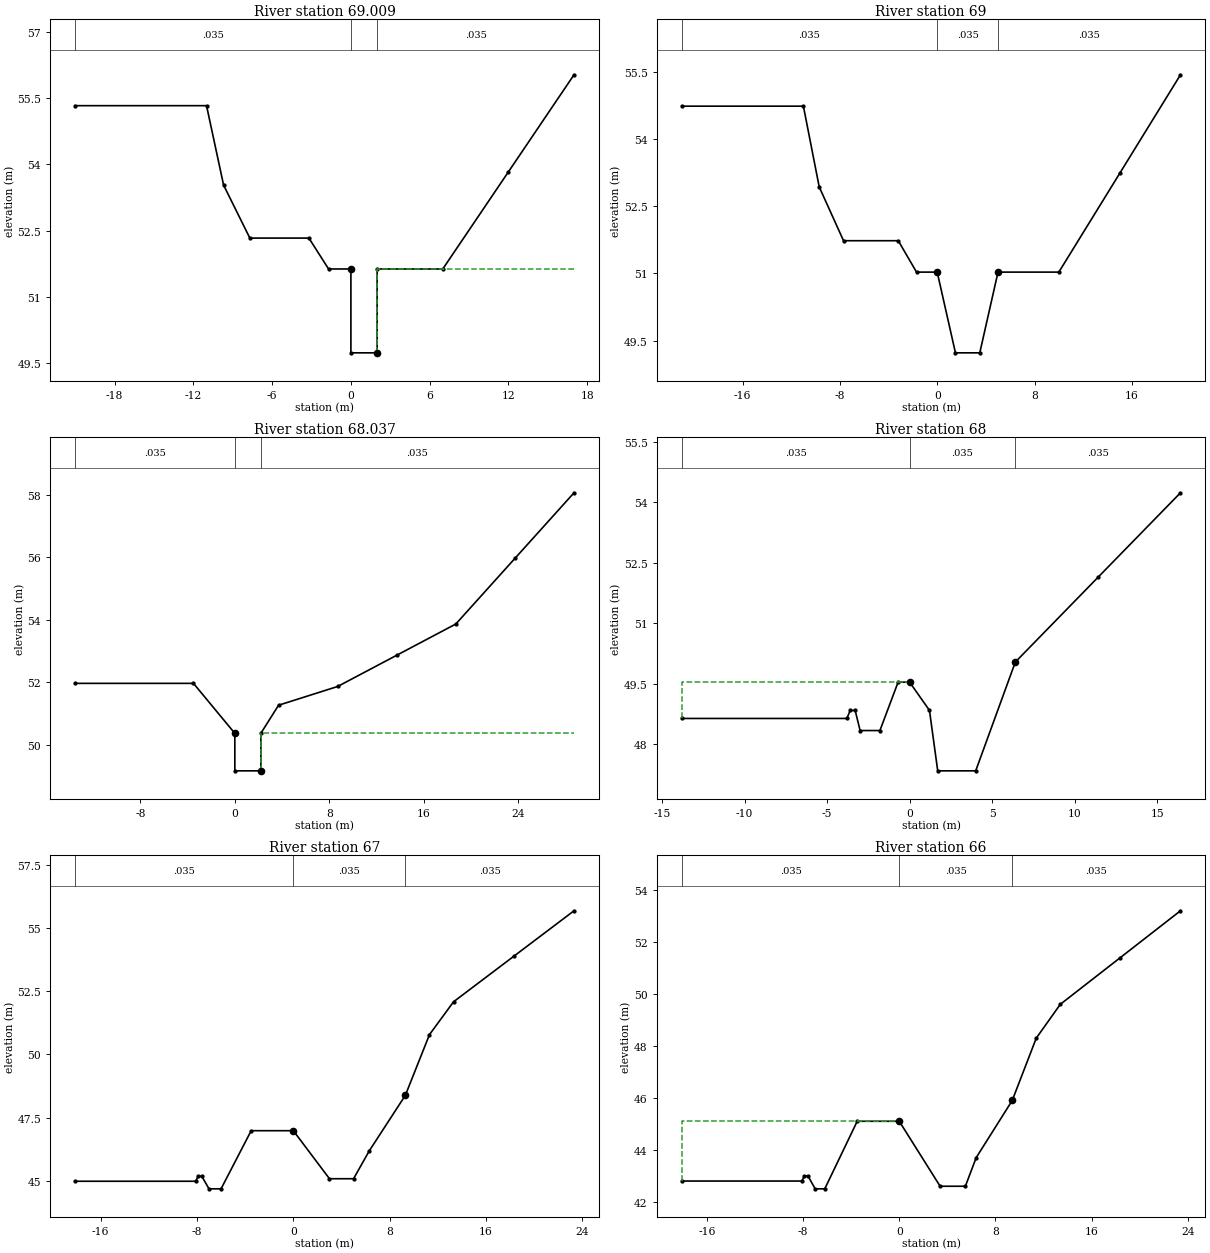
Type RM Length L Ch R = 1 ,69.009  ,9,9,9
#Sta/Elev= 13
     -21   55.33     -11   55.33    -9.7   53.53    -7.7   52.33    -3.2   52.33
    -1.7   51.63       0   51.63       0   49.73       2   49.73       2   51.63
       7   51.63      12   53.83      17   56.03
#Mann= 3 , 0 , 0
     -21    .035       0       0    .035       0       2    .035       0
#XS Ineff= 2 , 0
               0   51.63       2           51.63
Permanent Ineff=
       F       F
Bank Sta=0,2
XS Rating Curve= 0
Exp/Cntr=.3,.1

Type RM Length L Ch R = 1 ,69      ,13,13,13
#Sta/Elev= 13
     -21   54.73     -11   54.73    -9.7   52.93    -7.7   51.73    -3.2   51.73
    -1.7   51.03       0   51.03     1.5   49.23     3.5   49.23       5   51.03
      10   51.03      15   53.23      20   55.43
#Mann= 3 , 0 , 0
     -21    .035       0       0    .035       0       5    .035       0
#XS Ineff= 2 , 0
               0   51.03       5           51.03
Permanent Ineff=
       F       F
Bank Sta=0,5
XS Rating Curve= 0
Exp/Cntr=.3,.1

Type RM Length L Ch R = 1 ,68.037  ,37,37,37
#Sta/Elev= 12
   -13.5   51.97    -3.5   51.97       0   50.37       0   49.17     2.2   49.17
     2.2   50.37     3.7   51.27     8.7   51.87    13.7   52.87    18.7   53.87
    23.7   55.97    28.7   58.07
#Mann= 3 , 0 , 0
   -13.5    .035       0       0    .035       0     2.2    .035       0
#XS Ineff= 2 , 0
               0   50.37     2.2           50.37
Permanent Ineff=
       F       F
Bank Sta=0,2.2
XS Rating Curve= 0
Exp/Cntr=.3,.1

Type RM Length L Ch R = 1 ,68      ,50,50,50
#Sta/Elev= 14
   -13.8   48.64    -3.8   48.64    -3.6   48.84    -3.3   48.84      -3   48.34
    -1.8   48.34     -.7   49.54       0   49.54     1.2   48.84     1.7   47.34
       4   47.34     6.4   50.04    11.4   52.14    16.4   54.24
#Mann= 3 , 0 , 0
   -13.8    .035       0       0    .035       0     6.4    .035       0
#XS Ineff= 2 , 0
               0   49.54     6.4           50.04
Permanent Ineff=
       F       F
Bank Sta=0,6.4
XS Rating Curve= 0
Exp/Cntr=.3,.1

Type RM Length L Ch R = 1 ,67      ,50,50,50
#Sta/Elev= 16
   -18.1   44.98    -8.1   44.98    -7.9   45.18    -7.6   45.18      -7   44.68
      -6   44.68    -3.5   46.98       0   46.98       3   45.08       5   45.08
     6.3   46.18     9.3   48.38    11.3   50.78    13.3   52.08    18.3   53.88
    23.3   55.68
#Mann= 3 , 0 , 0
   -18.1    .035       0       0    .035       0     9.3    .035       0
#XS Ineff= 2 , 0
       0       0   46.98     9.3       0   48.38
Permanent Ineff=
       F       F
Bank Sta=0,9.3
XS Rating Curve= 0
Exp/Cntr=.3,.1

Type RM Length L Ch R = 1 ,66      ,50,50,50
#Sta/Elev= 16
   -18.1    42.8    -8.1    42.8    -7.9      43    -7.6      43      -7    42.5
    -6.2    42.5    -3.5    45.1       0    45.1     3.4    42.6     5.5    42.6
     6.4    43.7     9.4    45.9    11.4    48.3    13.4    49.6    18.4    51.4
    23.4    53.2
#Mann= 3 , 0 , 0
   -18.1    .035       0       0    .035       0     9.4    .035       0
#XS Ineff= 2 , 0
               0    45.1     9.4            45.9
Permanent Ineff=
       F       F
Bank Sta=0,9.4
XS Rating Curve= 0
Exp/Cntr=.3,.1

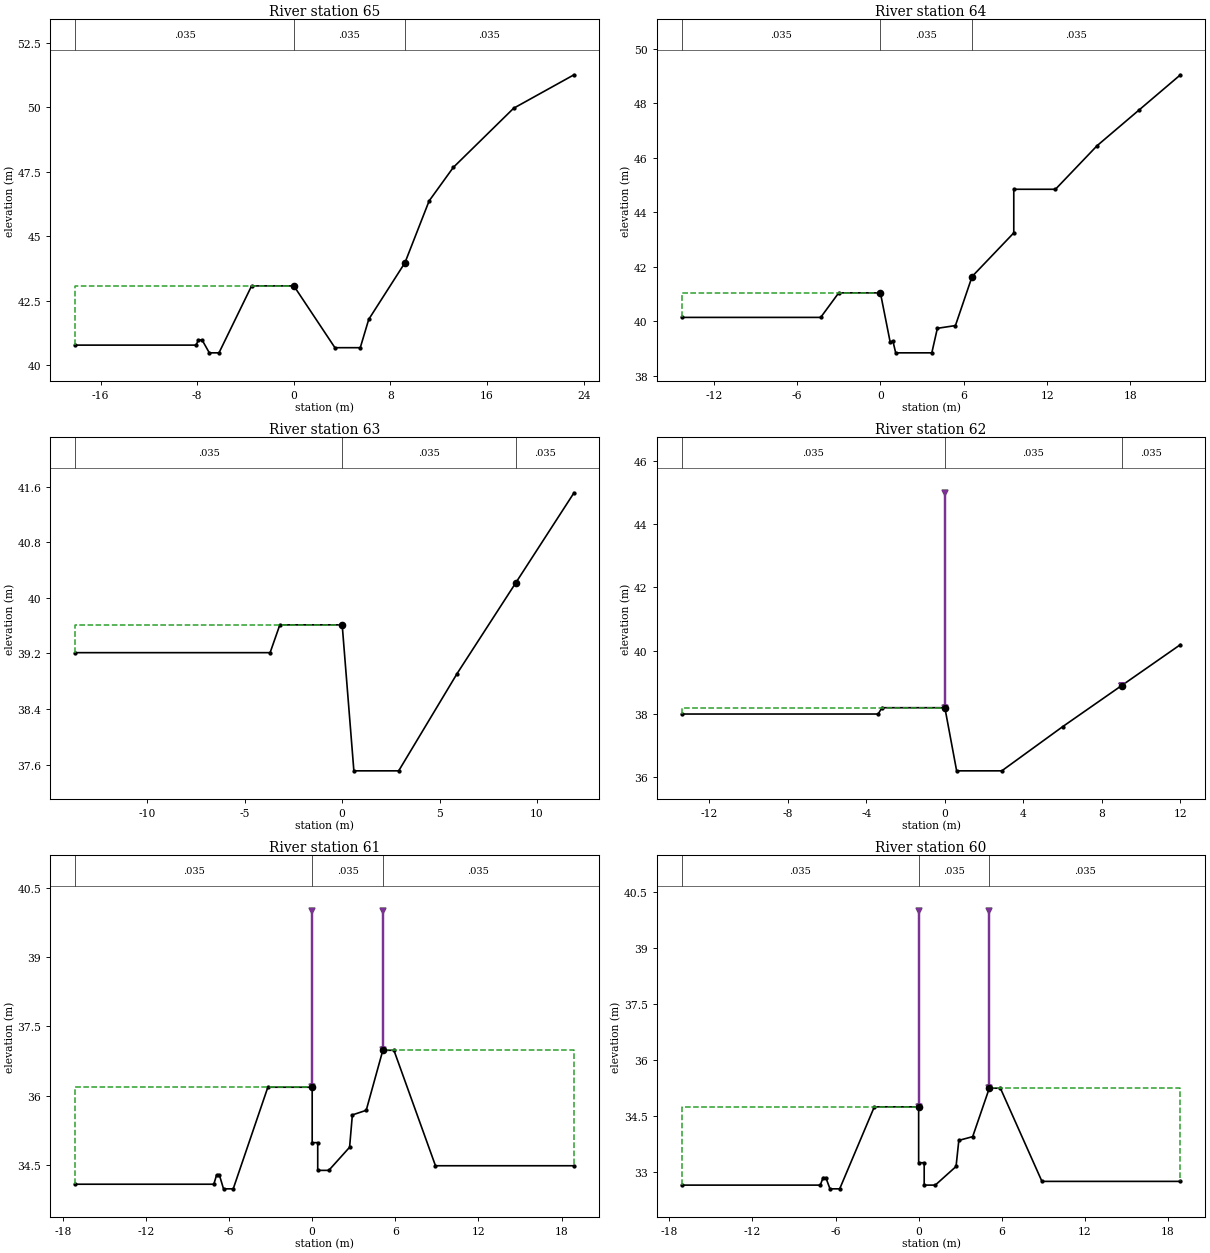
Type RM Length L Ch R = 1 ,65      ,50,50,50
#Sta/Elev= 16
   -18.1   40.77    -8.1   40.77    -7.9   40.97    -7.6   40.97      -7   40.47
    -6.2   40.47    -3.5   43.07       0   43.07     3.4   40.67     5.5   40.67
     6.2   41.77     9.2   43.97    11.2   46.37    13.2   47.67    18.2   49.97
    23.2   51.27
#Mann= 3 , 0 , 0
   -18.1    .035       0       0    .035       0     9.2    .035       0
#XS Ineff= 2 , 0
               0   43.07     9.2           43.97
Permanent Ineff=
       F       F
Bank Sta=0,9.2
XS Rating Curve= 0
Exp/Cntr=.3,.1

Type RM Length L Ch R = 1 ,64      ,50,50,50
#Sta/Elev= 17
   -14.3   40.14    -4.3   40.14      -3   41.04       0   41.04      .7   39.24
      .9   39.27     1.1   38.84     3.7   38.84     4.1   39.74     5.4   39.84
     6.6   41.64     9.6   43.24     9.6   44.84    12.6   44.84    15.6   46.44
    18.6   47.74    21.6   49.04
#Mann= 3 , 0 , 0
   -14.3    .035       0       0    .035       0     6.6    .035       0
#XS Ineff= 2 , 0
               0   41.04     6.6           41.64
Permanent Ineff=
       F       F
Bank Sta=0,6.6
XS Rating Curve= 0
Exp/Cntr=.3,.1

Type RM Length L Ch R = 1 ,63      ,50,50,50
#Sta/Elev= 9
   -13.7   39.21    -3.7   39.21    -3.2   39.61       0   39.61      .6   37.51
     2.9   37.51     5.9   38.91     8.9   40.21    11.9   41.51
#Mann= 3 , 0 , 0
   -13.7    .035       0       0    .035       0     8.9    .035       0
#XS Ineff= 2 , 0
               0   39.61     8.9           40.21
Permanent Ineff=
       F       F
Bank Sta=0,8.9
XS Rating Curve= 0
Exp/Cntr=.3,.1

Type RM Length L Ch R = 1 ,62      ,50,50,50
#Sta/Elev= 9
   -13.4   37.99    -3.4   37.99    -3.2   38.19       0   38.19      .6   36.19
     2.9   36.19       6   37.59       9   38.89      12   40.19
#Mann= 3 , 0 , 0
   -13.4    .035       0       0    .035       0       9    .035       0
Levee=-1,0,45,-1,9,38.89,,
#XS Ineff= 2 , 0
               0   38.19       9           38.89
Permanent Ineff=
       F       F
Bank Sta=0,9
XS Rating Curve= 0
Exp/Cntr=.3,.1

Type RM Length L Ch R = 1 ,61      ,50,50,50
#Sta/Elev= 19
   -17.1   34.08    -7.1   34.08    -6.9   34.28    -6.7   34.28    -6.4   33.98
    -5.7   33.98    -3.2   36.18       0   36.18       0   34.98      .4   34.98
      .4   34.38     1.2   34.38     2.7   34.88     2.9   35.58     3.9   35.68
     5.1   36.98     5.9   36.98     8.9   34.48    18.9   34.48
#Mann= 3 , 0 , 0
   -17.1    .035       0       0    .035       0     5.1    .035       0
Levee=-1,0,40,-1,5.1,40,,
#XS Ineff= 2 , 0
               0   36.18     5.1           36.98
Permanent Ineff=
       F       F
Bank Sta=0,5.1
XS Rating Curve= 0
Exp/Cntr=.3,.1

Type RM Length L Ch R = 1 ,60      ,50,50,50
#Sta/Elev= 19
   -17.1   32.64    -7.1   32.64    -6.9   32.84    -6.7   32.84    -6.4   32.54
    -5.7   32.54    -3.2   34.74       0   34.74       0   33.24      .4   33.24
      .4   32.64     1.2   32.64     2.7   33.14     2.9   33.84     3.9   33.94
     5.1   35.24     5.9   35.24     8.9   32.74    18.9   32.74
#Mann= 3 , 0 , 0
   -17.1    .035       0       0    .035       0     5.1    .035       0
Levee=-1,0,40,-1,5.1,40,,
#XS Ineff= 2 , 0
               0   34.74     5.1           35.24
Permanent Ineff=
       F       F
Bank Sta=0,5.1
XS Rating Curve= 0
Exp/Cntr=.3,.1

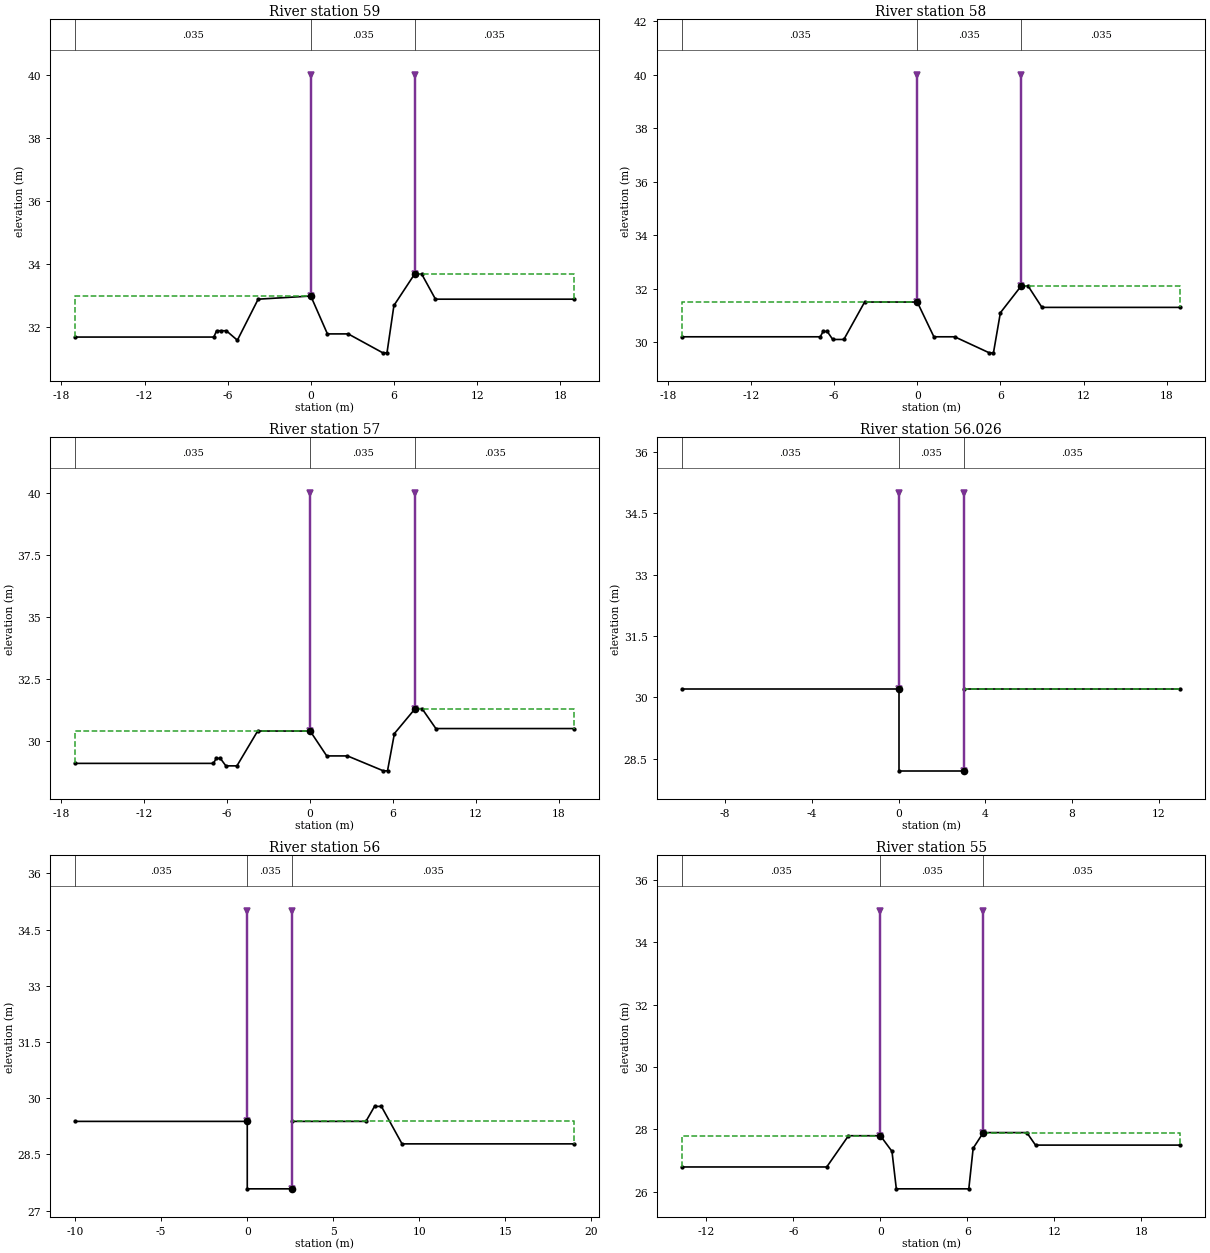
Type RM Length L Ch R = 1 ,59      ,50,50,50
#Sta/Elev= 17
     -17   31.69      -7   31.69    -6.8   31.89    -6.5   31.89    -6.1   31.89
    -5.3   31.59    -3.8   32.89       0   32.99     1.2   31.79     2.7   31.79
     5.2   31.19     5.5   31.19       6   32.69     7.5   33.69       8   33.69
       9   32.89      19   32.89
#Mann= 3 , 0 , 0
     -17    .035       0       0    .035       0     7.5    .035       0
Levee=-1,0,40,-1,7.5,40,,
#XS Ineff= 2 , 0
               0   32.99     7.5           33.69
Permanent Ineff=
       F       F
Bank Sta=0,7.5
XS Rating Curve= 0
Exp/Cntr=.3,.1

Type RM Length L Ch R = 1 ,58      ,50,50,50
#Sta/Elev= 17
     -17    30.2      -7    30.2    -6.8    30.4    -6.5    30.4    -6.1    30.1
    -5.3    30.1    -3.8    31.5       0    31.5     1.2    30.2     2.7    30.2
     5.2    29.6     5.5    29.6       6    31.1     7.5    32.1       8    32.1
       9    31.3      19    31.3
#Mann= 3 , 0 , 0
     -17    .035       0       0    .035       0     7.5    .035       0
Levee=-1,0,40,-1,7.5,40,,
#XS Ineff= 2 , 0
               0    31.5     7.5            32.1
Permanent Ineff=
       F       F
Bank Sta=0,7.5
XS Rating Curve= 0
Exp/Cntr=.3,.1

Type RM Length L Ch R = 1 ,57      ,24,24,24
#Sta/Elev= 17
     -17   29.12      -7   29.12    -6.8   29.32    -6.5   29.32    -6.1   29.02
    -5.3   29.02    -3.8   30.42       0   30.42     1.2   29.42     2.7   29.42
     5.3   28.82     5.6   28.82     6.1   30.32     7.6   31.32     8.1   31.32
     9.1   30.52    19.1   30.52
#Mann= 3 , 0 , 0
     -17    .035       0       0    .035       0     7.6    .035       0
Levee=-1,0,40,-1,7.6,40,,
#XS Ineff= 2 , 0
               0   30.42     7.6           31.32
Permanent Ineff=
       F       F
Bank Sta=0,7.6
XS Rating Curve= 0
Exp/Cntr=.3,.1

Type RM Length L Ch R = 1 ,56.026  ,26,26,26
#Sta/Elev= 6
     -10    30.2       0    30.2       0    28.2       3    28.2       3    30.2
      13    30.2
#Mann= 3 , 0 , 0
     -10    .035       0       0    .035       0       3    .035       0
Levee=-1,0,35,-1,3,35,,
#XS Ineff= 2 , 0
               0    30.2       3            30.2
Permanent Ineff=
       F       F
Bank Sta=0,3
XS Rating Curve= 0
Exp/Cntr=.3,.1

Type RM Length L Ch R = 1 ,56      ,50,50,50
#Sta/Elev= 10
     -10   29.38       0   29.38       0   27.58     2.6   27.58     2.6   29.38
     6.9   29.38     7.4   29.78     7.8   29.78       9   28.78      19   28.78
#Mann= 3 , 0 , 0
     -10    .035       0       0    .035       0     2.6    .035       0
Levee=-1,0,35,-1,2.6,35,,
#XS Ineff= 2 , 0
               0   29.38     2.6           29.38
Permanent Ineff=
       F       F
Bank Sta=0,2.6
XS Rating Curve= 0
Exp/Cntr=.3,.1

Type RM Length L Ch R = 1 ,55      ,34,34,34
#Sta/Elev= 12
   -13.7    26.8    -3.7    26.8    -2.2    27.8       0    27.8      .8    27.3
     1.1    26.1     6.1    26.1     6.4    27.4     7.1    27.9    10.1    27.9
    10.7    27.5    20.7    27.5
#Mann= 3 , 0 , 0
   -13.7    .035       0       0    .035       0     7.1    .035       0
Levee=-1,0,35,-1,7.1,35,,
#XS Ineff= 2 , 0
               0    27.8     7.1            27.9
Permanent Ineff=
       F       F
Bank Sta=0,7.1
XS Rating Curve= 0
Exp/Cntr=.3,.1

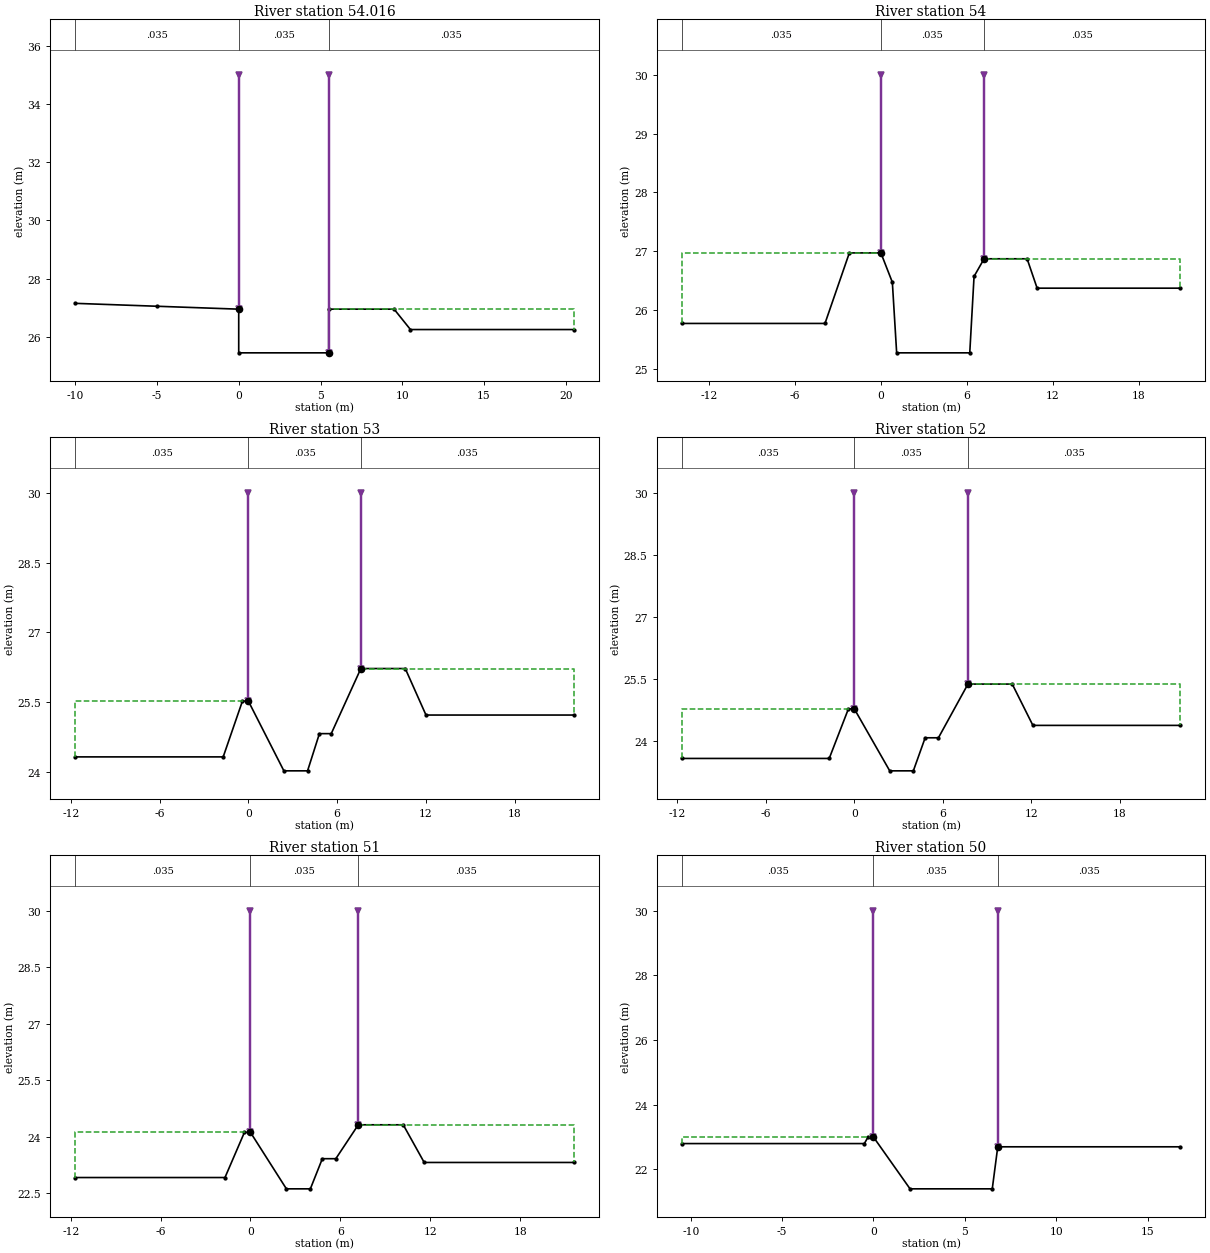
Type RM Length L Ch R = 1 ,54.016  ,16,16,16
#Sta/Elev= 9
     -10   27.15      -5   27.05       0   26.95       0   25.45     5.5   25.45
     5.5   26.95     9.5   26.95    10.5   26.25    20.5   26.25
#Mann= 3 , 0 , 0
     -10    .035       0       0    .035       0     5.5    .035       0
Levee=-1,0,35,-1,5.5,35,,
#XS Ineff= 2 , 0
               0   26.95     5.5           26.95
Permanent Ineff=
       F       F
Bank Sta=0,5.5
XS Rating Curve= 0
Exp/Cntr=.3,.1

Type RM Length L Ch R = 1 ,54      ,50,50,50
#Sta/Elev= 12
   -13.9   25.77    -3.9   25.77    -2.2   26.97       0   26.97      .8   26.47
     1.1   25.27     6.2   25.27     6.5   26.57     7.2   26.87    10.2   26.87
    10.9   26.37    20.9   26.37
#Mann= 3 , 0 , 0
   -13.9    .035       0       0    .035       0     7.2    .035       0
Levee=-1,0,30,-1,7.2,30,,
#XS Ineff= 2 , 0
               0   26.97     7.2           26.87
Permanent Ineff=
       F       F
Bank Sta=0,7.2
XS Rating Curve= 0
Exp/Cntr=.3,.1

Type RM Length L Ch R = 1 ,53      ,50,50,50
#Sta/Elev= 12
   -11.7   24.32    -1.7   24.32     -.4   25.52       0   25.52     2.4   24.02
       4   24.02     4.8   24.82     5.6   24.82     7.6   26.22    10.6   26.22
      12   25.22      22   25.22
#Mann= 3 , 0 , 0
   -11.7    .035       0       0    .035       0     7.6    .035       0
Levee=-1,0,30,-1,7.6,30,,
#XS Ineff= 2 , 0
               0   25.52     7.6           26.22
Permanent Ineff=
       F       F
Bank Sta=0,7.6
XS Rating Curve= 0
Exp/Cntr=.3,.1

Type RM Length L Ch R = 1 ,52      ,50,50,50
#Sta/Elev= 12
   -11.7   23.57    -1.7   23.57     -.4   24.77       0   24.77     2.4   23.27
       4   23.27     4.8   24.07     5.7   24.07     7.7   25.37    10.7   25.37
    12.1   24.37    22.1   24.37
#Mann= 3 , 0 , 0
   -11.7    .035       0       0    .035       0     7.7    .035       0
Levee=-1,0,30,-1,7.7,30,,
#XS Ineff= 2 , 0
               0   24.77     7.7           25.37
Permanent Ineff=
       F       F
Bank Sta=0,7.7
XS Rating Curve= 0
Exp/Cntr=.3,.1

Type RM Length L Ch R = 1 ,51      ,50,50,50
#Sta/Elev= 12
   -11.7   22.92    -1.7   22.92     -.4   24.12       0   24.12     2.4   22.62
       4   22.62     4.8   23.42     5.7   23.42     7.2   24.32    10.2   24.32
    11.6   23.32    21.6   23.32
#Mann= 3 , 0 , 0
   -11.7    .035       0       0    .035       0     7.2    .035       0
Levee=-1,0,30,-1,7.2,30,,
#XS Ineff= 2 , 0
               0   24.12     7.2           24.32
Permanent Ineff=
       F       F
Bank Sta=0,7.2
XS Rating Curve= 0
Exp/Cntr=.3,.1

Type RM Length L Ch R = 1 ,50      ,50,50,50
#Sta/Elev= 8
   -10.5    22.8     -.5    22.8     -.3      23       0      23       2    21.4
     6.5    21.4     6.8    22.7    16.8    22.7
#Mann= 3 , 0 , 0
   -10.5    .035       0       0    .035       0     6.8    .035       0
Levee=-1,0,30,-1,6.8,30,,
#XS Ineff= 2 , 0
               0      23     6.8            22.7
Permanent Ineff=
       F       F
Bank Sta=0,6.8
XS Rating Curve= 0
Exp/Cntr=.3,.1

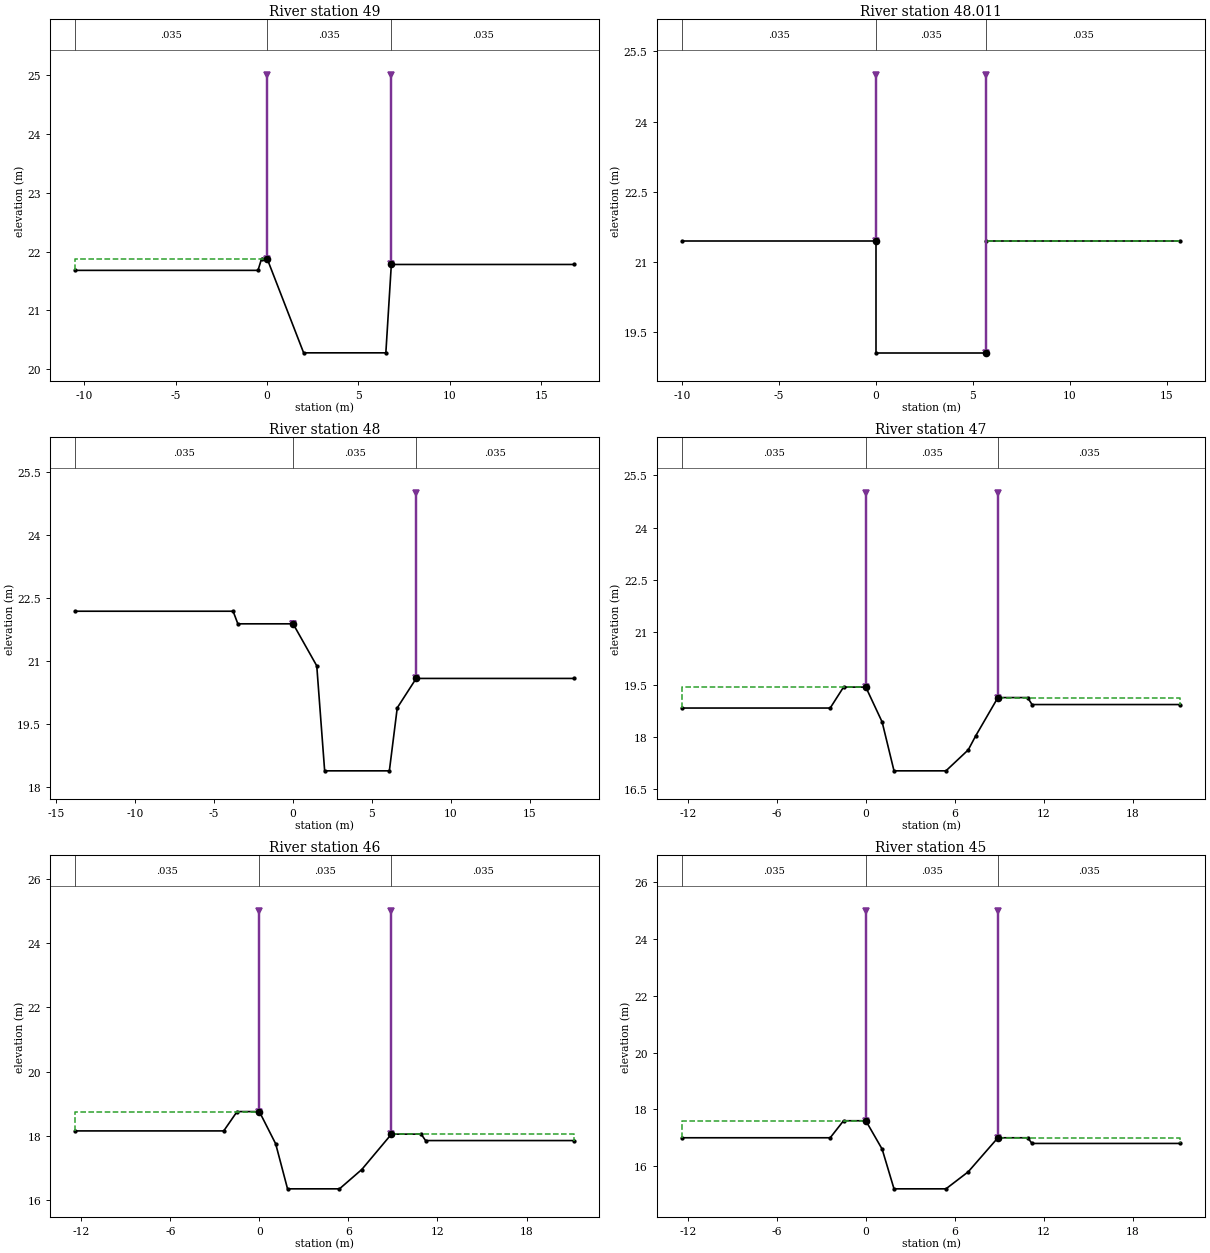
Type RM Length L Ch R = 1 ,49      ,39,39,39
#Sta/Elev= 8
   -10.5   21.68     -.5   21.68     -.3   21.88       0   21.88       2   20.28
     6.5   20.28     6.8   21.78    16.8   21.78
#Mann= 3 , 0 , 0
   -10.5    .035       0       0    .035       0     6.8    .035       0
Levee=-1,0,25,-1,6.8,25,,
#XS Ineff= 2 , 0
               0   21.88     6.8           21.78
Permanent Ineff=
       F       F
Bank Sta=0,6.8
XS Rating Curve= 0
Exp/Cntr=.3,.1

Type RM Length L Ch R = 1 ,48.011  ,11,11,11
#Sta/Elev= 6
     -10   21.45       0   21.45       0   19.05     5.7   19.05     5.7   21.45
    15.7   21.45
#Mann= 3 , 0 , 0
     -10    .035       0       0    .035       0     5.7    .035       0
Levee=-1,0,25,-1,5.7,25,,
#XS Ineff= 2 , 0
               0   21.45     5.7           21.45
Permanent Ineff=
       F       F
Bank Sta=0,5.7
XS Rating Curve= 0
Exp/Cntr=.3,.1

Type RM Length L Ch R = 1 ,48      ,50,50,50
#Sta/Elev= 10
   -13.8   22.18    -3.8   22.18    -3.5   21.88       0   21.88     1.5   20.88
       2   18.38     6.1   18.38     6.6   19.88     7.8   20.58    17.8   20.58
#Mann= 3 , 0 , 0
   -13.8    .035       0       0    .035       0     7.8    .035       0
Levee=-1,0,21.88,-1,7.8,25,,
#XS Ineff= 2 , 0
               0   21.88     7.8           20.58
Permanent Ineff=
       F       F
Bank Sta=0,7.8
XS Rating Curve= 0
Exp/Cntr=.3,.1

Type RM Length L Ch R = 1 ,47      ,50,50,50
#Sta/Elev= 13
   -12.4   18.83    -2.4   18.83    -1.5   19.43       0   19.43     1.1   18.43
     1.9   17.03     5.4   17.03     6.9   17.63     7.4   18.03     8.9   19.13
    10.9   19.13    11.2   18.93    21.2   18.93
#Mann= 3 , 0 , 0
   -12.4    .035       0       0    .035       0     8.9    .035       0
Levee=-1,0,25,-1,8.9,25,,
#XS Ineff= 2 , 0
               0   19.43     8.9           19.13
Permanent Ineff=
       F       F
Bank Sta=0,8.9
XS Rating Curve= 0
Exp/Cntr=.3,.1

Type RM Length L Ch R = 1 ,46      ,50,50,50
#Sta/Elev= 12
   -12.4   18.16    -2.4   18.16    -1.5   18.76       0   18.76     1.1   17.76
     1.9   16.36     5.4   16.36     6.9   16.96     8.9   18.06    10.9   18.06
    11.2   17.86    21.2   17.86
#Mann= 3 , 0 , 0
   -12.4    .035       0       0    .035       0     8.9    .035       0
Levee=-1,0,25,-1,8.9,25,,
#XS Ineff= 2 , 0
               0   18.76     8.9           18.06
Permanent Ineff=
       F       F
Bank Sta=0,8.9
XS Rating Curve= 0
Exp/Cntr=.3,.1

Type RM Length L Ch R = 1 ,45      ,50,50,50
#Sta/Elev= 12
   -12.4      17    -2.4      17    -1.5    17.6       0    17.6     1.1    16.6
     1.9    15.2     5.4    15.2     6.9    15.8     8.9      17    10.9      17
    11.2    16.8    21.2    16.8
#Mann= 3 , 0 , 0
   -12.4    .035       0       0    .035       0     8.9    .035       0
Levee=-1,0,25,-1,8.9,25,,
#XS Ineff= 2 , 0
               0    17.6     8.9              17
Permanent Ineff=
       F       F
Bank Sta=0,8.9
XS Rating Curve= 0
Exp/Cntr=.3,.1

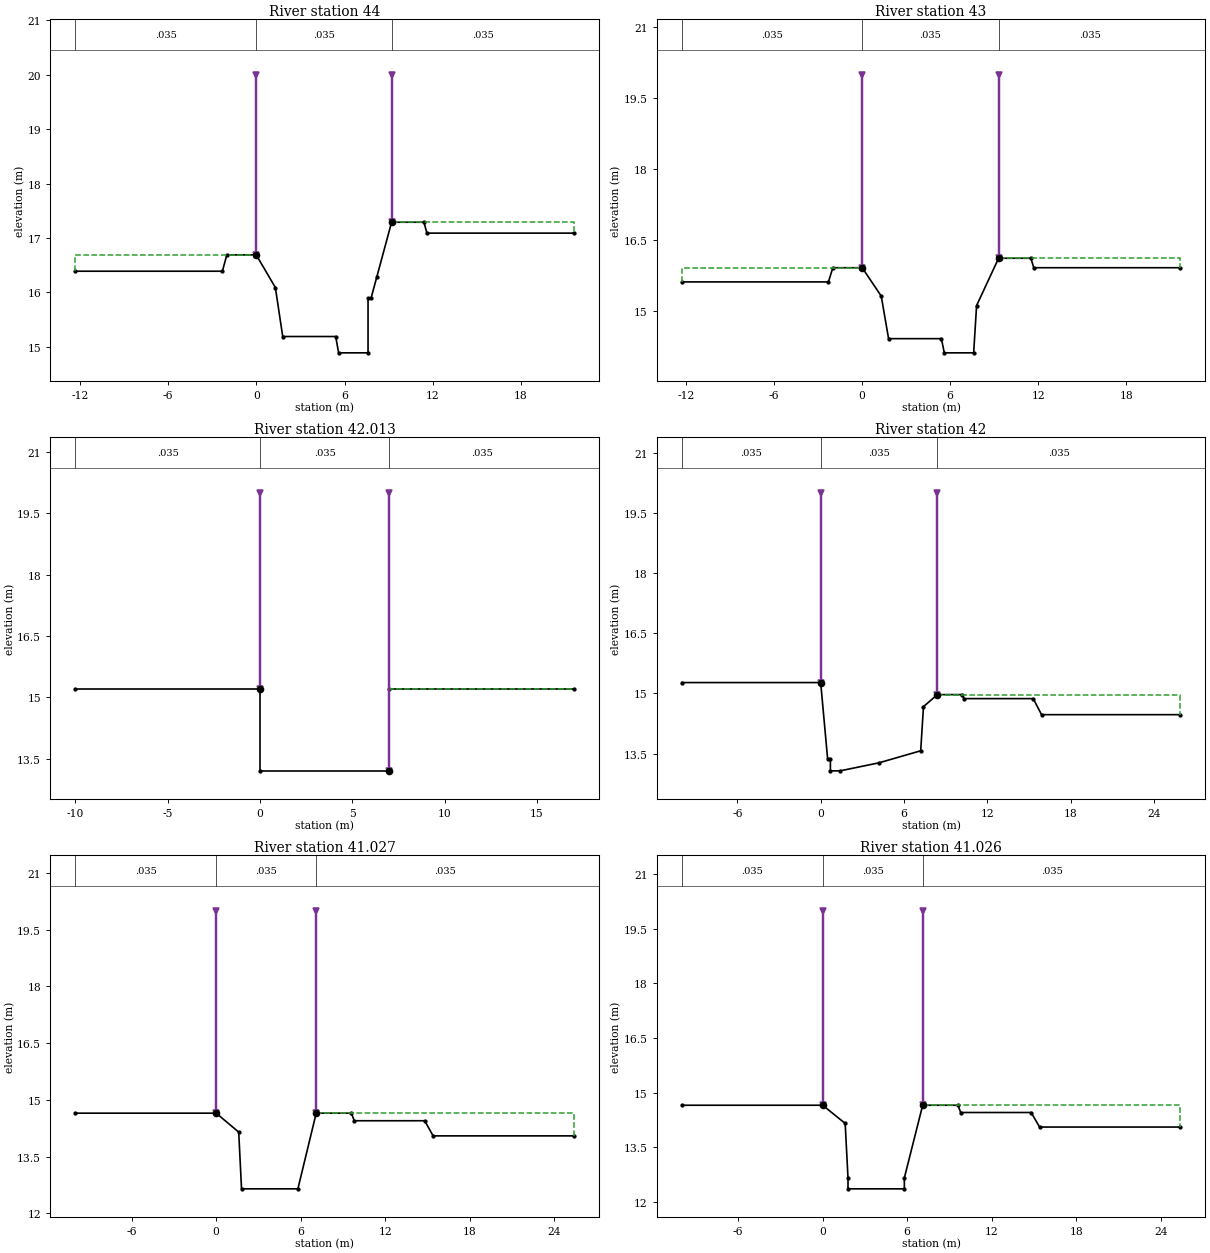
Type RM Length L Ch R = 1 ,44      ,50,50,50
#Sta/Elev= 16
   -12.3   16.39    -2.3   16.39      -2   16.69       0   16.69     1.3   16.09
     1.8   15.19     5.4   15.19     5.6   14.89     7.6   14.89     7.6   15.89
     7.8   15.89     8.2   16.29     9.2   17.29    11.4   17.29    11.6   17.09
    21.6   17.09
#Mann= 3 , 0 , 0
   -12.3    .035       0       0    .035       0     9.2    .035       0
Levee=-1,0,20,-1,9.2,20,,
#XS Ineff= 2 , 0
               0   16.69     9.2           17.29
Permanent Ineff=
       F       F
Bank Sta=0,9.2
XS Rating Curve= 0
Exp/Cntr=.3,.1

Type RM Length L Ch R = 1 ,43      ,37,37,37
#Sta/Elev= 14
   -12.3   15.62    -2.3   15.62      -2   15.92       0   15.92     1.3   15.32
     1.8   14.42     5.4   14.42     5.6   14.12     7.6   14.12     7.8   15.12
     9.3   16.12    11.5   16.12    11.7   15.92    21.7   15.92
#Mann= 3 , 0 , 0
   -12.3    .035       0       0    .035       0     9.3    .035       0
Levee=-1,0,20,-1,9.3,20,,
#XS Ineff= 2 , 0
               0   15.92     9.3           16.12
Permanent Ineff=
       F       F
Bank Sta=0,9.3
XS Rating Curve= 0
Exp/Cntr=.3,.1

Type RM Length L Ch R = 1 ,42.013  ,13,13,13
#Sta/Elev= 6
     -10    15.2       0    15.2       0    13.2       7    13.2       7    15.2
      17    15.2
#Mann= 3 , 0 , 0
     -10    .035       0       0    .035       0       7    .035       0
Levee=-1,0,20,-1,7,20,,
#XS Ineff= 2 , 0
               0    15.2       7            15.2
Permanent Ineff=
       F       F
Bank Sta=0,7
XS Rating Curve= 0
Exp/Cntr=.3,.1

Type RM Length L Ch R = 1 ,42      ,23,23,23
#Sta/Elev= 15
     -10   15.27       0   15.27      .5   13.37      .7   13.37      .7   13.07
     1.4   13.07     4.2   13.27     7.2   13.57     7.4   14.67     8.4   14.97
    10.2   14.97    10.3   14.87    15.3   14.87    15.9   14.47    25.9   14.47
#Mann= 3 , 0 , 0
     -10    .035       0       0    .035       0     8.4    .035       0
Levee=-1,0,20,-1,8.4,20,,
#XS Ineff= 2 , 0
               0   15.27     8.4           14.97
Permanent Ineff=
       F       F
Bank Sta=0,8.4
XS Rating Curve= 0
Exp/Cntr=.3,.1

Type RM Length L Ch R = 1 ,41.027  ,1,1,1
#Sta/Elev= 11
     -10   14.65       0   14.65     1.6   14.15     1.8   12.65     5.8   12.65
     7.1   14.65     9.6   14.65     9.8   14.45    14.8   14.45    15.4   14.05
    25.4   14.05
#Mann= 3 , 0 , 0
     -10    .035       0       0    .035       0     7.1    .035       0
Levee=-1,0,20,-1,7.1,20,,
#XS Ineff= 2 , 0
               0   14.65     7.1           14.65
Permanent Ineff=
       F       F
Bank Sta=0,7.1
XS Rating Curve= 0
Exp/Cntr=.3,.1

Type RM Length L Ch R = 1 ,41.026  ,26,26,26
#Sta/Elev= 13
     -10   14.65       0   14.65     1.6   14.15     1.8   12.65     1.8   12.35
     5.8   12.35     5.8   12.65     7.1   14.65     9.6   14.65     9.8   14.45
    14.8   14.45    15.4   14.05    25.4   14.05
#Mann= 3 , 0 , 0
     -10    .035       0       0    .035       0     7.1    .035       0
Levee=-1,0,20,-1,7.1,20,,
#XS Ineff= 2 , 0
               0   14.65     7.1           14.65
Permanent Ineff=
       F       F
Bank Sta=0,7.1
XS Rating Curve= 0
Exp/Cntr=.3,.1

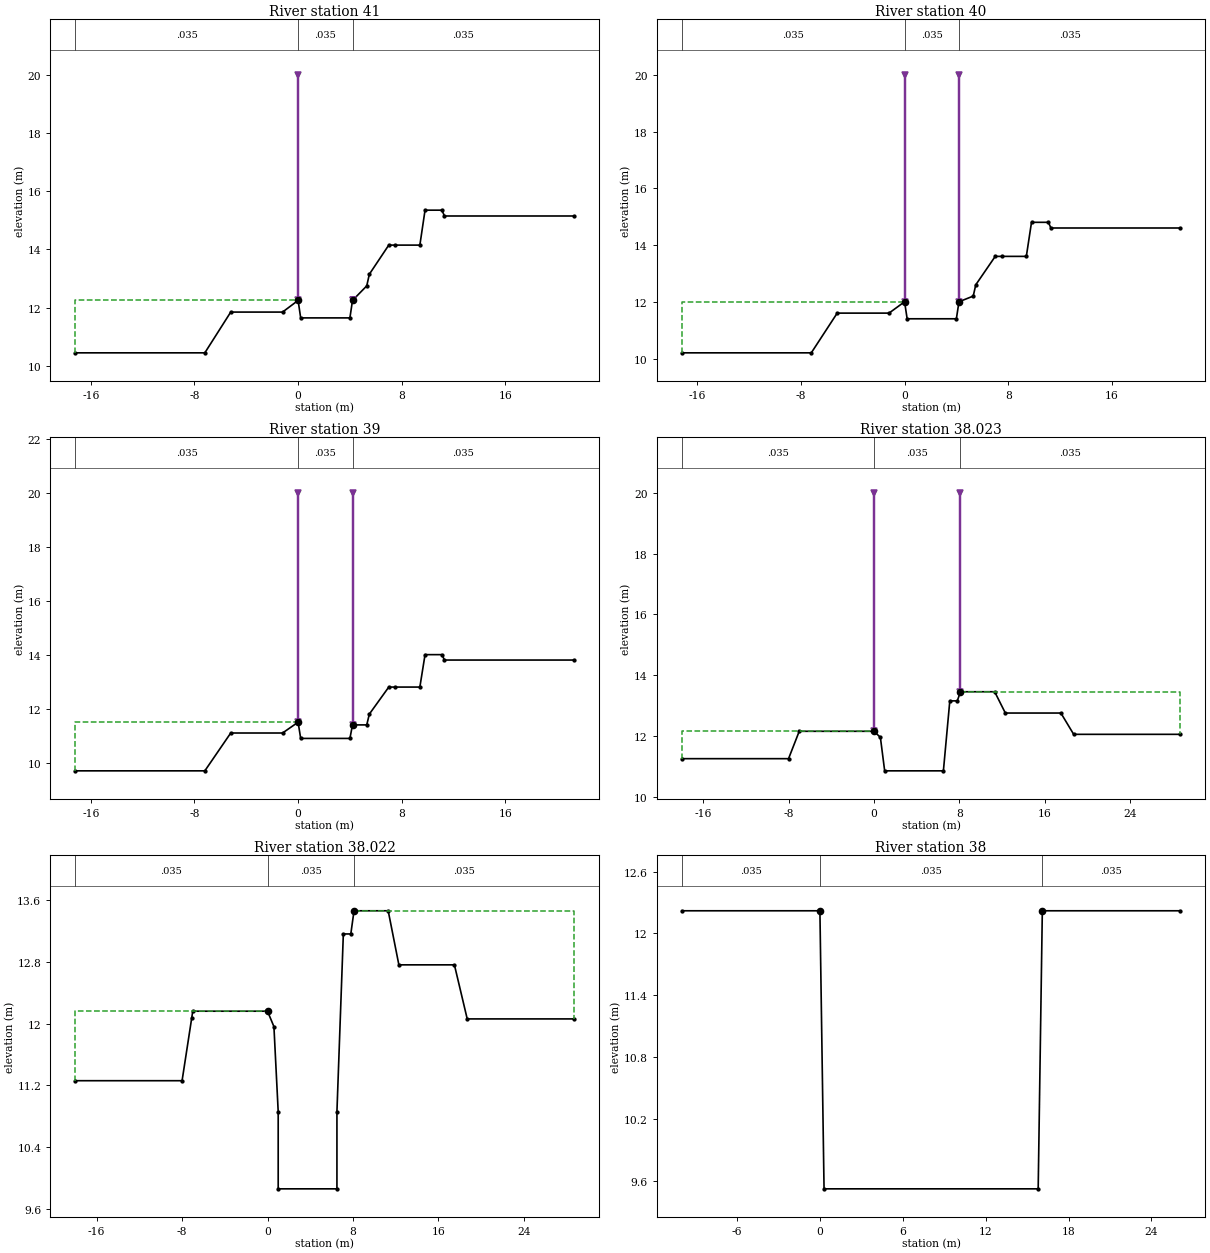
Type RM Length L Ch R = 1 ,41      ,50,50,50
#Sta/Elev= 17
   -17.2   10.45    -7.2   10.45    -5.2   11.85    -1.2   11.85       0   12.25
      .2   11.65       4   11.65     4.2   12.25     5.3   12.75     5.5   13.15
       7   14.15     7.5   14.15     9.4   14.15     9.8   15.35    11.1   15.35
    11.3   15.15    21.3   15.15
#Mann= 3 , 0 , 0
   -17.2    .035       0       0    .035       0     4.2    .035       0
Levee=-1,0,20,-1,4.2,12.25,,
#XS Ineff= 2 , 0
               0   12.25     4.2           12.25
Permanent Ineff=
       F       F
Bank Sta=0,4.2
XS Rating Curve= 0
Exp/Cntr=.3,.1

Type RM Length L Ch R = 1 ,40      ,50,50,50
#Sta/Elev= 17
   -17.2    10.2    -7.2    10.2    -5.2    11.6    -1.2    11.6       0      12
      .2    11.4       4    11.4     4.2      12     5.3    12.2     5.5    12.6
       7    13.6     7.5    13.6     9.4    13.6     9.8    14.8    11.1    14.8
    11.3    14.6    21.3    14.6
#Mann= 3 , 0 , 0
   -17.2    .035       0       0    .035       0     4.2    .035       0
Levee=-1,0,20,-1,4.2,20,,
#XS Ineff= 2 , 0
               0      12     4.2              12
Permanent Ineff=
       F       F
Bank Sta=0,4.2
XS Rating Curve= 0
Exp/Cntr=.3,.1

Type RM Length L Ch R = 1 ,39      ,27,27,27
#Sta/Elev= 17
   -17.2    9.71    -7.2    9.71    -5.2   11.11    -1.2   11.11       0   11.51
      .2   10.91       4   10.91     4.2   11.41     5.3   11.41     5.5   11.81
       7   12.81     7.5   12.81     9.4   12.81     9.8   14.01    11.1   14.01
    11.3   13.81    21.3   13.81
#Mann= 3 , 0 , 0
   -17.2    .035       0       0    .035       0     4.2    .035       0
Levee=-1,0,20,-1,4.2,20,,
#XS Ineff= 2 , 0
               0   11.51     4.2           11.41
Permanent Ineff=
       F       F
Bank Sta=0,4.2
XS Rating Curve= 0
Exp/Cntr=.3,.1

Type RM Length L Ch R = 1 ,38.023  ,1,1,1
#Sta/Elev= 15
     -18   11.26      -8   11.26      -7   12.16       0   12.16      .6   11.96
       1   10.86     6.5   10.86     7.1   13.16     7.8   13.16     8.1   13.46
    11.3   13.46    12.3   12.76    17.5   12.76    18.7   12.06    28.7   12.06
#Mann= 3 , 0 , 0
     -18    .035       0       0    .035       0     8.1    .035       0
Levee=-1,0,20,-1,8.1,20,,
#XS Ineff= 2 , 0
               0   12.16     8.1           13.46
Permanent Ineff=
       F       F
Bank Sta=0,8.1
XS Rating Curve= 0
Exp/Cntr=.3,.1

Type RM Length L Ch R = 1 ,38.022  ,22,22,22
#Sta/Elev= 18
     -18   11.26      -8   11.26    -7.1   12.07      -7   12.16       0   12.16
      .6   11.96       1   10.86       1    9.86     6.5    9.86     6.5   10.86
     7.1   13.16     7.8   13.16     8.1   13.46    11.3   13.46    12.3   12.76
    17.5   12.76    18.7   12.06    28.7   12.06
#Mann= 3 , 0 , 0
     -18    .035       0       0    .035       0     8.1    .035       0
#XS Ineff= 2 , 0
               0   12.16     8.1           13.46
Permanent Ineff=
       F       F
Bank Sta=0,8.1
XS Rating Curve= 0
Exp/Cntr=.3,.1

Type RM Length L Ch R = 1 ,38      ,50,50,50
#Sta/Elev= 6
     -10   12.22       0   12.22      .3    9.52    15.8    9.52    16.1   12.22
    26.1   12.22
#Mann= 3 , 0 , 0
     -10    .035       0       0    .035       0    16.1    .035       0
#XS Ineff= 2 , 0
               0   12.22    16.1           12.22
Permanent Ineff=
       F       F
Bank Sta=0,16.1
XS Rating Curve= 0
Exp/Cntr=.3,.1