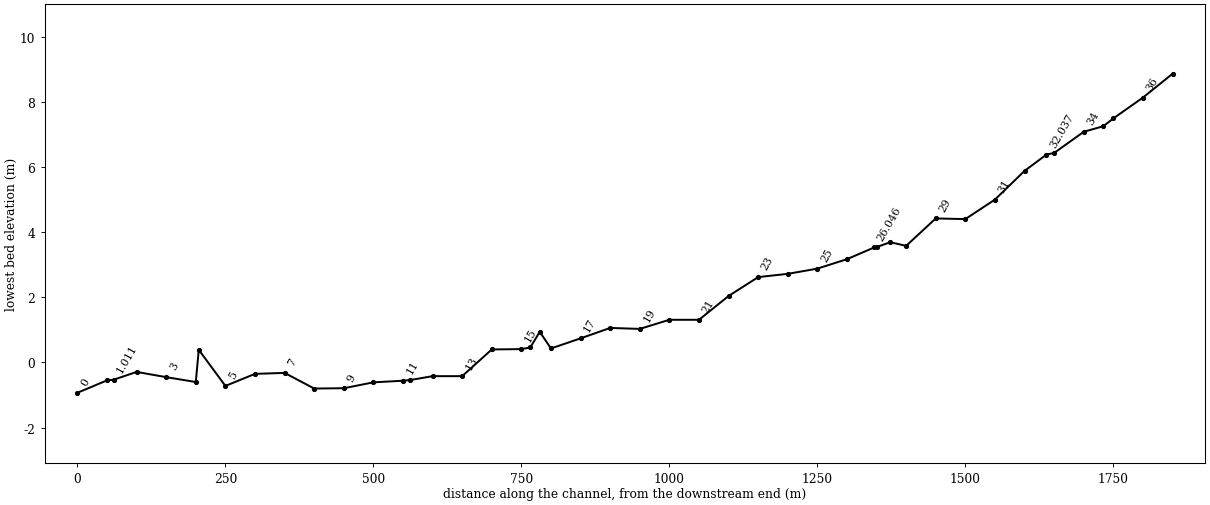
HEC-RAS study SHC.prj: songhak-ch

--- SHC.g01 (geometry) --- (continued)

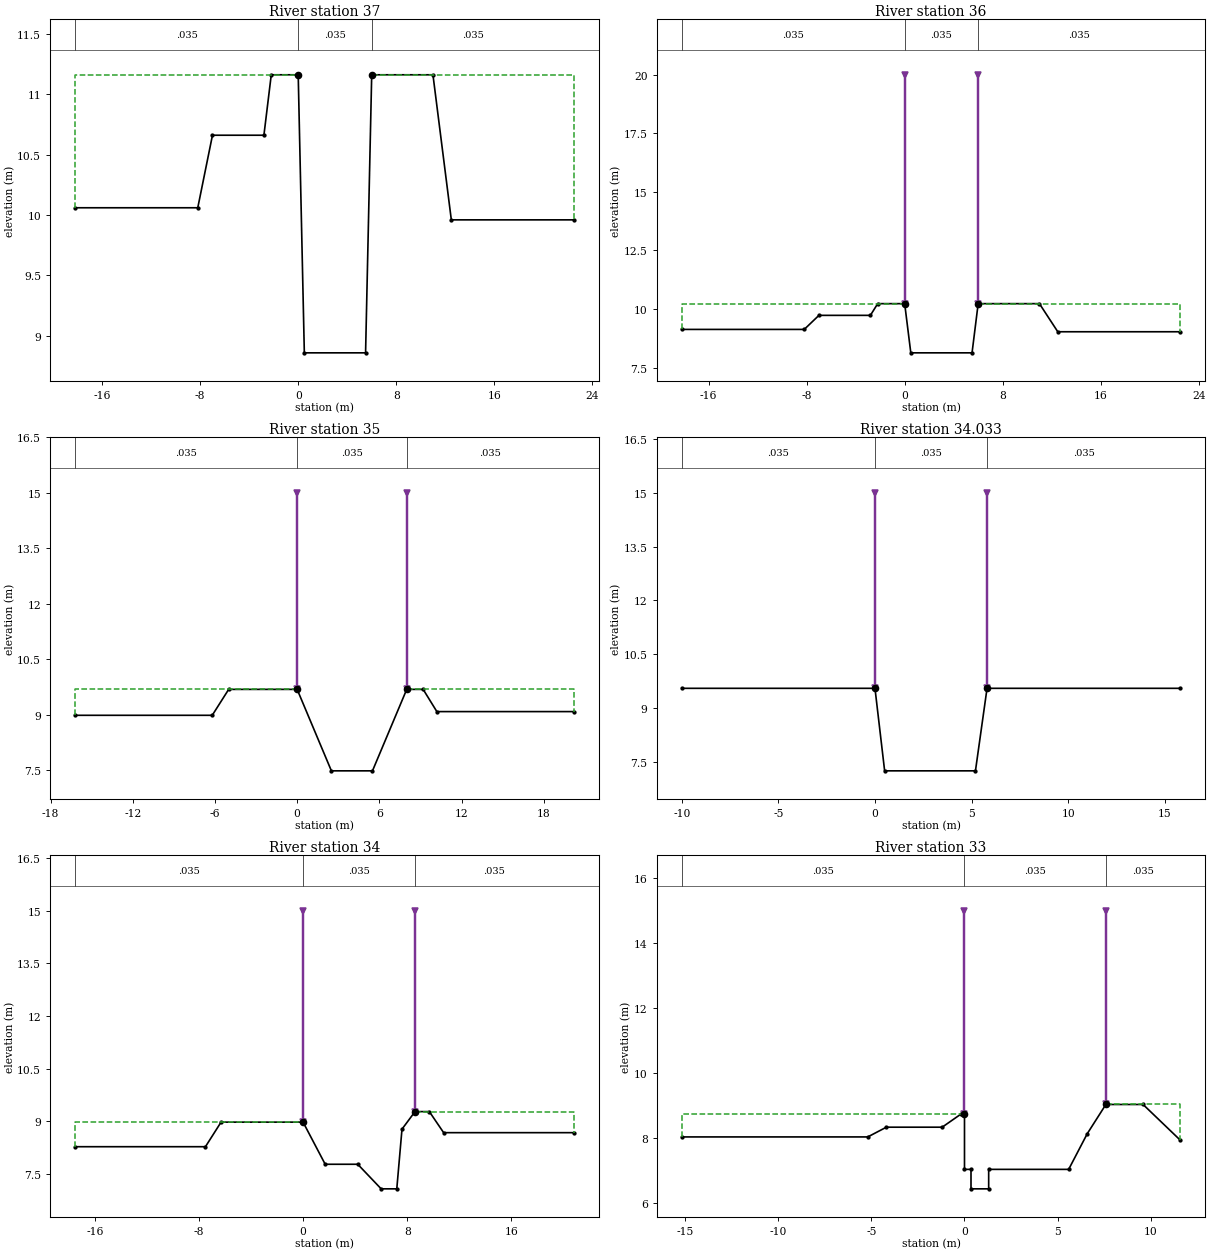
Type RM Length L Ch R = 1 ,37      ,50,50,50
#Sta/Elev= 12
   -18.2   10.06    -8.2   10.06      -7   10.66    -2.8   10.66    -2.2   11.16
       0   11.16      .5    8.86     5.5    8.86       6   11.16      11   11.16
    12.5    9.96    22.5    9.96
#Mann= 3 , 0 , 0
   -18.2    .035       0       0    .035       0       6    .035       0
#XS Ineff= 2 , 0
               0   11.16       6           11.16
Permanent Ineff=
       F       F
Bank Sta=0,6
XS Rating Curve= 0
Exp/Cntr=.3,.1

Type RM Length L Ch R = 1 ,36      ,50,50,50
#Sta/Elev= 12
   -18.2    9.13    -8.2    9.13      -7    9.73    -2.8    9.73    -2.2   10.23
       0   10.23      .5    8.13     5.5    8.13       6   10.23      11   10.23
    12.5    9.03    22.5    9.03
#Mann= 3 , 0 , 0
   -18.2    .035       0       0    .035       0       6    .035       0
Levee=-1,0,20,-1,6,20,,
#XS Ineff= 2 , 0
               0   10.23       6           10.23
Permanent Ineff=
       F       F
Bank Sta=0,6
XS Rating Curve= 0
Exp/Cntr=.3,.1

Type RM Length L Ch R = 1 ,35      ,17,17,17
#Sta/Elev= 10
   -16.2    8.99    -6.2    8.99      -5    9.69       0    9.69     2.5    7.49
     5.5    7.49       8    9.69     9.2    9.69    10.2    9.09    20.2    9.09
#Mann= 3 , 0 , 0
   -16.2    .035       0       0    .035       0       8    .035       0
Levee=-1,0,15,-1,8,15,,
#XS Ineff= 2 , 0
               0    9.69       8            9.69
Permanent Ineff=
       F       F
Bank Sta=0,8
XS Rating Curve= 0
Exp/Cntr=.3,.1

Type RM Length L Ch R = 1 ,34.033  ,33,33,33
#Sta/Elev= 6
     -10    9.55       0    9.55      .5    7.25     5.2    7.25     5.8    9.55
    15.8    9.55
#Mann= 3 , 0 , 0
     -10    .035       0       0    .035       0     5.8    .035       0
Levee=-1,0,15,-1,5.8,15,,
#XS Ineff= 2 , 0
               0    9.55     5.8            9.55
Permanent Ineff=
       F       F
Bank Sta=0,5.8
XS Rating Curve= 0
Exp/Cntr=.3,.1

Type RM Length L Ch R = 1 ,34      ,50,50,50
#Sta/Elev= 13
   -17.5    8.28    -7.5    8.28    -6.3    8.98       0    8.98     1.7    7.78
     4.2    7.78       6    7.08     7.2    7.08     7.6    8.78     8.6    9.28
     9.7    9.28    10.8    8.68    20.8    8.68
#Mann= 3 , 0 , 0
   -17.5    .035       0       0    .035       0     8.6    .035       0
Levee=-1,0,15,-1,8.6,15,,
#XS Ineff= 2 , 0
               0    8.98     8.6            9.28
Permanent Ineff=
       F       F
Bank Sta=0,8.6
XS Rating Curve= 0
Exp/Cntr=.3,.1

Type RM Length L Ch R = 1 ,33      ,13,13,13
#Sta/Elev= 16
   -15.2    8.03    -5.2    8.03    -4.2    8.33    -1.2    8.33     -.2    8.73
       0    8.73       0    7.03     .35    7.03     .35    6.43     1.3    6.43
     1.3    7.03     5.6    7.03     6.6    8.13     7.6    9.03     9.6    9.03
    11.6    7.93
#Mann= 3 , 0 , 0
   -15.2    .035       0       0    .035       0     7.6    .035       0
Levee=-1,0,15,-1,7.6,15,,
#XS Ineff= 2 , 0
               0    8.73     7.6            9.03
Permanent Ineff=
       F       F
Bank Sta=0,7.6
XS Rating Curve= 0
Exp/Cntr=.3,.1

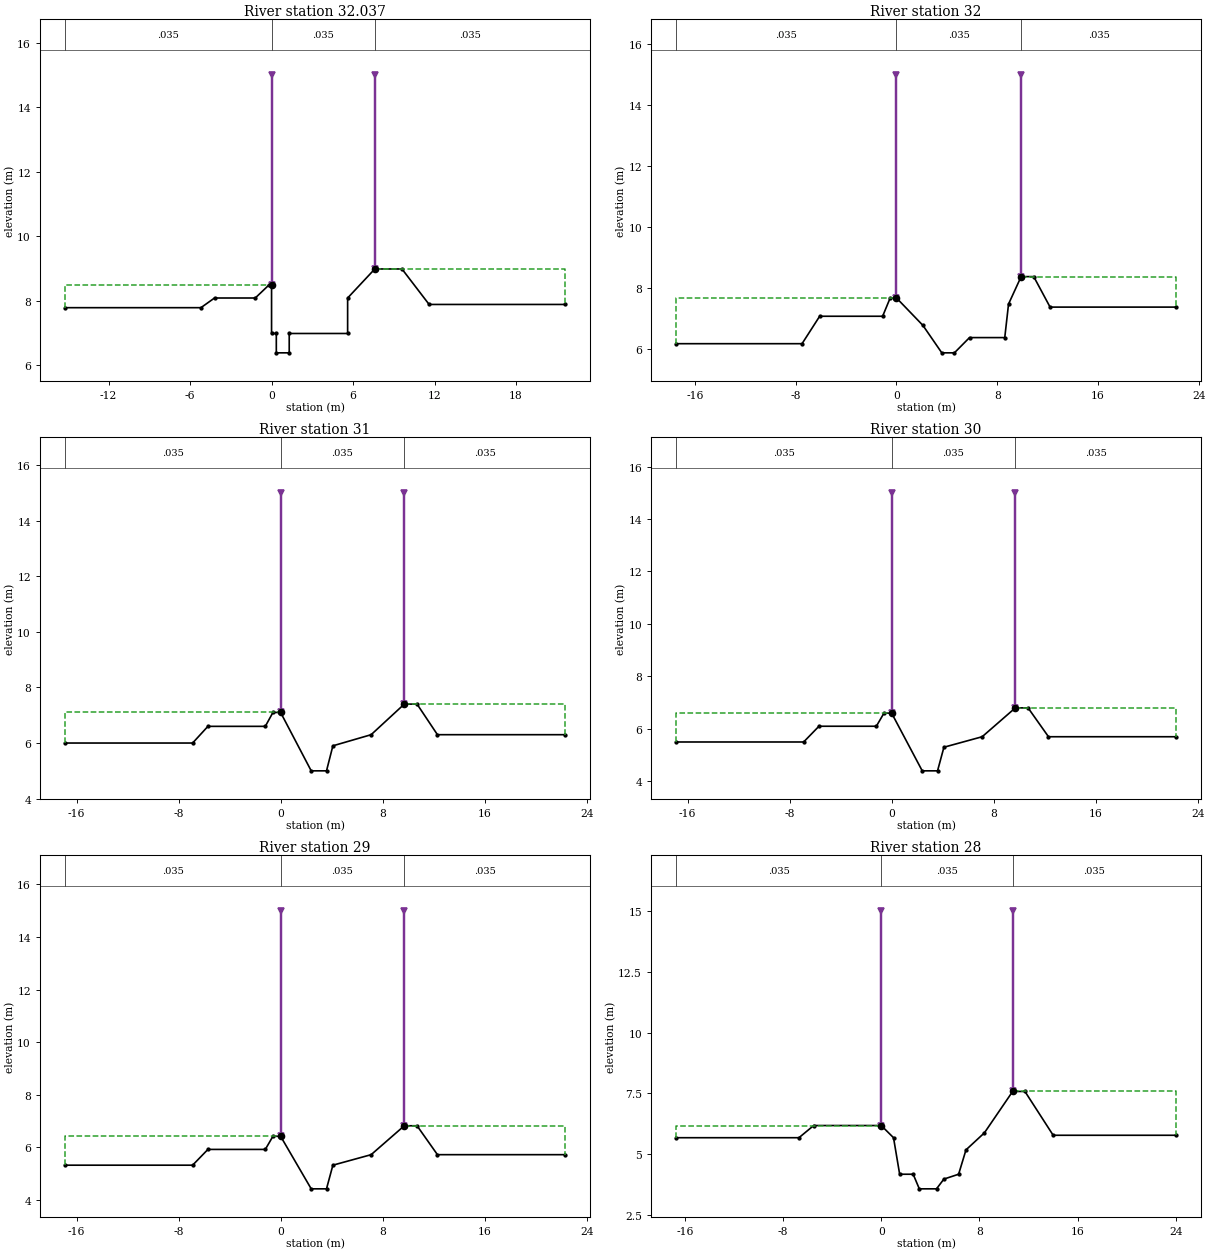
Type RM Length L Ch R = 1 ,32.037  ,37,37,37
#Sta/Elev= 17
   -15.2    7.78    -5.2    7.78    -4.2    8.08    -1.2    8.08     -.2    8.48
       0    8.48       0    6.98     .35    6.98     .35    6.38     1.3    6.38
     1.3    6.98     5.6    6.98     5.6    8.08     7.6    8.98     9.6    8.98
    11.6    7.88    21.6    7.88
#Mann= 3 , 0 , 0
   -15.2    .035       0       0    .035       0     7.6    .035       0
Levee=-1,0,15,-1,7.6,15,,
#XS Ineff= 2 , 0
               0    8.48     7.6            8.98
Permanent Ineff=
       F       F
Bank Sta=0,7.6
XS Rating Curve= 0
Exp/Cntr=.3,.1

Type RM Length L Ch R = 1 ,32      ,50,50,50
#Sta/Elev= 16
   -17.5    6.18    -7.5    6.18    -6.1    7.08    -1.1    7.08     -.5    7.68
       0    7.68     2.1    6.78     3.6    5.88     4.6    5.88     5.8    6.38
     8.6    6.38     8.9    7.48     9.9    8.38    10.9    8.38    12.2    7.38
    22.2    7.38
#Mann= 3 , 0 , 0
   -17.5    .035       0       0    .035       0     9.9    .035       0
Levee=-1,0,15,-1,9.9,15,,
#XS Ineff= 2 , 0
               0    7.68     9.9            8.38
Permanent Ineff=
       F       F
Bank Sta=0,9.9
XS Rating Curve= 0
Exp/Cntr=.3,.1

Type RM Length L Ch R = 1 ,31      ,50,50,50
#Sta/Elev= 14
   -16.9       6    -6.9       6    -5.7     6.6    -1.2     6.6     -.6     7.1
       0     7.1     2.4       5     3.6       5     4.1     5.9     7.1     6.3
     9.7     7.4    10.7     7.4    12.3     6.3    22.3     6.3
#Mann= 3 , 0 , 0
   -16.9    .035       0       0    .035       0     9.7    .035       0
Levee=-1,0,15,-1,9.7,15,,
#XS Ineff= 2 , 0
               0     7.1     9.7             7.4
Permanent Ineff=
       F       F
Bank Sta=0,9.7
XS Rating Curve= 0
Exp/Cntr=.3,.1

Type RM Length L Ch R = 1 ,30      ,50,50,50
#Sta/Elev= 14
   -16.9     5.5    -6.9     5.5    -5.7     6.1    -1.2     6.1     -.6     6.6
       0     6.6     2.4     4.4     3.6     4.4     4.1     5.3     7.1     5.7
     9.7     6.8    10.7     6.8    12.3     5.7    22.3     5.7
#Mann= 3 , 0 , 0
   -16.9    .035       0       0    .035       0     9.7    .035       0
Levee=-1,0,15,-1,9.7,15,,
#XS Ineff= 2 , 0
               0     6.6     9.7             6.8
Permanent Ineff=
       F       F
Bank Sta=0,9.7
XS Rating Curve= 0
Exp/Cntr=.3,.1

Type RM Length L Ch R = 1 ,29      ,50,50,50
#Sta/Elev= 14
   -16.9    5.32    -6.9    5.32    -5.7    5.92    -1.2    5.92     -.6    6.42
       0    6.42     2.4    4.42     3.6    4.42     4.1    5.32     7.1    5.72
     9.7    6.82    10.7    6.82    12.3    5.72    22.3    5.72
#Mann= 3 , 0 , 0
   -16.9    .035       0       0    .035       0     9.7    .035       0
Levee=-1,0,15,-1,9.7,15,,
#XS Ineff= 2 , 0
               0    6.42     9.7            6.82
Permanent Ineff=
       F       F
Bank Sta=0,9.7
XS Rating Curve= 0
Exp/Cntr=.3,.1

Type RM Length L Ch R = 1 ,28      ,27,27,27
#Sta/Elev= 17
   -16.7    5.68    -6.7    5.68    -5.5    6.18       0    6.18       1    5.68
     1.5    4.18     2.6    4.18     3.1    3.58     4.5    3.58     5.1    3.98
     6.3    4.18     6.9    5.18     8.4    5.88    10.7    7.58    11.7    7.58
      14    5.78      24    5.78
#Mann= 3 , 0 , 0
   -16.7    .035       0       0    .035       0    10.7    .035       0
Levee=-1,0,15,-1,10.7,15,,
#XS Ineff= 2 , 0
               0    6.18    10.7            7.58
Permanent Ineff=
       F       F
Bank Sta=0,10.7
XS Rating Curve= 0
Exp/Cntr=.3,.1

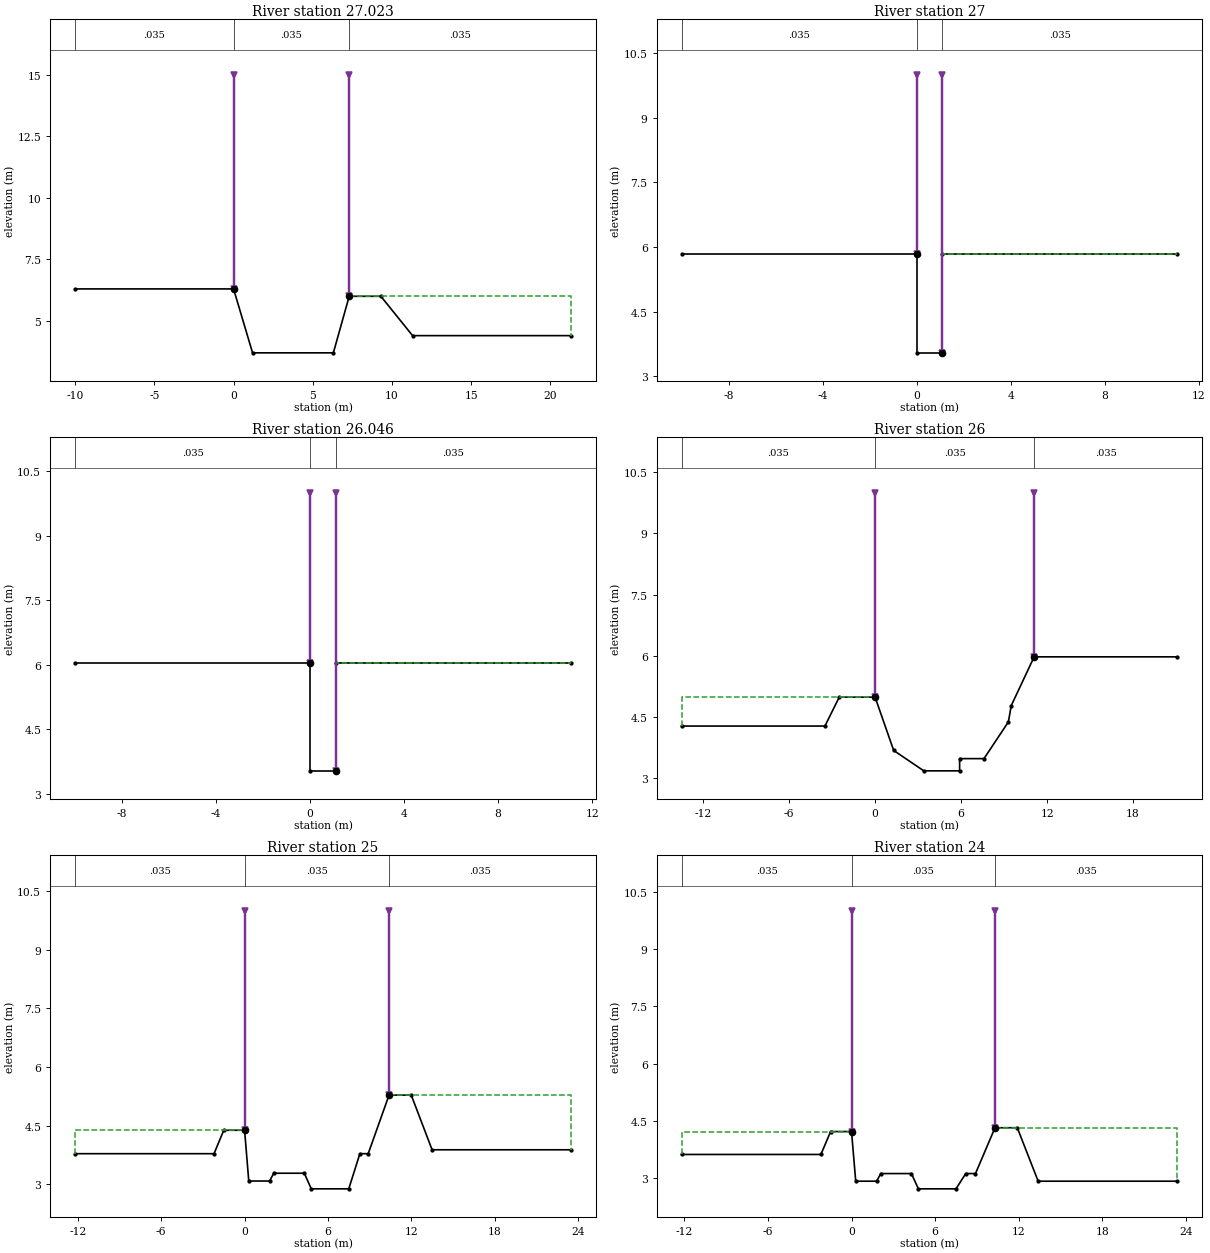
Type RM Length L Ch R = 1 ,27.023  ,23,23,23
#Sta/Elev= 8
     -10    6.29       0    6.29     1.2    3.69     6.3    3.69     7.3    5.99
     9.3    5.99    11.3    4.39    21.3    4.39
#Mann= 3 , 0 , 0
     -10    .035       0       0    .035       0     7.3    .035       0
Levee=-1,0,15,-1,7.3,15,,
#XS Ineff= 2 , 0
               0    6.29     7.3            5.99
Permanent Ineff=
       F       F
Bank Sta=0,7.3
XS Rating Curve= 0
Exp/Cntr=.3,.1

Type RM Length L Ch R = 1 ,27      ,4,4,4
#Sta/Elev= 6
     -10    5.84       0    5.84       0    3.54     1.1    3.54     1.1    5.84
    11.1    5.84
#Mann= 3 , 0 , 0
     -10    .035       0       0    .035       0     1.1    .035       0
Levee=-1,0,10,-1,1.1,10,,
#XS Ineff= 2 , 0
               0    5.84     1.1            5.84
Permanent Ineff=
       F       F
Bank Sta=0,1.1
XS Rating Curve= 0
Exp/Cntr=.3,.1

Type RM Length L Ch R = 1 ,26.046  ,46,46,46
#Sta/Elev= 6
     -10    6.03       0    6.03       0    3.53     1.1    3.53     1.1    6.03
    11.1    6.03
#Mann= 3 , 0 , 0
     -10    .035       0       0    .035       0     1.1    .035       0
Levee=-1,0,10,-1,1.1,10,,
#XS Ineff= 2 , 0
               0    6.03     1.1            6.03
Permanent Ineff=
       F       F
Bank Sta=0,1.1
XS Rating Curve= 0
Exp/Cntr=.3,.1

Type RM Length L Ch R = 1 ,26      ,50,50,50
#Sta/Elev= 13
   -13.5    4.27    -3.5    4.27    -2.5    4.98       0    4.98     1.3    3.67
     3.4    3.17     5.9    3.17     5.9    3.47     7.6    3.47     9.3    4.37
     9.5    4.77    11.1    5.97    21.1    5.97
#Mann= 3 , 0 , 0
   -13.5    .035       0       0    .035       0    11.1    .035       0
Levee=-1,0,10,-1,11.1,10,,
#XS Ineff= 2 , 0
               0    4.98    11.1            5.97
Permanent Ineff=
       F       F
Bank Sta=0,11.1
XS Rating Curve= 0
Exp/Cntr=.3,.1

Type RM Length L Ch R = 1 ,25      ,50,50,50
#Sta/Elev= 16
   -12.2    3.78    -2.2    3.78    -1.5    4.38       0    4.38      .3    3.08
     1.8    3.08     2.1    3.28     4.3    3.28     4.8    2.88     7.5    2.88
     8.3    3.78     8.9    3.78    10.4    5.28      12    5.28    13.5    3.88
    23.5    3.88
#Mann= 3 , 0 , 0
   -12.2    .035       0       0    .035       0    10.4    .035       0
Levee=-1,0,10,-1,10.4,10,,
#XS Ineff= 2 , 0
               0    4.38    10.4            5.28
Permanent Ineff=
       F       F
Bank Sta=0,10.4
XS Rating Curve= 0
Exp/Cntr=.3,.1

Type RM Length L Ch R = 1 ,24      ,50,50,50
#Sta/Elev= 16
   -12.2    3.62    -2.2    3.62    -1.5    4.22       0    4.22      .3    2.92
     1.8    2.92     2.1    3.12     4.3    3.12     4.8    2.72     7.5    2.72
     8.2    3.12     8.9    3.12    10.3    4.32    11.9    4.32    13.4    2.92
    23.4    2.92
#Mann= 3 , 0 , 0
   -12.2    .035       0       0    .035       0    10.3    .035       0
Levee=-1,0,10,-1,10.3,10,,
#XS Ineff= 2 , 0
               0    4.22    10.3            4.32
Permanent Ineff=
       F       F
Bank Sta=0,10.3
XS Rating Curve= 0
Exp/Cntr=.3,.1

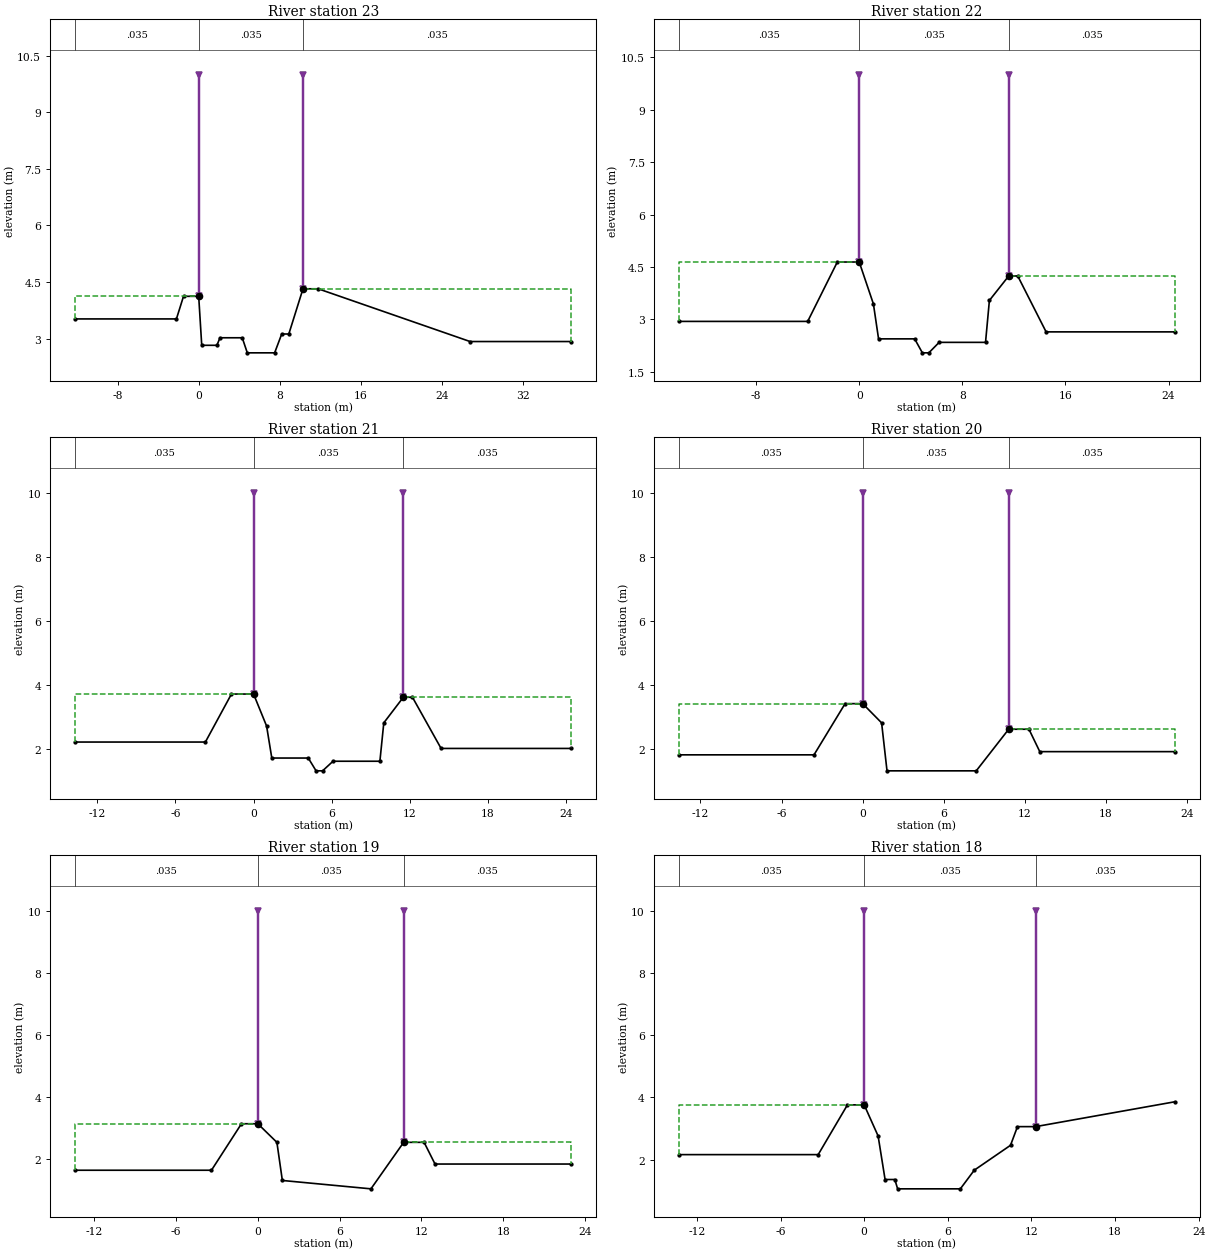
Type RM Length L Ch R = 1 ,23      ,50,50,50
#Sta/Elev= 16
   -12.2    3.52    -2.2    3.52    -1.5    4.12       0    4.12      .3    2.82
     1.8    2.82     2.1    3.02     4.3    3.02     4.8    2.62     7.5    2.62
     8.2    3.12     8.9    3.12    10.3    4.32    11.8    4.32    26.8    2.92
    36.8    2.92
#Mann= 3 , 0 , 0
   -12.2    .035       0       0    .035       0    10.3    .035       0
Levee=-1,0,10,-1,10.3,10,,
#XS Ineff= 2 , 0
               0    4.12    10.3            4.32
Permanent Ineff=
       F       F
Bank Sta=0,10.3
XS Rating Curve= 0
Exp/Cntr=.3,.1

Type RM Length L Ch R = 1 ,22      ,50,50,50
#Sta/Elev= 16
     -14    2.94      -4    2.94    -1.7    4.64       0    4.64     1.1    3.44
     1.5    2.44     4.3    2.44     4.9    2.04     5.4    2.04     6.2    2.34
     9.8    2.34    10.1    3.54    11.6    4.24    12.3    4.24    14.5    2.64
    24.5    2.64
#Mann= 3 , 0 , 0
     -14    .035       0       0    .035       0    11.6    .035       0
Levee=-1,0,10,-1,11.6,10,,
#XS Ineff= 2 , 0
               0    4.64    11.6            4.24
Permanent Ineff=
       F       F
Bank Sta=0,11.6
XS Rating Curve= 0
Exp/Cntr=.3,.1

Type RM Length L Ch R = 1 ,21      ,50,50,50
#Sta/Elev= 16
   -13.7    2.21    -3.7    2.21    -1.7    3.71       0    3.71       1    2.71
     1.4    1.71     4.2    1.71     4.8    1.31     5.3    1.31     6.1    1.61
     9.7    1.61      10    2.81    11.5    3.61    12.2    3.61    14.4    2.01
    24.4    2.01
#Mann= 3 , 0 , 0
   -13.7    .035       0       0    .035       0    11.5    .035       0
Levee=-1,0,10,-1,11.5,10,,
#XS Ineff= 2 , 0
               0    3.71    11.5            3.61
Permanent Ineff=
       F       F
Bank Sta=0,11.5
XS Rating Curve= 0
Exp/Cntr=.3,.1

Type RM Length L Ch R = 1 ,20      ,50,50,50
#Sta/Elev= 11
   -13.6    1.81    -3.6    1.81    -1.3    3.41       0    3.41     1.4    2.81
     1.8    1.31     8.4    1.31    10.8    2.61    12.3    2.61    13.1    1.91
    23.1    1.91
#Mann= 3 , 0 , 0
   -13.6    .035       0       0    .035       0    10.8    .035       0
Levee=-1,0,10,-1,10.8,10,,
#XS Ineff= 2 , 0
               0    3.41    10.8            2.61
Permanent Ineff=
       F       F
Bank Sta=0,10.8
XS Rating Curve= 0
Exp/Cntr=.3,.1

Type RM Length L Ch R = 1 ,19      ,50,50,50
#Sta/Elev= 11
   -13.4    1.63    -3.4    1.63    -1.2    3.13       0    3.13     1.4    2.53
     1.8     1.3     8.3    1.03    10.7    2.53    12.2    2.53      13    1.83
      23    1.83
#Mann= 3 , 0 , 0
   -13.4    .035       0       0    .035       0    10.7    .035       0
Levee=-1,0,10,-1,10.7,10,,
#XS Ineff= 2 , 0
               0    3.13    10.7            2.53
Permanent Ineff=
       F       F
Bank Sta=0,10.7
XS Rating Curve= 0
Exp/Cntr=.3,.1

Type RM Length L Ch R = 1 ,18      ,50,50,50
#Sta/Elev= 14
   -13.3    2.16    -3.3    2.16    -1.2    3.76       0    3.76       1    2.76
     1.5    1.36     2.2    1.36     2.4    1.06     6.9    1.06     7.9    1.66
    10.5    2.46      11    3.06    12.3    3.06    22.3    3.86
#Mann= 3 , 0 , 0
   -13.3    .035       0       0    .035       0    12.3    .035       0
Levee=-1,0,10,-1,12.3,10,,
#XS Ineff= 2 , 0
               0    3.76    12.3            3.06
Permanent Ineff=
       F       F
Bank Sta=0,12.3
XS Rating Curve= 0
Exp/Cntr=.3,.1

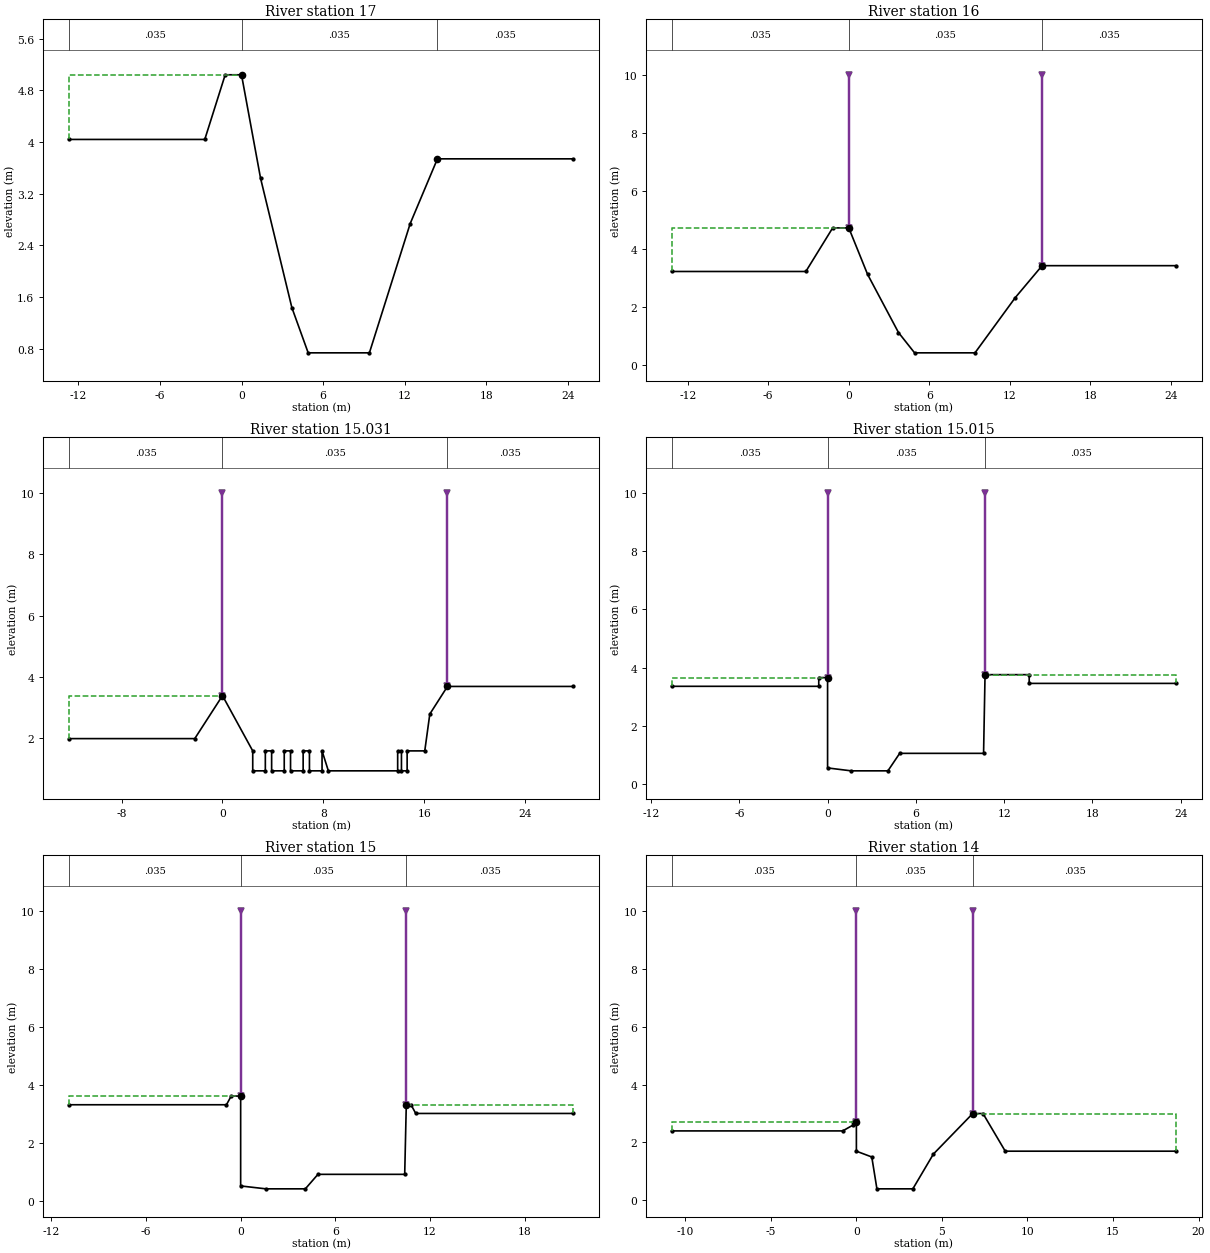
Type RM Length L Ch R = 1 ,17      ,50,50,50
#Sta/Elev= 11
   -12.7    4.04    -2.7    4.04    -1.2    5.04       0    5.04     1.4    3.44
     3.7    1.44     4.9     .74     9.4     .74    12.4    2.74    14.4    3.74
    24.4    3.74
#Mann= 3 , 0 , 0
   -12.7    .035       0       0    .035       0    14.4    .035       0
#XS Ineff= 2 , 0
               0    5.04    14.4            3.74
Permanent Ineff=
       F       F
Bank Sta=0,14.4
XS Rating Curve= 0
Exp/Cntr=.3,.1

Type RM Length L Ch R = 1 ,16      ,19,19,19
#Sta/Elev= 11
   -13.2    3.23    -3.2    3.23    -1.2    4.73       0    4.73     1.4    3.13
     3.7    1.13     4.9     .43     9.4     .43    12.4    2.33    14.4    3.43
    24.4    3.43
#Mann= 3 , 0 , 0
   -13.2    .035       0       0    .035       0    14.4    .035       0
Levee=-1,0,10,-1,14.4,10,,
#XS Ineff= 2 , 0
               0    4.73    14.4            3.43
Permanent Ineff=
       F       F
Bank Sta=0,14.4
XS Rating Curve= 0
Exp/Cntr=.3,.1

Type RM Length L Ch R = 1 ,15.031  ,16,16,16
#Sta/Elev= 30
   -12.2    1.99    -2.2    1.99       0    3.39     2.4    1.59     2.4     .94
     3.4     .94     3.4    1.59     3.9    1.59     3.9     .94     4.9     .94
     4.9    1.59     5.4    1.59     5.4     .94     6.4     .94     6.4    1.59
     6.9    1.59     6.9     .94     7.9     .94     7.9    1.59     8.4     .94
    13.9     .94    13.9    1.59    14.2    1.59    14.2     .94   14.65     .94
   14.65    1.59   16.05    1.59   16.45    2.79   17.85    3.69   27.85    3.69
#Mann= 3 , 0 , 0
   -12.2    .035       0       0    .035       0   17.85    .035       0
Levee=-1,0,10,-1,17.85,10,,
#XS Ineff= 2 , 0
               0    3.39   17.85            3.69
Permanent Ineff=
       F       F
Bank Sta=0,17.85
XS Rating Curve= 0
Exp/Cntr=.3,.1

Type RM Length L Ch R = 1 ,15.015  ,15,15,15
#Sta/Elev= 13
   -10.6    3.36     -.6    3.36     -.6    3.66       0    3.66       0     .56
     1.6     .46     4.1     .46     4.9    1.06    10.6    1.06    10.7    3.76
    13.7    3.76    13.7    3.46    23.7    3.46
#Mann= 3 , 0 , 0
   -10.6    .035       0       0    .035       0    10.7    .035       0
Levee=-1,0,10,-1,10.7,10,,
#XS Ineff= 2 , 0
               0    3.66    10.7            3.76
Permanent Ineff=
       F       F
Bank Sta=0,10.7
XS Rating Curve= 0
Exp/Cntr=.3,.1

Type RM Length L Ch R = 1 ,15      ,50,50,50
#Sta/Elev= 13
   -10.9    3.31     -.9    3.31     -.6    3.61       0    3.61       0     .51
     1.6     .41     4.1     .41     4.9     .91    10.4     .91    10.5    3.31
    10.8    3.31    11.1    3.01    21.1    3.01
#Mann= 3 , 0 , 0
   -10.9    .035       0       0    .035       0    10.5    .035       0
Levee=-1,0,10,-1,10.5,10,,
#XS Ineff= 2 , 0
               0    3.61    10.5            3.31
Permanent Ineff=
       F       F
Bank Sta=0,10.5
XS Rating Curve= 0
Exp/Cntr=.3,.1

Type RM Length L Ch R = 1 ,14      ,50,50,50
#Sta/Elev= 14
   -10.8     2.4     -.8     2.4     -.2     2.6     -.2     2.7       0     2.7
       0     1.7      .9     1.5     1.2      .4     3.3      .4     4.5     1.6
     6.8       3     7.4       3     8.7     1.7    18.7     1.7
#Mann= 3 , 0 , 0
   -10.8    .035       0       0    .035       0     6.8    .035       0
Levee=-1,0,10,-1,6.8,10,,
#XS Ineff= 2 , 0
               0     2.7     6.8               3
Permanent Ineff=
       F       F
Bank Sta=0,6.8
XS Rating Curve= 0
Exp/Cntr=.3,.1

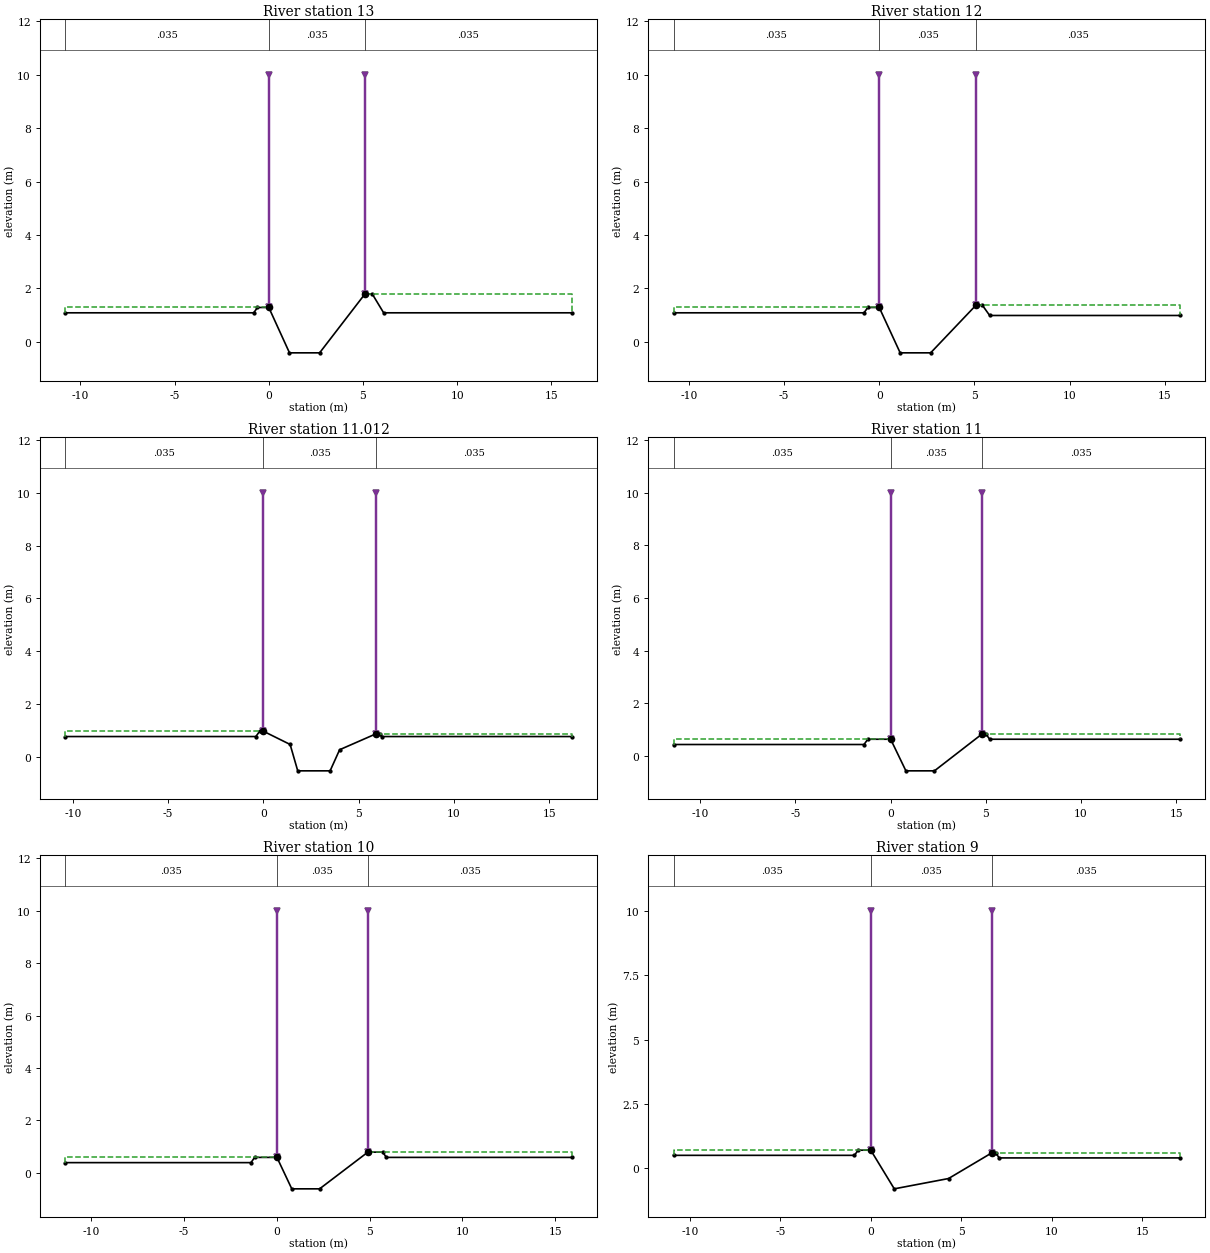
Type RM Length L Ch R = 1 ,13      ,50,50,50
#Sta/Elev= 10
   -10.8    1.08     -.8    1.08     -.6    1.28       0    1.28     1.1    -.42
     2.7    -.42     5.1    1.78     5.5    1.78     6.1    1.08    16.1    1.08
#Mann= 3 , 0 , 0
   -10.8    .035       0       0    .035       0     5.1    .035       0
Levee=-1,0,10,-1,5.1,10,,
#XS Ineff= 2 , 0
               0    1.28     5.1            1.78
Permanent Ineff=
       F       F
Bank Sta=0,5.1
XS Rating Curve= 0
Exp/Cntr=.3,.1

Type RM Length L Ch R = 1 ,12      ,38,38,38
#Sta/Elev= 10
   -10.8    1.08     -.8    1.08     -.6    1.28       0    1.28     1.1    -.42
     2.7    -.42     5.1    1.38     5.4    1.38     5.8     .98    15.8     .98
#Mann= 3 , 0 , 0
   -10.8    .035       0       0    .035       0     5.1    .035       0
Levee=-1,0,10,-1,5.1,10,,
#XS Ineff= 2 , 0
               0    1.28     5.1            1.38
Permanent Ineff=
       F       F
Bank Sta=0,5.1
XS Rating Curve= 0
Exp/Cntr=.3,.1

Type RM Length L Ch R = 1 ,11.012  ,12,12,12
#Sta/Elev= 12
   -10.4     .76     -.4     .76     -.2     .96       0     .96     1.4     .46
     1.8    -.54     3.5    -.54       4     .26     5.9     .86     6.1     .86
     6.2     .76    16.2     .76
#Mann= 3 , 0 , 0
   -10.4    .035       0       0    .035       0     5.9    .035       0
Levee=-1,0,10,-1,5.9,10,,
#XS Ineff= 2 , 0
               0     .96     5.9             .86
Permanent Ineff=
       F       F
Bank Sta=0,5.9
XS Rating Curve= 0
Exp/Cntr=.3,.1

Type RM Length L Ch R = 1 ,11      ,50,50,50
#Sta/Elev= 10
   -11.4     .44    -1.4     .44    -1.2     .64       0     .64      .8    -.56
     2.3    -.56     4.8     .84       5     .84     5.2     .64    15.2     .64
#Mann= 3 , 0 , 0
   -11.4    .035       0       0    .035       0     4.8    .035       0
Levee=-1,0,10,-1,4.8,10,,
#XS Ineff= 2 , 0
               0     .64     4.8             .84
Permanent Ineff=
       F       F
Bank Sta=0,4.8
XS Rating Curve= 0
Exp/Cntr=.3,.1

Type RM Length L Ch R = 1 ,10      ,50,50,50
#Sta/Elev= 10
   -11.4     .39    -1.4     .39    -1.2     .59       0     .59      .8    -.61
     2.3    -.61     4.9     .79     5.7     .79     5.9     .59    15.9     .59
#Mann= 3 , 0 , 0
   -11.4    .035       0       0    .035       0     4.9    .035       0
Levee=-1,0,10,-1,4.9,10,,
#XS Ineff= 2 , 0
               0     .59     4.9             .79
Permanent Ineff=
       F       F
Bank Sta=0,4.9
XS Rating Curve= 0
Exp/Cntr=.3,.1

Type RM Length L Ch R = 1 ,9       ,50,50,50
#Sta/Elev= 10
   -10.9     .51     -.9     .51     -.7     .71       0     .71     1.3    -.79
     4.3    -.39     6.7     .61     6.9     .61     7.1     .41    17.1     .41
#Mann= 3 , 0 , 0
   -10.9    .035       0       0    .035       0     6.7    .035       0
Levee=-1,0,10,-1,6.7,10,,
#XS Ineff= 2 , 0
               0     .71     6.7             .61
Permanent Ineff=
       F       F
Bank Sta=0,6.7
XS Rating Curve= 0
Exp/Cntr=.3,.1

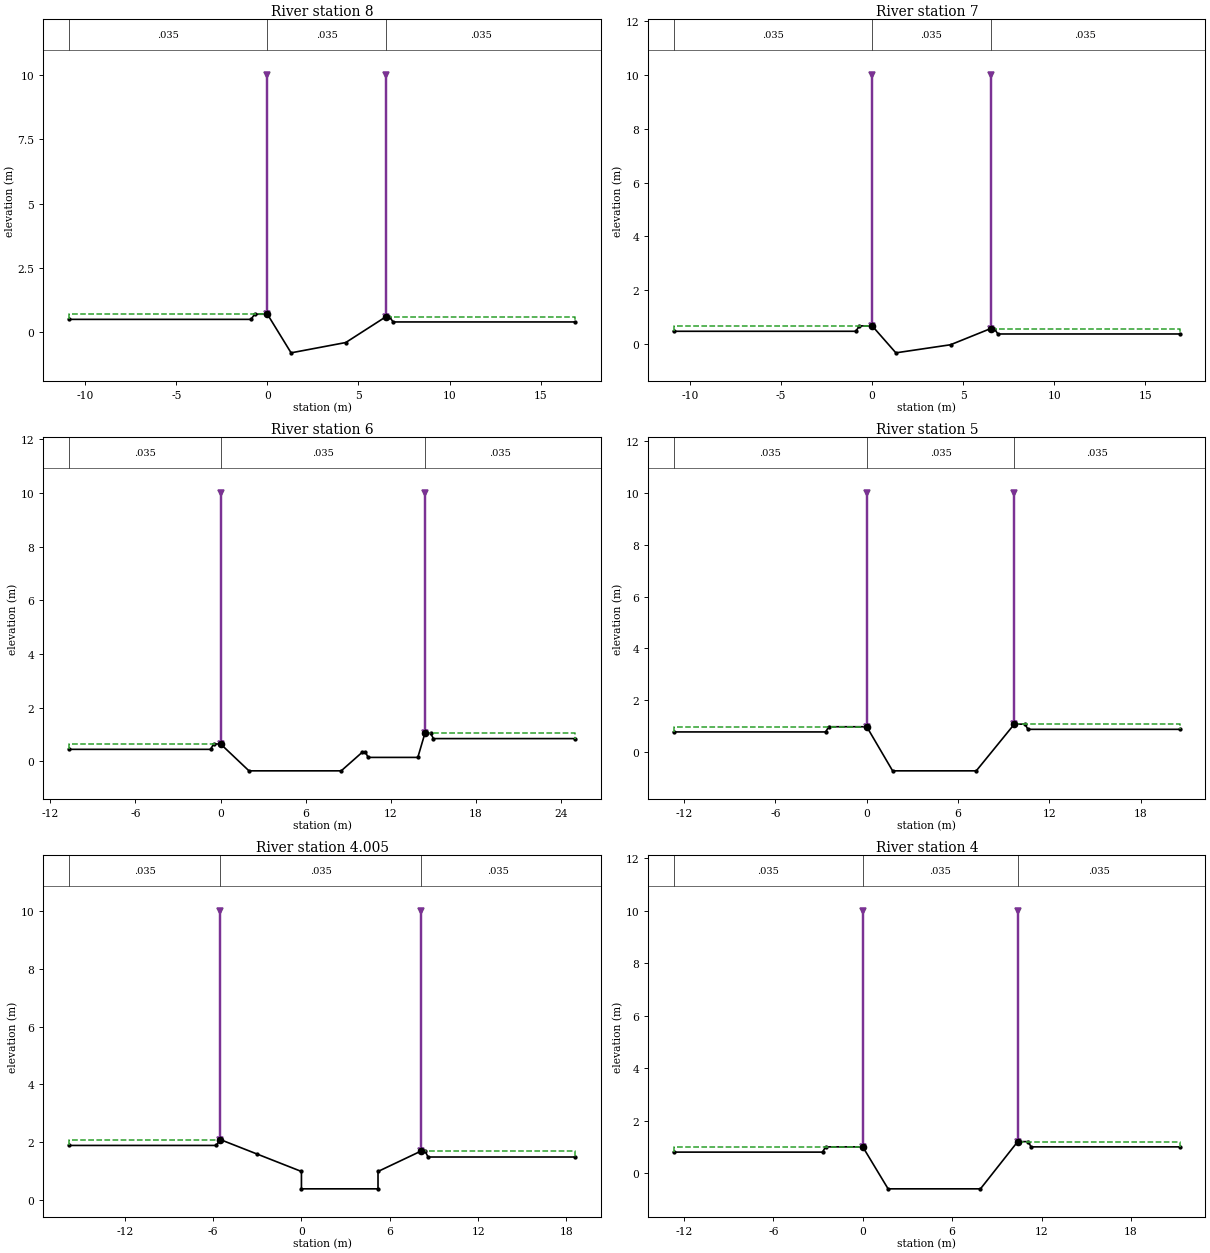
Type RM Length L Ch R = 1 ,8       ,50,50,50
#Sta/Elev= 10
   -10.9      .5     -.9      .5     -.7      .7       0      .7     1.3     -.8
     4.3     -.4     6.5      .6     6.7      .6     6.9      .4    16.9      .4
#Mann= 3 , 0 , 0
   -10.9    .035       0       0    .035       0     6.5    .035       0
Levee=-1,0,10,-1,6.5,10,,
#XS Ineff= 2 , 0
               0      .7     6.5              .6
Permanent Ineff=
       F       F
Bank Sta=0,6.5
XS Rating Curve= 0
Exp/Cntr=.3,.1

Type RM Length L Ch R = 1 ,7       ,50,50,50
#Sta/Elev= 10
   -10.9     .48     -.9     .48     -.7     .68       0     .68     1.3    -.32
     4.3    -.02     6.5     .58     6.7     .58     6.9     .38    16.9     .38
#Mann= 3 , 0 , 0
   -10.9    .035       0       0    .035       0     6.5    .035       0
Levee=-1,0,10,-1,6.5,10,,
#XS Ineff= 2 , 0
               0     .68     6.5             .58
Permanent Ineff=
       F       F
Bank Sta=0,6.5
XS Rating Curve= 0
Exp/Cntr=.3,.1

Type RM Length L Ch R = 1 ,6       ,50,50,50
#Sta/Elev= 14
   -10.7     .45     -.7     .45     -.5     .65       0     .65       2    -.35
     8.5    -.35      10     .35    10.2     .35    10.4     .15    13.9     .15
    14.4    1.05    14.8    1.05      15     .85      25     .85
#Mann= 3 , 0 , 0
   -10.7    .035       0       0    .035       0    14.4    .035       0
Levee=-1,0,10,-1,14.4,10,,
#XS Ineff= 2 , 0
               0     .65    14.4            1.05
Permanent Ineff=
       F       F
Bank Sta=0,14.4
XS Rating Curve= 0
Exp/Cntr=.3,.1

Type RM Length L Ch R = 1 ,5       ,45,45,45
#Sta/Elev= 10
   -12.7     .78    -2.7     .78    -2.5     .98       0     .98     1.7    -.72
     7.2    -.72     9.7    1.08    10.4    1.08    10.6     .88    20.6     .88
#Mann= 3 , 0 , 0
   -12.7    .035       0       0    .035       0     9.7    .035       0
Levee=-1,0,10,-1,9.7,10,,
#XS Ineff= 2 , 0
               0     .98     9.7            1.08
Permanent Ineff=
       F       F
Bank Sta=0,9.7
XS Rating Curve= 0
Exp/Cntr=.3,.1

Type RM Length L Ch R = 1 ,4.005   ,5,5,5
#Sta/Elev= 12
   -15.8    1.89    -5.8    1.89    -5.5    2.09      -3    1.59       0     .99
       0     .39     5.2     .39     5.2     .99     8.1    1.69     8.4    1.69
     8.6    1.49    18.6    1.49
#Mann= 3 , 0 , 0
   -15.8    .035       0    -5.5    .035       0     8.1    .035       0
Levee=-1,-5.5,10,-1,8.1,10,,
#XS Ineff= 2 , 0
            -5.5    2.09     8.1            1.69
Permanent Ineff=
       F       F
Bank Sta=-5.5,8.1
XS Rating Curve= 0
Exp/Cntr=.3,.1

Type RM Length L Ch R = 1 ,4       ,50,50,50
#Sta/Elev= 10
   -12.7      .8    -2.7      .8    -2.5       1       0       1     1.7     -.6
     7.9     -.6    10.4     1.2    11.1     1.2    11.3       1    21.3       1
#Mann= 3 , 0 , 0
   -12.7    .035       0       0    .035       0    10.4    .035       0
Levee=-1,0,10,-1,10.4,10,,
#XS Ineff= 2 , 0
               0       1    10.4             1.2
Permanent Ineff=
       F       F
Bank Sta=0,10.4
XS Rating Curve= 0
Exp/Cntr=.3,.1

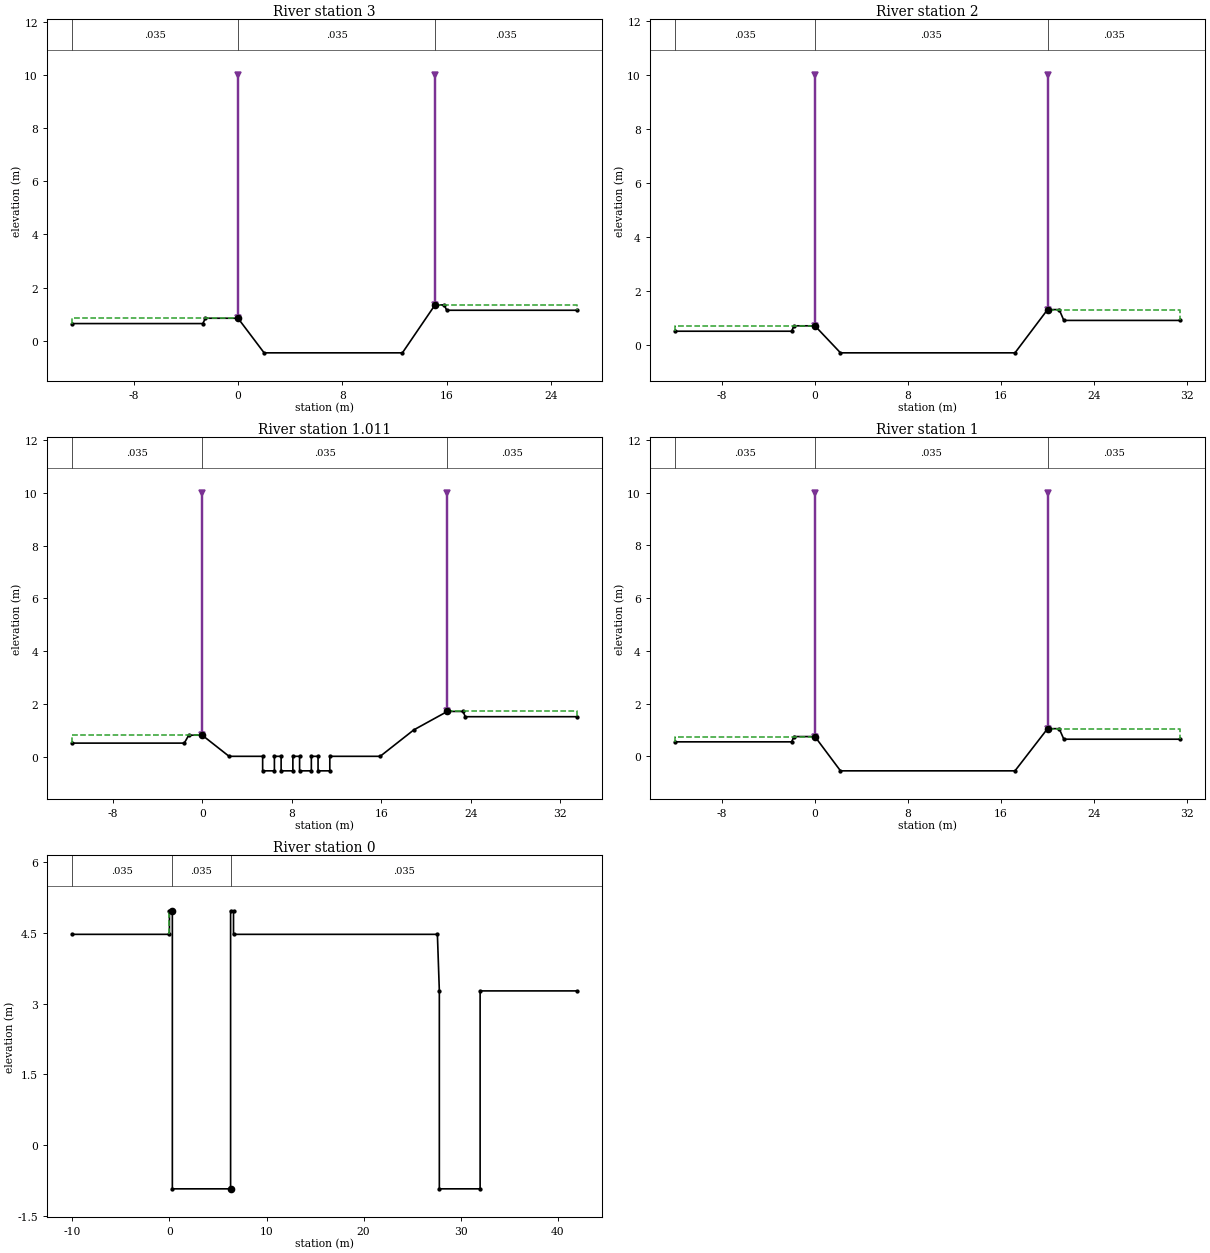
Type RM Length L Ch R = 1 ,3       ,50,50,50
#Sta/Elev= 10
   -12.7     .65    -2.7     .65    -2.5     .85       0     .85       2    -.45
    12.6    -.45    15.1    1.35    15.8    1.35      16    1.15      26    1.15
#Mann= 3 , 0 , 0
   -12.7    .035       0       0    .035       0    15.1    .035       0
Levee=-1,0,10,-1,15.1,10,,
#XS Ineff= 2 , 0
               0     .85    15.1            1.35
Permanent Ineff=
       F       F
Bank Sta=0,15.1
XS Rating Curve= 0
Exp/Cntr=.3,.1

Type RM Length L Ch R = 1 ,2       ,39,39,39
#Sta/Elev= 10
     -12     .51      -2     .51    -1.8     .71       0     .71     2.2    -.29
    17.2    -.29      20    1.31      21    1.31    21.4     .91    31.4     .91
#Mann= 3 , 0 , 0
     -12    .035       0       0    .035       0      20    .035       0
Levee=-1,0,10,-1,20,10,,
#XS Ineff= 2 , 0
               0     .71      20            1.31
Permanent Ineff=
       F       F
Bank Sta=0,20
XS Rating Curve= 0
Exp/Cntr=.3,.1

Type RM Length L Ch R = 1 ,1.011   ,11,11,11
#Sta/Elev= 27
   -11.6     .52    -1.6     .52    -1.2     .82       0     .82     2.4     .02
     5.4     .02     5.4    -.53    6.45    -.53    6.45     .02    7.05     .02
    7.05    -.53     8.1    -.53     8.1     .02     8.7     .02     8.7    -.53
    9.75    -.53    9.75     .02   10.35     .02   10.35    -.53    11.4    -.53
    11.4     .02    15.9     .02    18.9    1.02    21.9    1.72    23.3    1.72
    23.5    1.52    33.5    1.52
#Mann= 3 , 0 , 0
   -11.6    .035       0       0    .035       0    21.9    .035       0
Levee=-1,0,10,-1,21.9,10,,
#XS Ineff= 2 , 0
               0     .82    21.9            1.72
Permanent Ineff=
       F       F
Bank Sta=0,21.9
XS Rating Curve= 0
Exp/Cntr=.3,.1

Type RM Length L Ch R = 1 ,1       ,50,50,50
#Sta/Elev= 10
     -12     .55      -2     .55    -1.8     .75       0     .75     2.2    -.55
    17.2    -.55      20    1.05      21    1.05    21.4     .65    31.4     .65
#Mann= 3 , 0 , 0
     -12    .035       0       0    .035       0      20    .035       0
Levee=-1,0,10,-1,20,10,,
#XS Ineff= 2 , 0
               0     .75      20            1.05
Permanent Ineff=
       F       F
Bank Sta=0,20
XS Rating Curve= 0
Exp/Cntr=.3,.1

Type RM Length L Ch R = 1 ,0       ,0,0,0
#Sta/Elev= 15
     -10    4.47       0    4.47       0    4.97      .3    4.97      .3    -.93
     6.3    -.93     6.3    4.97     6.6    4.97     6.6    4.47    27.6    4.47
    27.8    3.27    27.8    -.93      32    -.93      32    3.27      42    3.27
#Mann= 3 , 0 , 0
     -10    .035       0      .3    .035       0     6.3    .035       0
#XS Ineff= 2 , 0
       0      .3    4.97     6.3       0    -.93
Permanent Ineff=
       F       F
Bank Sta=.3,6.3
XS Rating Curve= 0
Exp/Cntr=.3,.1

Chan Stop Cuts=-1