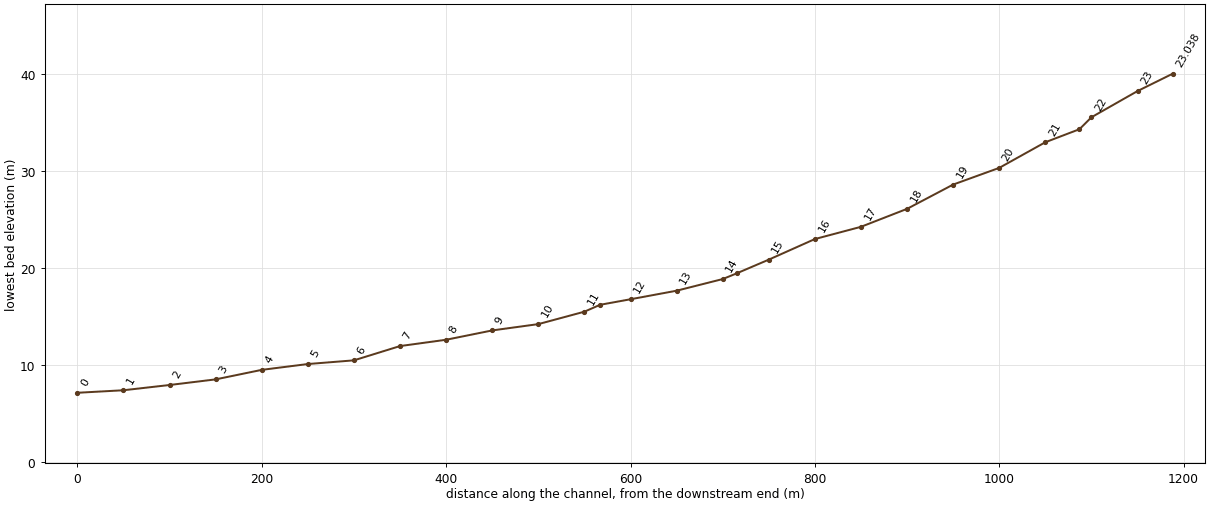
--- epc.prj (project) ---

Proj Title=enpo-ch
Current Plan=p01
Default Exp/Contr=.3,.1
SI Units
Geom File=g01
Flow File=f01
Plan File=p01
Y Axis Title=Elevation
X Axis Title(PF)=Main Channel Distance
X Axis Title(XS)=Station
BEGIN DESCRIPTION:
           BACK WATER COMPUTATION
      APPLICATION OF HEC-2 BY Samju Construction Engineering
      enpo-ch: 10,20,30,50,80 yr
END DESCRIPTION:
DSS Export Rating Curves= 0
DSS Export Rating Curve Sorted= 0
DSS Export Volume Flow Curves= 0
DXF OffsetX= 0
DXF OffsetY= 0
DXF ScaleX= 1
DXF ScaleY= 10

--- epc.p01 (plan) ---

Plan Title=Imported Plan 01
Version=Version 3.0.1  Mar 2001
Short Identifier=Imported Pla
Geom File=g01
Flow File=f01
Subcritical Flow
K Sum by GR= 0
Std Step Tol= 0.003
Critical Tol= 0.003
Num of Std Step Trials= 20
Max Error Tol= 0.1
Flow Tol Ratio= 0.001
Split Flow NTrial= 30
Split Flow Tol= 0.02
Split Flow Ratio= 0.02
Log Output Level= 0
Friction Slope Method= 1
Unsteady Friction Slope Method= 2
Parabolic Critical Depth
Global Vel Dist= 0 , 0 , 0
Global Log Level= 0
CheckData=True
Encroach Param=-1 ,0,0, 0
Computation Interval=1HOUR
Output Interval=1HOUR
Run HTab= 0
Run UNet= 0
Run PostProcess= 0
UNET Theta= 1
UNET ZTol= 0.02
UNET ZSATol= 0.1
UNET MxIter= 20
UNET MaxInSteps= 20
UNET DtIC= 0
UNET DtMin= 0
UNET MaxCRTS= 20
UNET WFStab= 2
UNET SFStab= 1
UNET WFX= 1
UNET SFX= 1
UNET Convert EG Bridges=-1
UNET Use Existing IB Tables=-1
Instantaneous Interval=1HOUR
Write IC File= 0
Write Velocity= 0
Write Detailed= 0

--- epc.f01 (steady flow) ---

Flow Title=Imported Flow 01
Version=Version 3.0.1  Mar 2001
Number of Profiles= 5
Profile Names=10yr,20yr,30yr,50yr,80yr
River Rch & RM=RIVER-1,Reach-1         ,23.038
   11.88   13.09    13.8   14.69    15.5
River Rch & RM=EUNPO,EUNPO           ,23.038
   11.88   13.09    13.8   14.69    15.5
Boundary for River Rch & Prof#=EUNPO,EUNPO           , 1
Up Type= 0
Dn Type= 3
Dn Slope=.0285
Boundary for River Rch & Prof#=EUNPO,EUNPO           , 2
Up Type= 0
Dn Type= 3
Dn Slope=.0285
Boundary for River Rch & Prof#=EUNPO,EUNPO           , 3
Up Type= 0
Dn Type= 3
Dn Slope=.0285
Boundary for River Rch & Prof#=EUNPO,EUNPO           , 4
Up Type= 0
Dn Type= 3
Dn Slope=.0285
Boundary for River Rch & Prof#=EUNPO,EUNPO           , 5
Up Type= 0
Dn Type= 3
Dn Slope=.0285
DSS Import GetInterval= 0
DSS Import GetPeak= 0
DSS Import FillOption= 0

--- epc.g01 (geometry) ---

Geom Title=Imported Geom 01
Version=Version 3.0.1  Mar 2001

River Reach=EUNPO           ,EUNPO
Reach XY= 2
              .5             .95              .5             .05

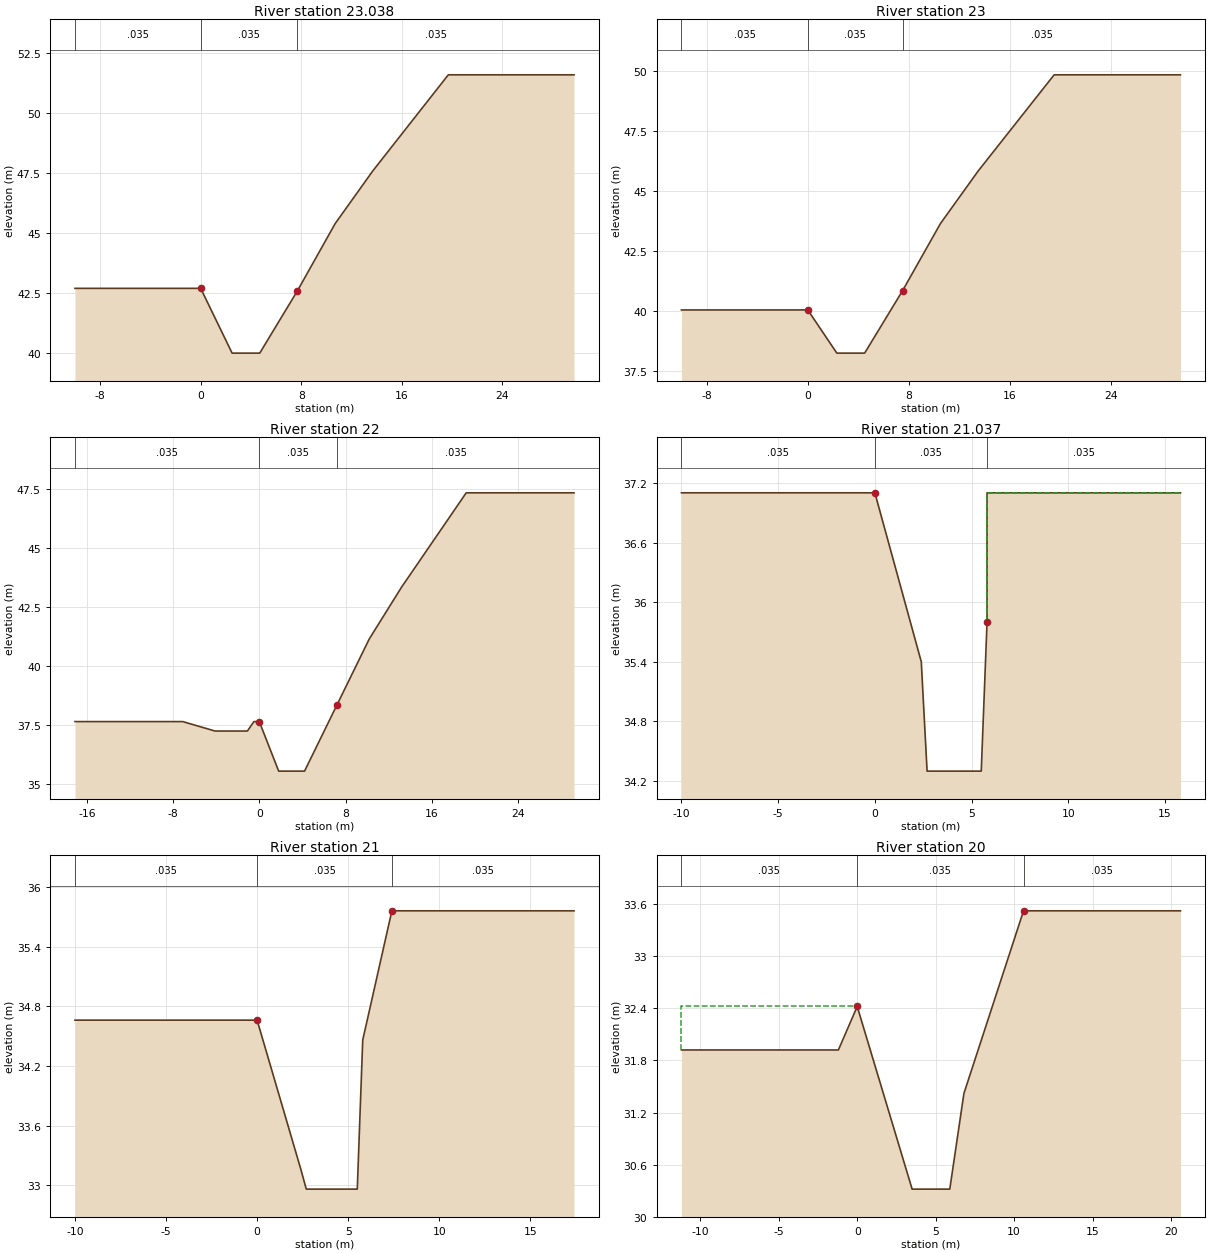
Type RM Length L Ch R = 1 ,23.038  ,38,38,38
#Sta/Elev= 10
     -10   42.71       0   42.71     2.5   40.01     4.7   40.01     7.7   42.61
    10.7   45.41    13.7   47.61    16.7   49.61    19.7   51.61    29.7   51.61
#Mann= 3 , 0 , 0
     -10    .035       0       0    .035       0     7.7    .035       0
#XS Ineff= 2 , 0
               0   42.71     7.7           42.61
Permanent Ineff=
       F       F
Bank Sta=0,7.7
XS Rating Curve= 0
Exp/Cntr=.3,.1

Type RM Length L Ch R = 1 ,23      ,50,50,50
#Sta/Elev= 10
     -10   40.03       0   40.03     2.3   38.23     4.5   38.23     7.5   40.83
    10.5   43.63    13.5   45.83    16.5   47.83    19.5   49.83    29.5   49.83
#Mann= 3 , 0 , 0
     -10    .035       0       0    .035       0     7.5    .035       0
#XS Ineff= 2 , 0
               0   40.03     7.5           40.83
Permanent Ineff=
       F       F
Bank Sta=0,7.5
XS Rating Curve= 0
Exp/Cntr=.3,.1

Type RM Length L Ch R = 1 ,22      ,13,13,13
#Sta/Elev= 14
   -17.1   37.63    -7.1   37.63    -4.1   37.23    -1.1   37.23     -.5   37.63
       0   37.63     1.8   35.53     4.2   35.53     7.2   38.33    10.2   41.13
    13.2   43.33    16.2   45.33    19.2   47.33    29.2   47.33
#Mann= 3 , 0 , 0
   -17.1    .035       0       0    .035       0     7.2    .035       0
#XS Ineff= 2 , 0
               0   37.63     7.2           38.33
Permanent Ineff=
       F       F
Bank Sta=0,7.2
XS Rating Curve= 0
Exp/Cntr=.3,.1

Type RM Length L Ch R = 1 ,21.037  ,37,37,37
#Sta/Elev= 8
     -10    37.1       0    37.1     2.4    35.4     2.7    34.3     5.5    34.3
     5.8    35.8     5.8    37.1    15.8    37.1
#Mann= 3 , 0 , 0
     -10    .035       0       0    .035       0     5.8    .035       0
#XS Ineff= 2 , 0
               0    37.1     5.8            37.1
Permanent Ineff=
       F       F
Bank Sta=0,5.8
XS Rating Curve= 0
Exp/Cntr=.3,.1

Type RM Length L Ch R = 1 ,21      ,50,50,50
#Sta/Elev= 8
     -10   34.66       0   34.66     2.4   33.16     2.7   32.96     5.5   32.96
     5.8   34.46     7.4   35.76    17.4   35.76
#Mann= 3 , 0 , 0
     -10    .035       0       0    .035       0     7.4    .035       0
#XS Ineff= 2 , 0
               0   34.66     7.4           35.76
Permanent Ineff=
       F       F
Bank Sta=0,7.4
XS Rating Curve= 0
Exp/Cntr=.3,.1

Type RM Length L Ch R = 1 ,20      ,50,50,50
#Sta/Elev= 8
   -11.2   31.92    -1.2   31.92       0   32.42     3.5   30.32     5.9   30.32
     6.8   31.42    10.6   33.52    20.6   33.52
#Mann= 3 , 0 , 0
   -11.2    .035       0       0    .035       0    10.6    .035       0
#XS Ineff= 2 , 0
               0   32.42    10.6           33.52
Permanent Ineff=
       F       F
Bank Sta=0,10.6
XS Rating Curve= 0
Exp/Cntr=.3,.1

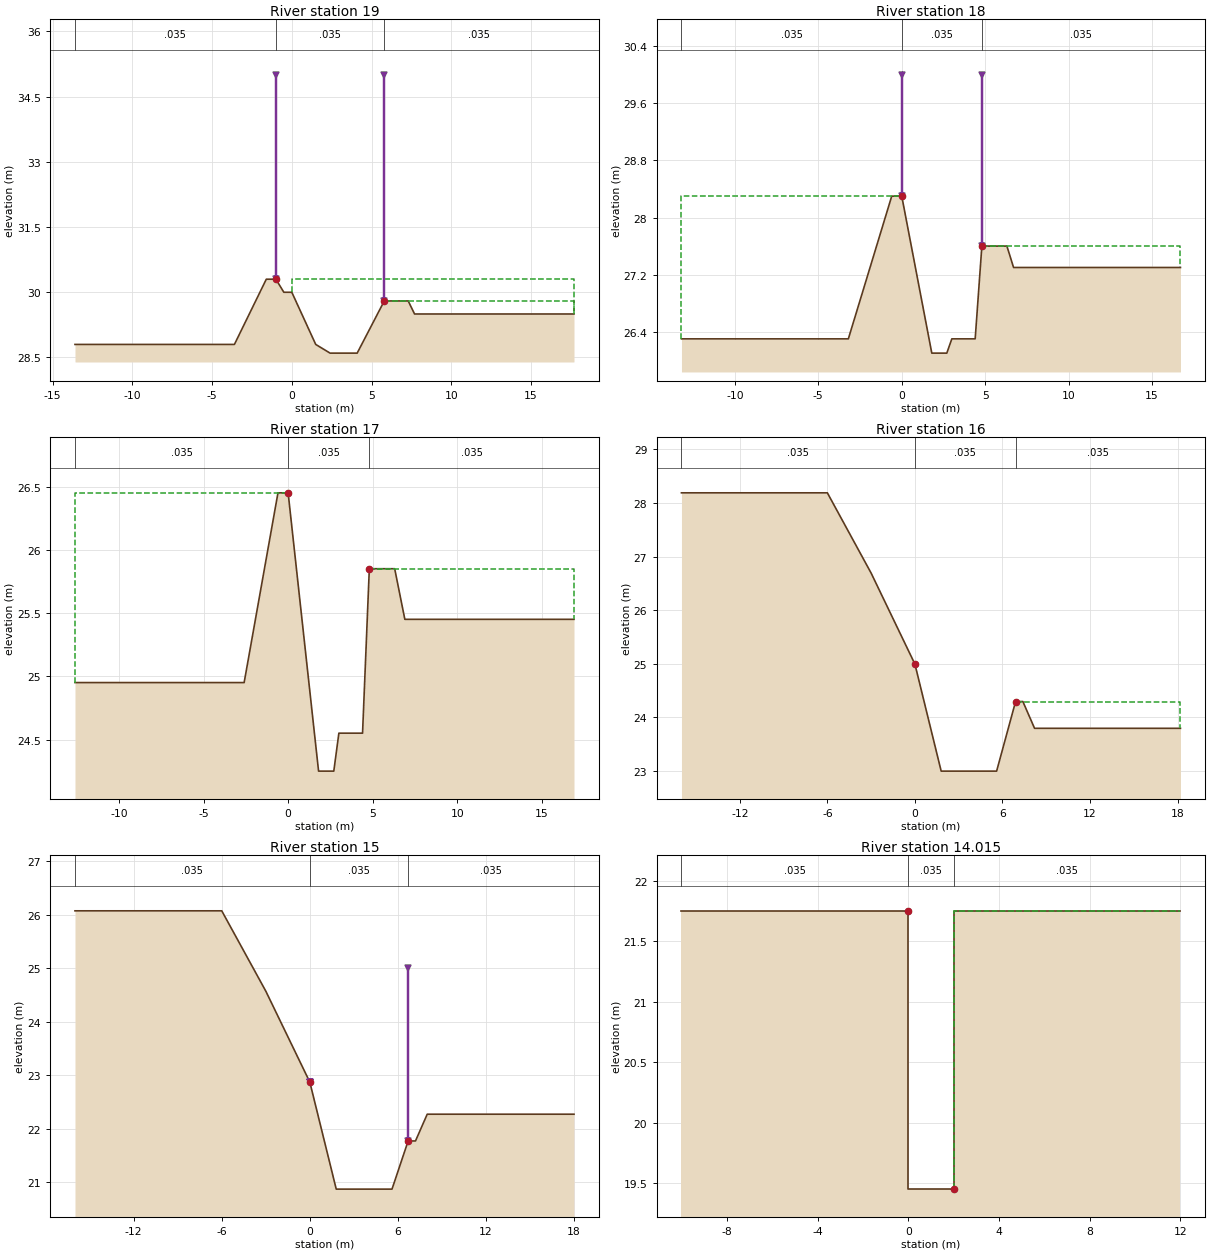
Type RM Length L Ch R = 1 ,19      ,50,50,50
#Sta/Elev= 13
   -13.6    28.8    -3.6    28.8    -1.6    30.3      -1    30.3     -.5      30
       0      30     1.5    28.8     2.4    28.6     4.1    28.6     5.8    29.8
     7.3    29.8     7.7    29.5    17.7    29.5
#Mann= 3 , 0 , 0
   -13.6    .035       0      -1    .035       0     5.8    .035       0
Levee=-1,-1,35,-1,5.8,35,,
#XS Ineff= 2 , 0
       0      -1    30.3     5.8       0    29.8
Permanent Ineff=
       F       F
Bank Sta=-1,5.8
XS Rating Curve= 0
Exp/Cntr=.3,.1

Type RM Length L Ch R = 1 ,18      ,50,50,50
#Sta/Elev= 12
   -13.2    26.3    -3.2    26.3     -.6    28.3       0    28.3     1.8    26.1
     2.7    26.1       3    26.3     4.4    26.3     4.8    27.6     6.3    27.6
     6.7    27.3    16.7    27.3
#Mann= 3 , 0 , 0
   -13.2    .035       0       0    .035       0     4.8    .035       0
Levee=-1,0,30,-1,4.8,30,,
#XS Ineff= 2 , 0
               0    28.3     4.8            27.6
Permanent Ineff=
       F       F
Bank Sta=0,4.8
XS Rating Curve= 0
Exp/Cntr=.3,.1

Type RM Length L Ch R = 1 ,17      ,50,50,50
#Sta/Elev= 12
   -12.6   24.95    -2.6   24.95     -.6   26.45       0   26.45     1.8   24.25
     2.7   24.25       3   24.55     4.4   24.55     4.8   25.85     6.3   25.85
     6.9   25.45    16.9   25.45
#Mann= 3 , 0 , 0
   -12.6    .035       0       0    .035       0     4.8    .035       0
#XS Ineff= 2 , 0
               0   26.45     4.8           25.85
Permanent Ineff=
       F       F
Bank Sta=0,4.8
XS Rating Curve= 0
Exp/Cntr=.3,.1

Type RM Length L Ch R = 1 ,16      ,50,50,50
#Sta/Elev= 10
     -16   28.19      -6   28.19      -3   26.69       0   24.99     1.8   22.99
     5.6   22.99     6.9   24.29     7.4   24.29     8.2   23.79    18.2   23.79
#Mann= 3 , 0 , 0
     -16    .035       0       0    .035       0     6.9    .035       0
#XS Ineff= 2 , 0
               0   24.99     6.9           24.29
Permanent Ineff=
       F       F
Bank Sta=0,6.9
XS Rating Curve= 0
Exp/Cntr=.3,.1

Type RM Length L Ch R = 1 ,15      ,35,35,35
#Sta/Elev= 10
     -16   26.07      -6   26.07      -3   24.57       0   22.87     1.8   20.87
     5.6   20.87     6.7   21.77     7.2   21.77       8   22.27      18   22.27
#Mann= 3 , 0 , 0
     -16    .035       0       0    .035       0     6.7    .035       0
Levee=-1,0,22.87,-1,6.7,25,,
#XS Ineff= 2 , 0
               0   22.87     6.7           21.77
Permanent Ineff=
       F       F
Bank Sta=0,6.7
XS Rating Curve= 0
Exp/Cntr=.3,.1

Type RM Length L Ch R = 1 ,14.015  ,15,15,15
#Sta/Elev= 6
     -10   21.75       0   21.75       0   19.45       2   19.45       2   21.75
      12   21.75
#Mann= 3 , 0 , 0
     -10    .035       0       0    .035       0       2    .035       0
#XS Ineff= 2 , 0
               0   21.75       2           21.75
Permanent Ineff=
       F       F
Bank Sta=0,2
XS Rating Curve= 0
Exp/Cntr=.3,.1

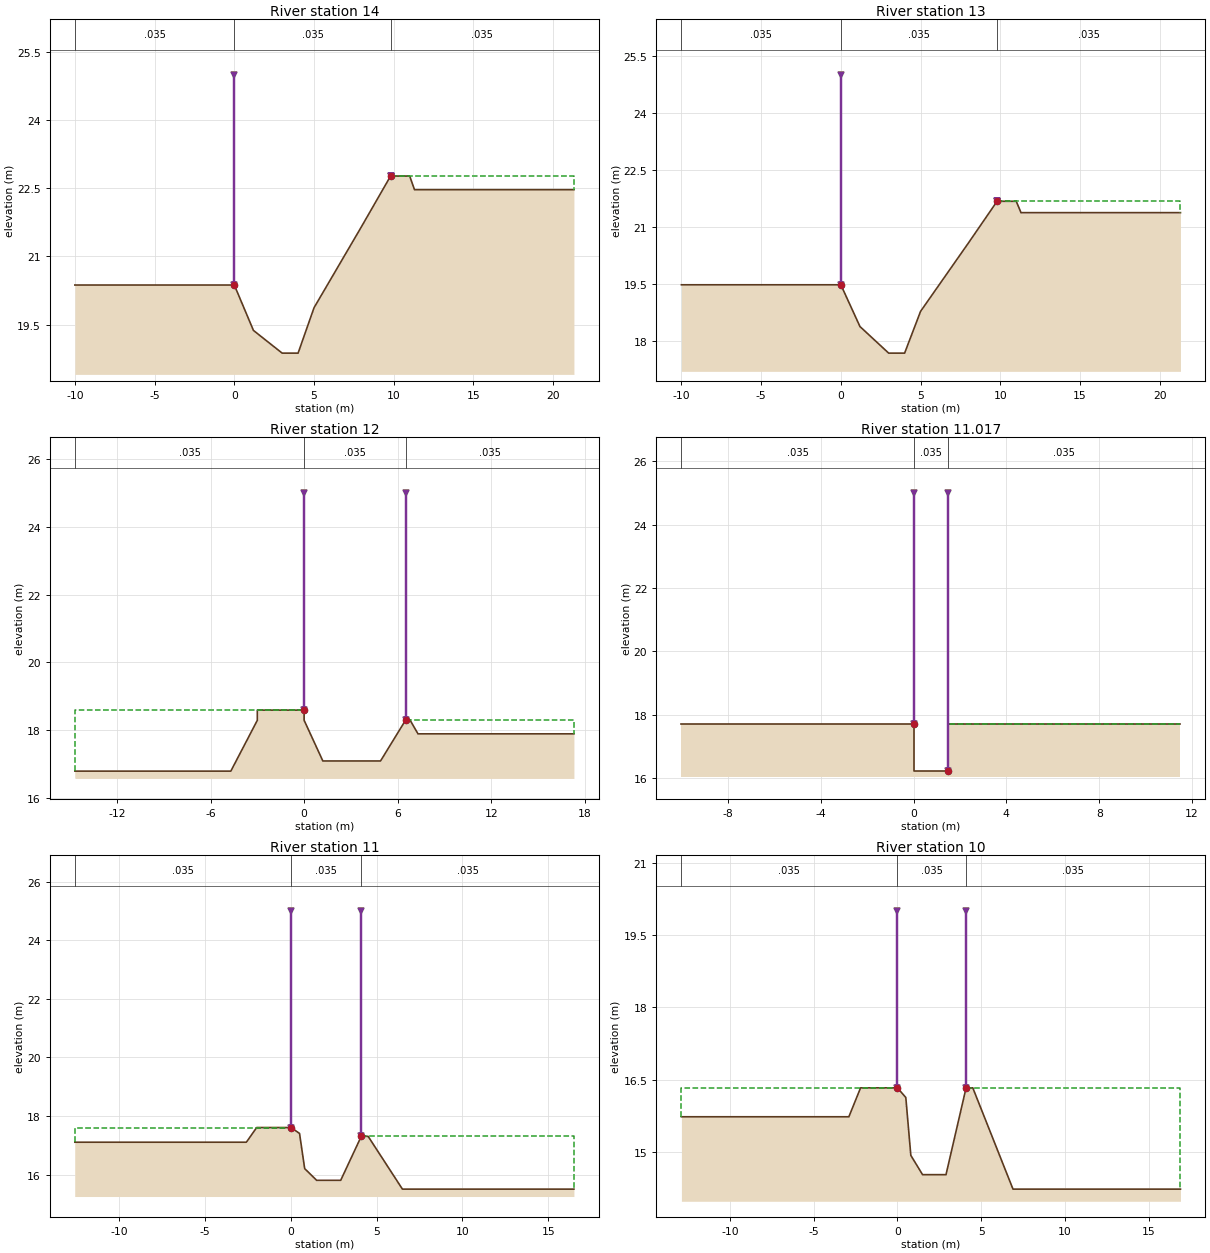
Type RM Length L Ch R = 1 ,14      ,50,50,50
#Sta/Elev= 11
     -10   20.37       0   20.37     1.2   19.37       3   18.87       4   18.87
       5   19.87       8   21.67     9.8   22.77      11   22.77    11.3   22.47
    21.3   22.47
#Mann= 3 , 0 , 0
     -10    .035       0       0    .035       0     9.8    .035       0
Levee=-1,0,25,-1,9.8,22.77,,
#XS Ineff= 2 , 0
               0   20.37     9.8           22.77
Permanent Ineff=
       F       F
Bank Sta=0,9.8
XS Rating Curve= 0
Exp/Cntr=.3,.1

Type RM Length L Ch R = 1 ,13      ,50,50,50
#Sta/Elev= 11
     -10   19.47       0   19.47     1.2   18.37       3   17.67       4   17.67
       5   18.77       8   20.57     9.8   21.67      11   21.67    11.3   21.37
    21.3   21.37
#Mann= 3 , 0 , 0
     -10    .035       0       0    .035       0     9.8    .035       0
Levee=-1,0,25,-1,9.8,21.67,,
#XS Ineff= 2 , 0
               0   19.47     9.8           21.67
Permanent Ineff=
       F       F
Bank Sta=0,9.8
XS Rating Curve= 0
Exp/Cntr=.3,.1

Type RM Length L Ch R = 1 ,12      ,33,33,33
#Sta/Elev= 12
   -14.7   16.79    -4.7   16.79      -3   18.29      -3   18.59       0   18.59
       0   18.29     1.2   17.09     4.9   17.09     6.5   18.29     6.8   18.29
     7.3   17.89    17.3   17.89
#Mann= 3 , 0 , 0
   -14.7    .035       0       0    .035       0     6.5    .035       0
Levee=-1,0,25,-1,6.5,25,,
#XS Ineff= 2 , 0
               0   18.59     6.5           18.29
Permanent Ineff=
       F       F
Bank Sta=0,6.5
XS Rating Curve= 0
Exp/Cntr=.3,.1

Type RM Length L Ch R = 1 ,11.017  ,17,17,17
#Sta/Elev= 6
     -10   17.72       0   17.72       0   16.22     1.5   16.22     1.5   17.72
    11.5   17.72
#Mann= 3 , 0 , 0
     -10    .035       0       0    .035       0     1.5    .035       0
Levee=-1,0,25,-1,1.5,25,,
#XS Ineff= 2 , 0
               0   17.72     1.5           17.72
Permanent Ineff=
       F       F
Bank Sta=0,1.5
XS Rating Curve= 0
Exp/Cntr=.3,.1

Type RM Length L Ch R = 1 ,11      ,50,50,50
#Sta/Elev= 12
   -12.6   17.11    -2.6   17.11      -2   17.61       0   17.61      .5   17.41
      .8   16.21     1.5   15.81     2.9   15.81     4.1   17.31     4.5   17.31
     6.5   15.51    16.5   15.51
#Mann= 3 , 0 , 0
   -12.6    .035       0       0    .035       0     4.1    .035       0
Levee=-1,0,25,-1,4.1,25,,
#XS Ineff= 2 , 0
               0   17.61     4.1           17.31
Permanent Ineff=
       F       F
Bank Sta=0,4.1
XS Rating Curve= 0
Exp/Cntr=.3,.1

Type RM Length L Ch R = 1 ,10      ,50,50,50
#Sta/Elev= 12
   -12.9   15.73    -2.9   15.73    -2.2   16.33       0   16.33      .5   16.13
      .8   14.93     1.5   14.53     2.9   14.53     4.1   16.33     4.5   16.33
     6.9   14.23    16.9   14.23
#Mann= 3 , 0 , 0
   -12.9    .035       0       0    .035       0     4.1    .035       0
Levee=-1,0,20,-1,4.1,20,,
#XS Ineff= 2 , 0
               0   16.33     4.1           16.33
Permanent Ineff=
       F       F
Bank Sta=0,4.1
XS Rating Curve= 0
Exp/Cntr=.3,.1

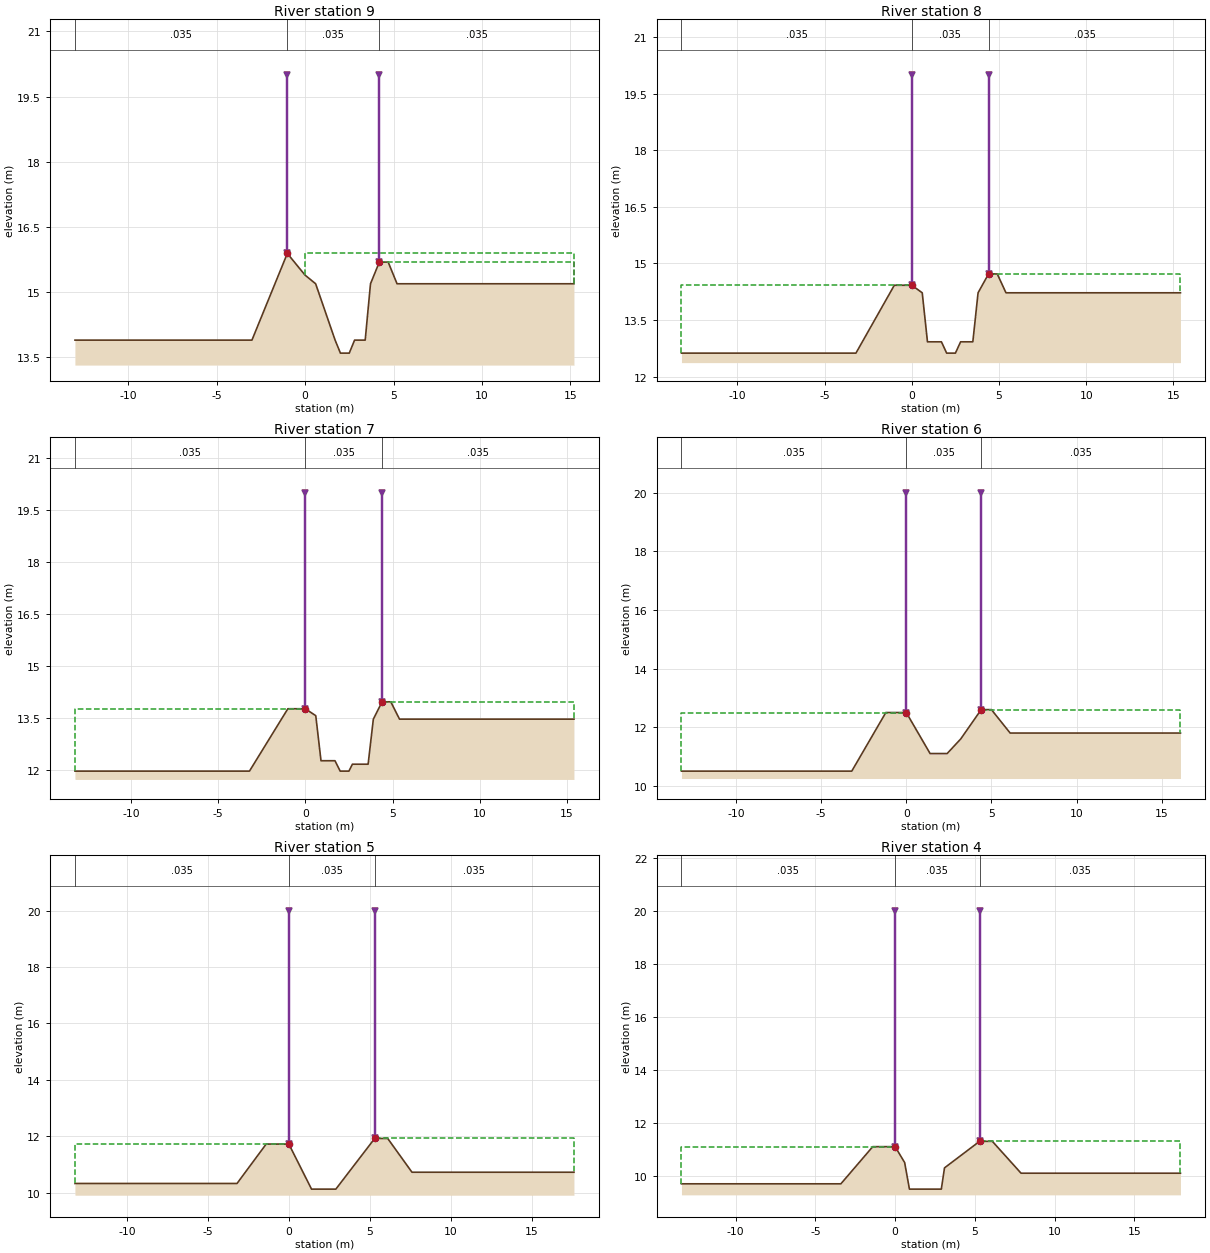
Type RM Length L Ch R = 1 ,9       ,50,50,50
#Sta/Elev= 15
     -13   13.88      -3   13.88      -1   15.88       0   15.38      .6   15.18
     1.7   13.88       2   13.58     2.5   13.58     2.8   13.88     3.4   13.88
     3.7   15.18     4.2   15.68     4.7   15.68     5.2   15.18    15.2   15.18
#Mann= 3 , 0 , 0
     -13    .035       0      -1    .035       0     4.2    .035       0
Levee=-1,-1,20,-1,4.2,20,,
#XS Ineff= 2 , 0
       0      -1   15.88     4.2       0   15.68
Permanent Ineff=
       F       F
Bank Sta=-1,4.2
XS Rating Curve= 0
Exp/Cntr=.3,.1

Type RM Length L Ch R = 1 ,8       ,50,50,50
#Sta/Elev= 17
   -13.2   12.62    -3.2   12.62      -1   14.42     -.8   14.42       0   14.42
      .6   14.22      .9   12.92     1.7   12.92       2   12.62     2.5   12.62
     2.8   12.92     3.5   12.92     3.8   14.22     4.4   14.72     4.9   14.72
     5.4   14.22    15.4   14.22
#Mann= 3 , 0 , 0
   -13.2    .035       0       0    .035       0     4.4    .035       0
Levee=-1,0,20,-1,4.4,20,,
#XS Ineff= 2 , 0
               0   14.42     4.4           14.72
Permanent Ineff=
       F       F
Bank Sta=0,4.4
XS Rating Curve= 0
Exp/Cntr=.3,.1

Type RM Length L Ch R = 1 ,7       ,50,50,50
#Sta/Elev= 16
   -13.2   11.97    -3.2   11.97      -1   13.77       0   13.77      .6   13.57
      .9   12.27     1.7   12.27       2   11.97     2.5   11.97     2.7   12.17
     3.6   12.17     3.9   13.47     4.4   13.97     4.9   13.97     5.4   13.47
    15.4   13.47
#Mann= 3 , 0 , 0
   -13.2    .035       0       0    .035       0     4.4    .035       0
Levee=-1,0,20,-1,4.4,20,,
#XS Ineff= 2 , 0
               0   13.77     4.4           13.97
Permanent Ineff=
       F       F
Bank Sta=0,4.4
XS Rating Curve= 0
Exp/Cntr=.3,.1

Type RM Length L Ch R = 1 ,6       ,50,50,50
#Sta/Elev= 11
   -13.2    10.5    -3.2    10.5    -1.2    12.5       0    12.5     1.4    11.1
     2.4    11.1     3.2    11.6     4.4    12.6       5    12.6     6.1    11.8
    16.1    11.8
#Mann= 3 , 0 , 0
   -13.2    .035       0       0    .035       0     4.4    .035       0
Levee=-1,0,20,-1,4.4,20,,
#XS Ineff= 2 , 0
               0    12.5     4.4            12.6
Permanent Ineff=
       F       F
Bank Sta=0,4.4
XS Rating Curve= 0
Exp/Cntr=.3,.1

Type RM Length L Ch R = 1 ,5       ,50,50,50
#Sta/Elev= 10
   -13.2   10.32    -3.2   10.32    -1.4   11.72       0   11.72     1.4   10.12
     2.9   10.12     5.3   11.92     6.1   11.92     7.6   10.72    17.6   10.72
#Mann= 3 , 0 , 0
   -13.2    .035       0       0    .035       0     5.3    .035       0
Levee=-1,0,20,-1,5.3,20,,
#XS Ineff= 2 , 0
               0   11.72     5.3           11.92
Permanent Ineff=
       F       F
Bank Sta=0,5.3
XS Rating Curve= 0
Exp/Cntr=.3,.1

Type RM Length L Ch R = 1 ,4       ,50,50,50
#Sta/Elev= 12
   -13.4    9.72    -3.4    9.72    -1.4   11.12       0   11.12      .6   10.52
      .9    9.52     2.9    9.52     3.1   10.32     5.3   11.32     6.1   11.32
     7.9   10.12    17.9   10.12
#Mann= 3 , 0 , 0
   -13.4    .035       0       0    .035       0     5.3    .035       0
Levee=-1,0,20,-1,5.3,20,,
#XS Ineff= 2 , 0
               0   11.12     5.3           11.32
Permanent Ineff=
       F       F
Bank Sta=0,5.3
XS Rating Curve= 0
Exp/Cntr=.3,.1

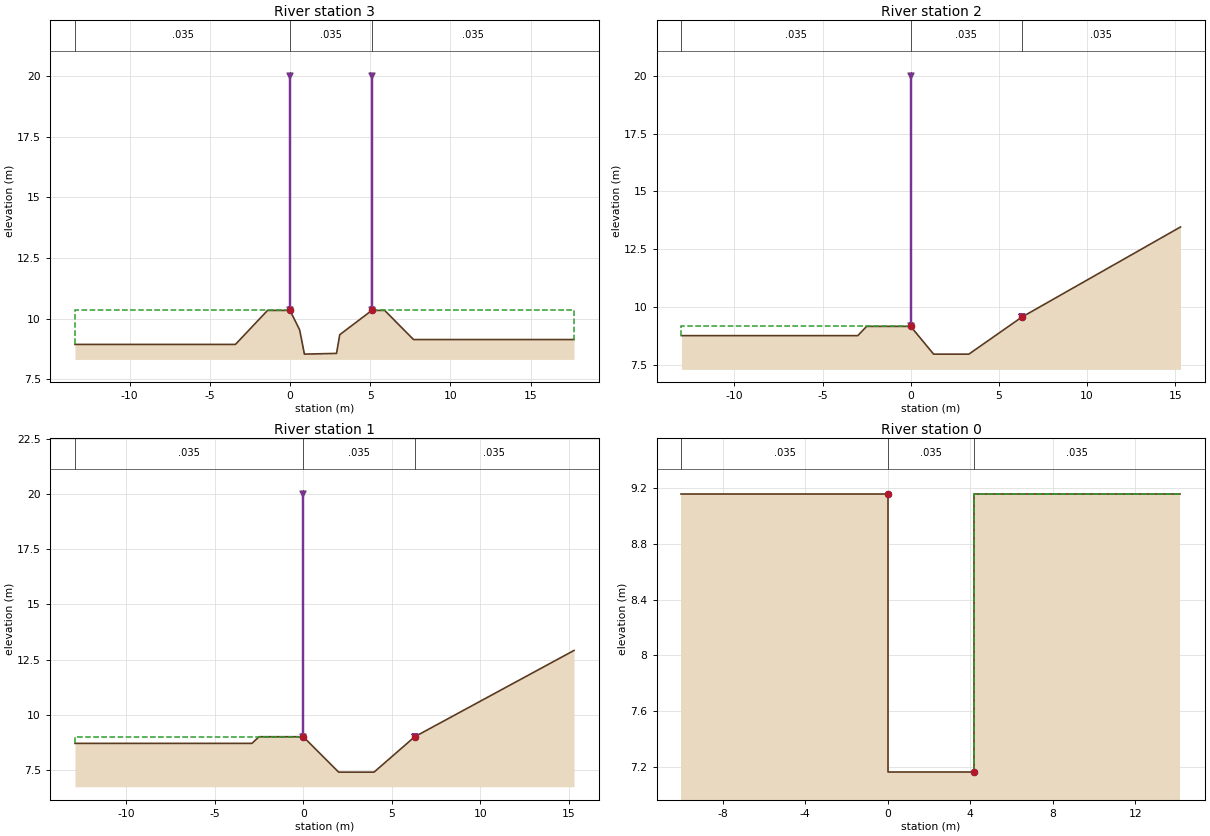
Type RM Length L Ch R = 1 ,3       ,50,50,50
#Sta/Elev= 12
   -13.4    8.94    -3.4    8.94    -1.4   10.34       0   10.34      .6    9.54
      .9    8.54     2.9    8.57     3.1    9.34     5.1   10.34     5.9   10.34
     7.7    9.14    17.7    9.14
#Mann= 3 , 0 , 0
   -13.4    .035       0       0    .035       0     5.1    .035       0
Levee=-1,0,20,-1,5.1,20,,
#XS Ineff= 2 , 0
               0   10.34     5.1           10.34
Permanent Ineff=
       F       F
Bank Sta=0,5.1
XS Rating Curve= 0
Exp/Cntr=.3,.1

Type RM Length L Ch R = 1 ,2       ,50,50,50
#Sta/Elev= 10
     -13    8.76      -3    8.76    -2.5    9.16       0    9.16     1.3    7.96
     3.3    7.96     6.3    9.56     9.3   10.86    12.3   12.16    15.3   13.46
#Mann= 3 , 0 , 0
     -13    .035       0       0    .035       0     6.3    .035       0
Levee=-1,0,20,-1,6.3,9.56,,
#XS Ineff= 2 , 0
               0    9.16     6.3            9.56
Permanent Ineff=
       F       F
Bank Sta=0,6.3
XS Rating Curve= 0
Exp/Cntr=.3,.1

Type RM Length L Ch R = 1 ,1       ,50,50,50
#Sta/Elev= 10
   -12.9    8.72    -2.9    8.72    -2.5    9.02       0    9.02       2    7.42
       4    7.42     6.3    9.02     9.3   10.32    12.3   11.62    15.3   12.92
#Mann= 3 , 0 , 0
   -12.9    .035       0       0    .035       0     6.3    .035       0
Levee=-1,0,20,-1,6.3,9.02,,
#XS Ineff= 2 , 0
               0    9.02     6.3            9.02
Permanent Ineff=
       F       F
Bank Sta=0,6.3
XS Rating Curve= 0
Exp/Cntr=.3,.1

Type RM Length L Ch R = 1 ,0       ,0,0,0
#Sta/Elev= 6
     -10    9.16       0    9.16       0    7.16     4.2    7.16     4.2    9.16
    14.2    9.16
#Mann= 3 , 0 , 0
     -10    .035       0       0    .035       0     4.2    .035       0
#XS Ineff= 2 , 0
               0    9.16     4.2            9.16
Permanent Ineff=
       F       F
Bank Sta=0,4.2
XS Rating Curve= 0
Exp/Cntr=.3,.1

Chan Stop Cuts=-1