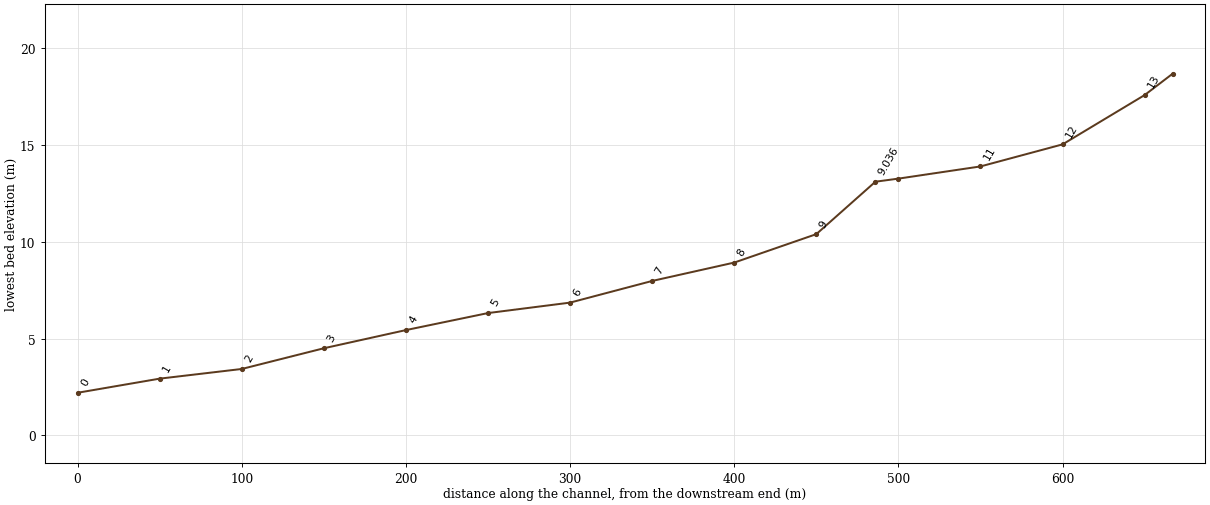
--- KMC.prj (project) ---

Proj Title=koman-ch
Current Plan=p01
Default Exp/Contr=.3,.1
SI Units
Geom File=g01
Flow File=f01
Plan File=p01
Y Axis Title=Elevation
X Axis Title(PF)=Main Channel Distance
X Axis Title(XS)=Station
BEGIN DESCRIPTION:
           BACK WATER COMPUTATION
      APPLICATION OF HEC-2 BY Samju Construction Engineering
      koman-ch: 10,20,30,50,80 yr
END DESCRIPTION:
DSS Export Rating Curves= 0
DSS Export Rating Curve Sorted= 0
DSS Export Volume Flow Curves= 0
DXF OffsetX= 0
DXF OffsetY= 0
DXF ScaleX= 1
DXF ScaleY= 10

--- KMC.p01 (plan) ---

Plan Title=Imported Plan 01
Version=Version 3.0.1  Mar 2001
Short Identifier=Imported Pla
Geom File=g01
Flow File=f01
Subcritical Flow
K Sum by GR= 0
Std Step Tol= 0.003
Critical Tol= 0.003
Num of Std Step Trials= 20
Max Error Tol= 0.1
Flow Tol Ratio= 0.001
Split Flow NTrial= 30
Split Flow Tol= 0.02
Split Flow Ratio= 0.02
Log Output Level= 0
Friction Slope Method= 1
Unsteady Friction Slope Method= 2
Parabolic Critical Depth
Global Vel Dist= 0 , 0 , 0
Global Log Level= 0
CheckData=True
Encroach Param=-1 ,0,0, 0
Computation Interval=1HOUR
Output Interval=1HOUR
Run HTab= 0
Run UNet= 0
Run PostProcess= 0
UNET Theta= 1
UNET ZTol= 0.02
UNET ZSATol= 0.1
UNET MxIter= 20
UNET MaxInSteps= 20
UNET DtIC= 0
UNET DtMin= 0
UNET MaxCRTS= 20
UNET WFStab= 2
UNET SFStab= 1
UNET WFX= 1
UNET SFX= 1
UNET Convert EG Bridges=-1
UNET Use Existing IB Tables=-1
Instantaneous Interval=1HOUR
Write IC File= 0
Write Velocity= 0
Write Detailed= 0

--- KMC.f01 (steady flow) ---

Flow Title=Imported Flow 01
Version=Version 3.0.1  Mar 2001
Number of Profiles= 5
Profile Names=10YR,20YR,30YR,50YR,80YR
River Rch & RM=RIVER-1,Reach-1         ,13.017
   11.08   12.21   12.86   13.69   14.46
River Rch & RM=GOMAN,GOMAN           ,13.017
   11.08   12.21   12.86   13.69   14.46
Boundary for River Rch & Prof#=GOMAN,GOMAN           , 1
Up Type= 0
Dn Type= 3
Dn Slope=.025
Boundary for River Rch & Prof#=GOMAN,GOMAN           , 2
Up Type= 0
Dn Type= 3
Dn Slope=.025
Boundary for River Rch & Prof#=GOMAN,GOMAN           , 3
Up Type= 0
Dn Type= 3
Dn Slope=.025
Boundary for River Rch & Prof#=GOMAN,GOMAN           , 4
Up Type= 0
Dn Type= 3
Dn Slope=.025
Boundary for River Rch & Prof#=GOMAN,GOMAN           , 5
Up Type= 0
Dn Type= 3
Dn Slope=.025
DSS Import GetInterval= 0
DSS Import GetPeak= 0
DSS Import FillOption= 0

--- KMC.g01 (geometry) ---

Geom Title=Imported Geom 01
Version=Version 3.0.1  Mar 2001

River Reach=GOMAN           ,GOMAN
Reach XY= 2
              .5             .95              .5             .05

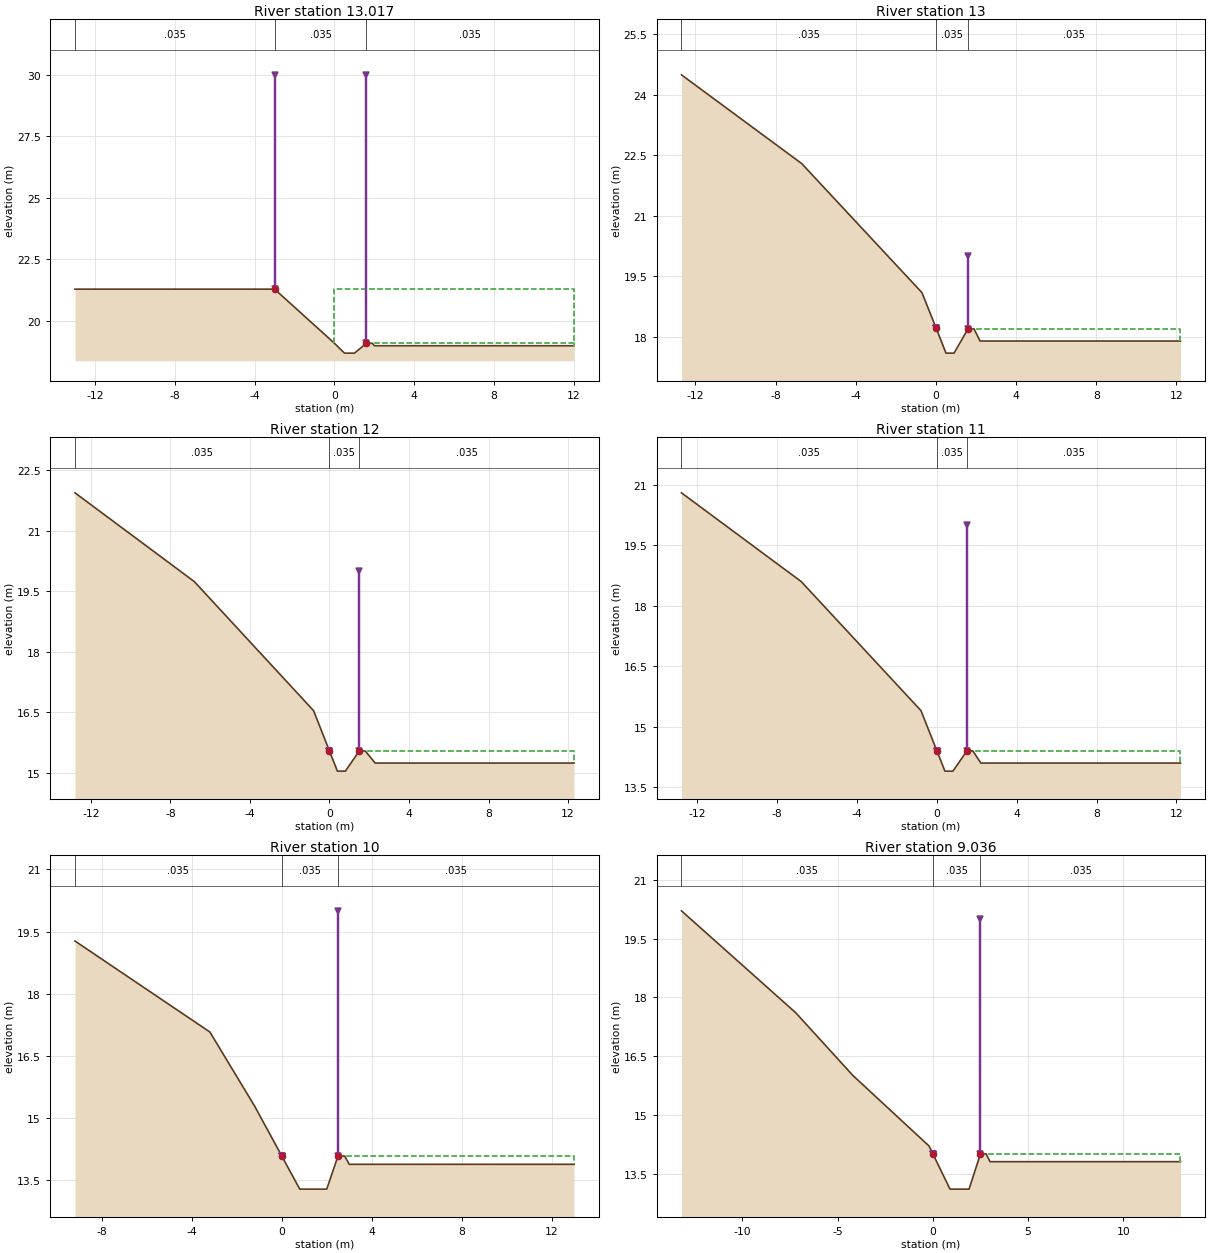
Type RM Length L Ch R = 1 ,13.017  ,17,17,17
#Sta/Elev= 9
     -13   21.29      -3   21.29       0   19.09      .5   18.69       1   18.69
     1.6   19.09     1.9   19.09       2   18.99      12   18.99
#Mann= 3 , 0 , 0
     -13    .035       0      -3    .035       0     1.6    .035       0
Levee=-1,-3,30,-1,1.6,30,,
#XS Ineff= 2 , 0
       0      -3   21.29     1.6       0   19.09
Permanent Ineff=
       F       F
Bank Sta=-3,1.6
XS Rating Curve= 0
Exp/Cntr=.3,.1

Type RM Length L Ch R = 1 ,13      ,50,50,50
#Sta/Elev= 12
   -12.7   24.49    -9.7   23.39    -6.7   22.29    -3.7   20.69     -.7   19.09
       0   18.22      .5   17.59      .9   17.59     1.6   18.19     1.9   18.19
     2.2   17.89    12.2   17.89
#Mann= 3 , 0 , 0
   -12.7    .035       0       0    .035       0     1.6    .035       0
Levee=-1,0,18.22,-1,1.6,20,,
#XS Ineff= 2 , 0
               0   18.22     1.6           18.19
Permanent Ineff=
       F       F
Bank Sta=0,1.6
XS Rating Curve= 0
Exp/Cntr=.3,.1

Type RM Length L Ch R = 1 ,12      ,50,50,50
#Sta/Elev= 12
   -12.8   21.94    -9.8   20.84    -6.8   19.74    -3.8   18.14     -.8   16.54
       0   15.54      .4   15.04      .8   15.04     1.5   15.54     1.8   15.54
     2.3   15.24    12.3   15.24
#Mann= 3 , 0 , 0
   -12.8    .035       0       0    .035       0     1.5    .035       0
Levee=-1,0,15.54,-1,1.5,20,,
#XS Ineff= 2 , 0
               0   15.54     1.5           15.54
Permanent Ineff=
       F       F
Bank Sta=0,1.5
XS Rating Curve= 0
Exp/Cntr=.3,.1

Type RM Length L Ch R = 1 ,11      ,50,50,50
#Sta/Elev= 12
   -12.8    20.8    -9.8    19.7    -6.8    18.6    -3.8      17     -.8    15.4
       0    14.4      .4    13.9      .8    13.9     1.5    14.4     1.8    14.4
     2.2    14.1    12.2    14.1
#Mann= 3 , 0 , 0
   -12.8    .035       0       0    .035       0     1.5    .035       0
Levee=-1,0,14.4,-1,1.5,20,,
#XS Ineff= 2 , 0
               0    14.4     1.5            14.4
Permanent Ineff=
       F       F
Bank Sta=0,1.5
XS Rating Curve= 0
Exp/Cntr=.3,.1

Type RM Length L Ch R = 1 ,10      ,14,14,14
#Sta/Elev= 11
    -9.2   19.27    -6.2   18.17    -3.2   17.07    -1.2   15.27       0   14.07
      .8   13.27       2   13.27     2.5   14.07     2.8   14.07       3   13.87
      13   13.87
#Mann= 3 , 0 , 0
    -9.2    .035       0       0    .035       0     2.5    .035       0
Levee=-1,0,14.07,-1,2.5,20,,
#XS Ineff= 2 , 0
               0   14.07     2.5           14.07
Permanent Ineff=
       F       F
Bank Sta=0,2.5
XS Rating Curve= 0
Exp/Cntr=.3,.1

Type RM Length L Ch R = 1 ,9.036   ,36,36,36
#Sta/Elev= 13
   -13.2   20.21   -10.2   18.91    -7.2   17.61    -4.2   16.01    -2.2   15.11
     -.2   14.21       0   14.01      .9   13.11     1.9   13.11     2.5   14.01
     2.8   14.01       3   13.81      13   13.81
#Mann= 3 , 0 , 0
   -13.2    .035       0       0    .035       0     2.5    .035       0
Levee=-1,0,14.01,-1,2.5,20,,
#XS Ineff= 2 , 0
               0   14.01     2.5           14.01
Permanent Ineff=
       F       F
Bank Sta=0,2.5
XS Rating Curve= 0
Exp/Cntr=.3,.1

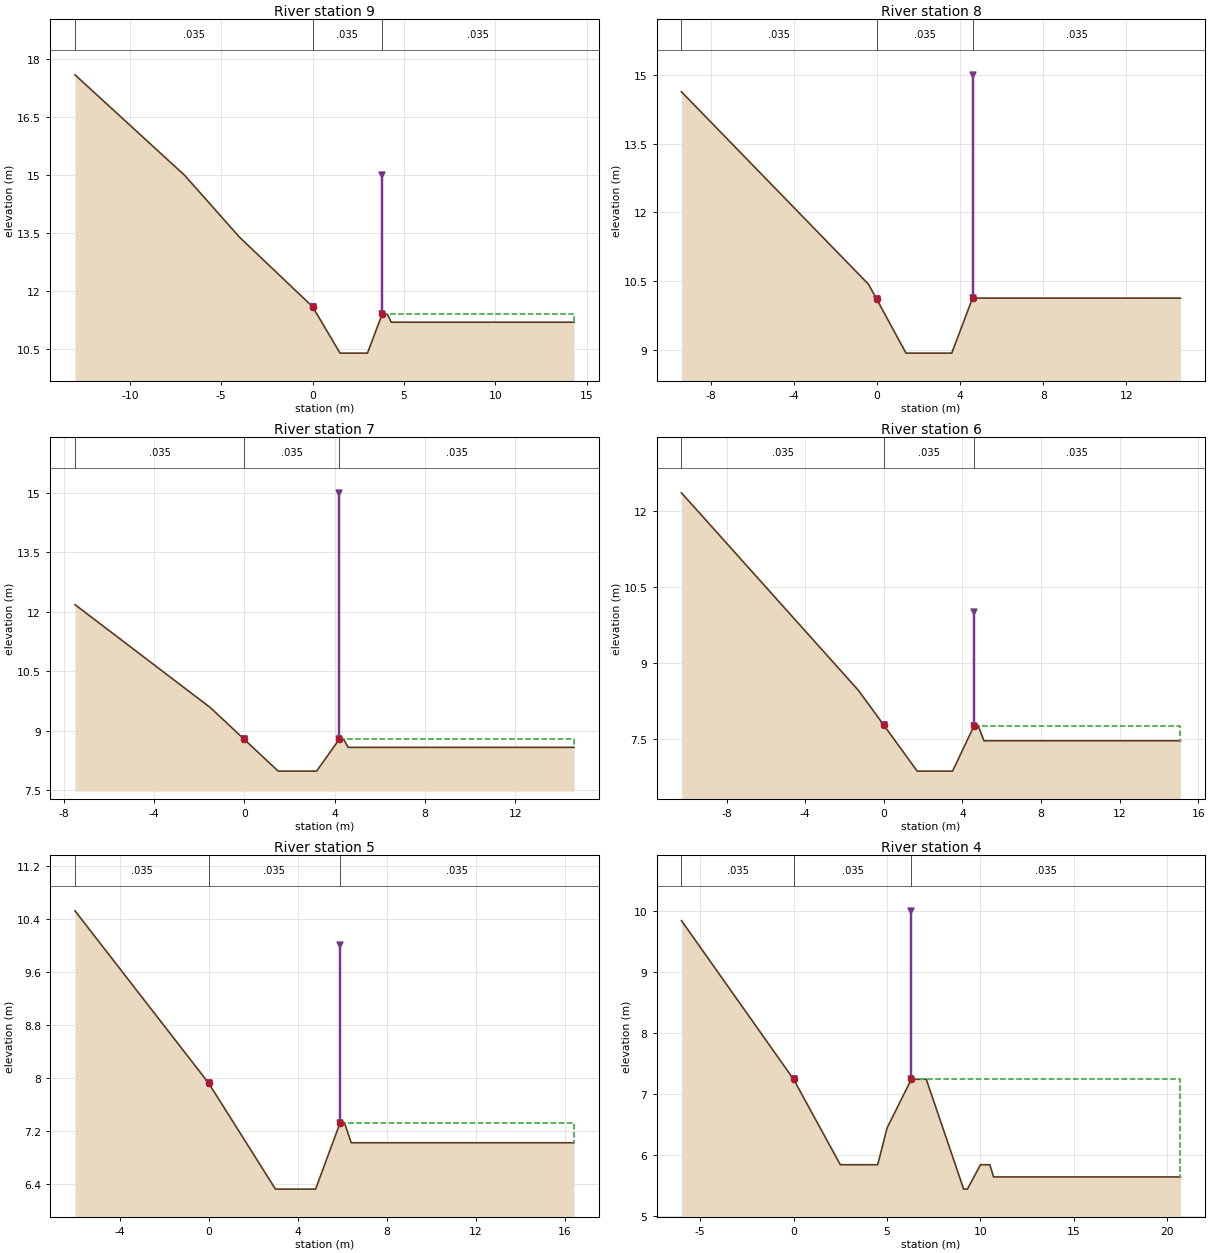
Type RM Length L Ch R = 1 ,9       ,50,50,50
#Sta/Elev= 12
     -13    17.6     -10    16.3      -7      15      -4    13.4      -2    12.5
       0    11.6     1.5    10.4       3    10.4     3.8    11.4     4.1    11.4
     4.3    11.2    14.3    11.2
#Mann= 3 , 0 , 0
     -13    .035       0       0    .035       0     3.8    .035       0
Levee=-1,0,11.6,-1,3.8,15,,
#XS Ineff= 2 , 0
               0    11.6     3.8            11.4
Permanent Ineff=
       F       F
Bank Sta=0,3.8
XS Rating Curve= 0
Exp/Cntr=.3,.1

Type RM Length L Ch R = 1 ,8       ,50,50,50
#Sta/Elev= 9
    -9.4   14.63    -6.4   13.23    -3.4   11.83     -.4   10.43       0    10.1
     1.4    8.93     3.6    8.93     4.6   10.13    14.6   10.13
#Mann= 3 , 0 , 0
    -9.4    .035       0       0    .035       0     4.6    .035       0
Levee=-1,0,10.1,-1,4.6,15,,
#XS Ineff= 2 , 0
               0    10.1     4.6           10.13
Permanent Ineff=
       F       F
Bank Sta=0,4.6
XS Rating Curve= 0
Exp/Cntr=.3,.1

Type RM Length L Ch R = 1 ,7       ,50,50,50
#Sta/Elev= 10
    -7.5   12.18    -4.5   10.88    -1.5    9.58       0    8.78     1.5    7.98
     3.2    7.98     4.2    8.78     4.4    8.78     4.6    8.58    14.6    8.58
#Mann= 3 , 0 , 0
    -7.5    .035       0       0    .035       0     4.2    .035       0
Levee=-1,0,8.78,-1,4.2,15,,
#XS Ineff= 2 , 0
               0    8.78     4.2            8.78
Permanent Ineff=
       F       F
Bank Sta=0,4.2
XS Rating Curve= 0
Exp/Cntr=.3,.1

Type RM Length L Ch R = 1 ,6       ,50,50,50
#Sta/Elev= 11
   -10.3   12.36    -7.3   11.06    -4.3    9.76    -1.3    8.46       0    7.77
     1.7    6.86     3.5    6.86     4.6    7.76     4.8    7.76     5.1    7.46
    15.1    7.46
#Mann= 3 , 0 , 0
   -10.3    .035       0       0    .035       0     4.6    .035       0
Levee=-1,0,7.77,-1,4.6,10,,
#XS Ineff= 2 , 0
               0    7.77     4.6            7.76
Permanent Ineff=
       F       F
Bank Sta=0,4.6
XS Rating Curve= 0
Exp/Cntr=.3,.1

Type RM Length L Ch R = 1 ,5       ,50,50,50
#Sta/Elev= 9
      -6   10.52      -3    9.22       0    7.92       3    6.32     4.8    6.32
     5.9    7.32     6.1    7.32     6.4    7.02    16.4    7.02
#Mann= 3 , 0 , 0
      -6    .035       0       0    .035       0     5.9    .035       0
Levee=-1,0,7.92,-1,5.9,10,,
#XS Ineff= 2 , 0
               0    7.92     5.9            7.32
Permanent Ineff=
       F       F
Bank Sta=0,5.9
XS Rating Curve= 0
Exp/Cntr=.3,.1

Type RM Length L Ch R = 1 ,4       ,50,50,50
#Sta/Elev= 14
      -6    9.84      -3    8.54       0    7.24     2.5    5.84     4.5    5.84
       5    6.44     6.3    7.24     7.1    7.24     9.1    5.44     9.3    5.44
      10    5.84    10.5    5.84    10.7    5.64    20.7    5.64
#Mann= 3 , 0 , 0
      -6    .035       0       0    .035       0     6.3    .035       0
Levee=-1,0,7.24,-1,6.3,10,,
#XS Ineff= 2 , 0
               0    7.24     6.3            7.24
Permanent Ineff=
       F       F
Bank Sta=0,6.3
XS Rating Curve= 0
Exp/Cntr=.3,.1

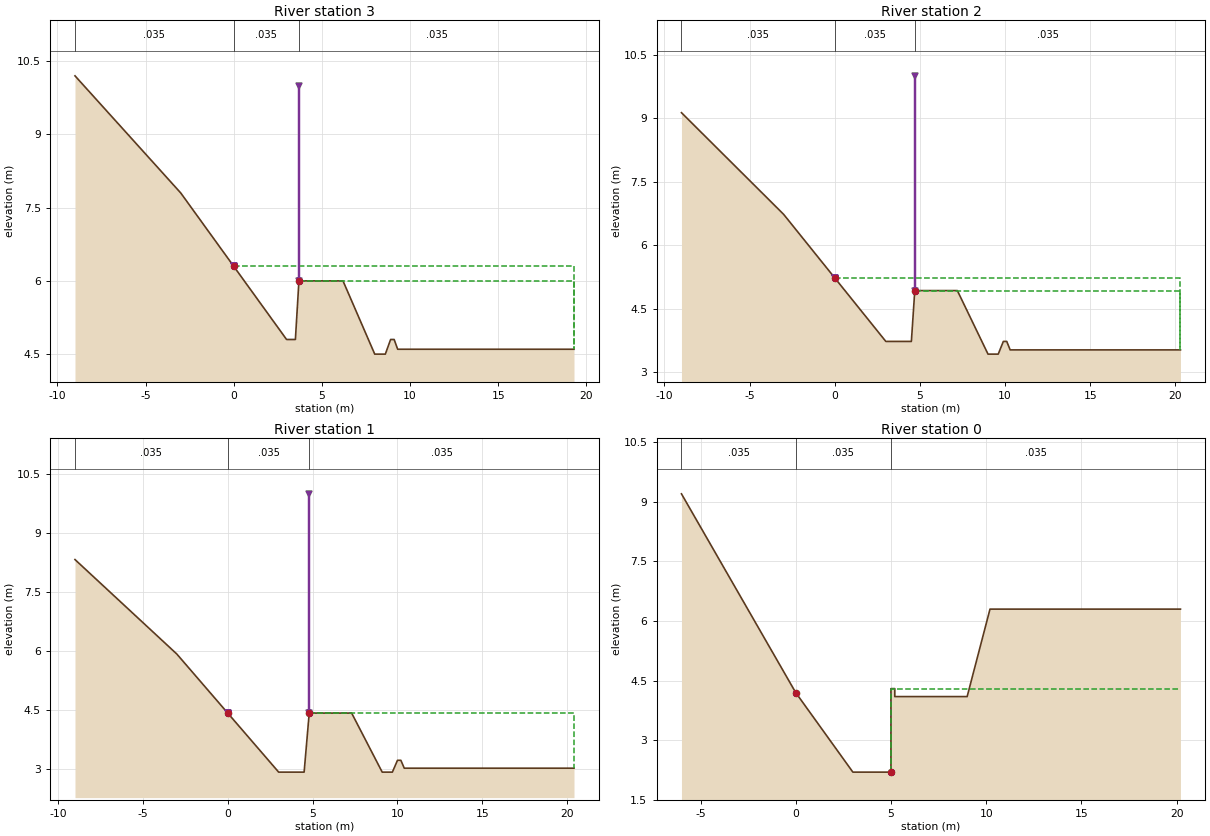
Type RM Length L Ch R = 1 ,3       ,50,50,50
#Sta/Elev= 14
      -9    10.2      -6       9      -3     7.8       0     6.3       3     4.8
     3.5     4.8     3.7       6     6.2       6       8     4.5     8.6     4.5
     8.9     4.8     9.1     4.8     9.3     4.6    19.3     4.6
#Mann= 3 , 0 , 0
      -9    .035       0       0    .035       0     3.7    .035       0
Levee=-1,0,6.3,-1,3.7,10,,
#XS Ineff= 2 , 0
       0       0     6.3     3.7       0       6
Permanent Ineff=
       F       F
Bank Sta=0,3.7
XS Rating Curve= 0
Exp/Cntr=.3,.1

Type RM Length L Ch R = 1 ,2       ,50,50,50
#Sta/Elev= 14
      -9    9.13      -6    7.93      -3    6.73       0    5.23       3    3.73
     4.5    3.73     4.7    4.93     7.2    4.93       9    3.43     9.6    3.43
     9.9    3.73    10.1    3.73    10.3    3.53    20.3    3.53
#Mann= 3 , 0 , 0
      -9    .035       0       0    .035       0     4.7    .035       0
Levee=-1,0,5.23,-1,4.7,10,,
#XS Ineff= 2 , 0
       0       0    5.23     4.7       0    4.93
Permanent Ineff=
       F       F
Bank Sta=0,4.7
XS Rating Curve= 0
Exp/Cntr=.3,.1

Type RM Length L Ch R = 1 ,1       ,50,50,50
#Sta/Elev= 14
      -9    8.33      -6    7.13      -3    5.93       0    4.43       3    2.93
     4.5    2.93     4.8    4.43     7.3    4.43     9.1    2.93     9.7    2.93
      10    3.23    10.2    3.23    10.4    3.03    20.4    3.03
#Mann= 3 , 0 , 0
      -9    .035       0       0    .035       0     4.8    .035       0
Levee=-1,0,4.43,-1,4.8,10,,
#XS Ineff= 2 , 0
               0    4.43     4.8            4.43
Permanent Ineff=
       F       F
Bank Sta=0,4.8
XS Rating Curve= 0
Exp/Cntr=.3,.1

Type RM Length L Ch R = 1 ,0       ,0,0,0
#Sta/Elev= 11
      -6     9.2      -3     6.7       0     4.2       3     2.2       5     2.2
       5     4.3     5.2     4.3     5.2     4.1       9     4.1    10.2     6.3
    20.2     6.3
#Mann= 3 , 0 , 0
      -6    .035       0       0    .035       0       5    .035       0
#XS Ineff= 2 , 0
               0     4.2       5             4.3
Permanent Ineff=
       F       F
Bank Sta=0,5
XS Rating Curve= 0
Exp/Cntr=.3,.1

Chan Stop Cuts=-1