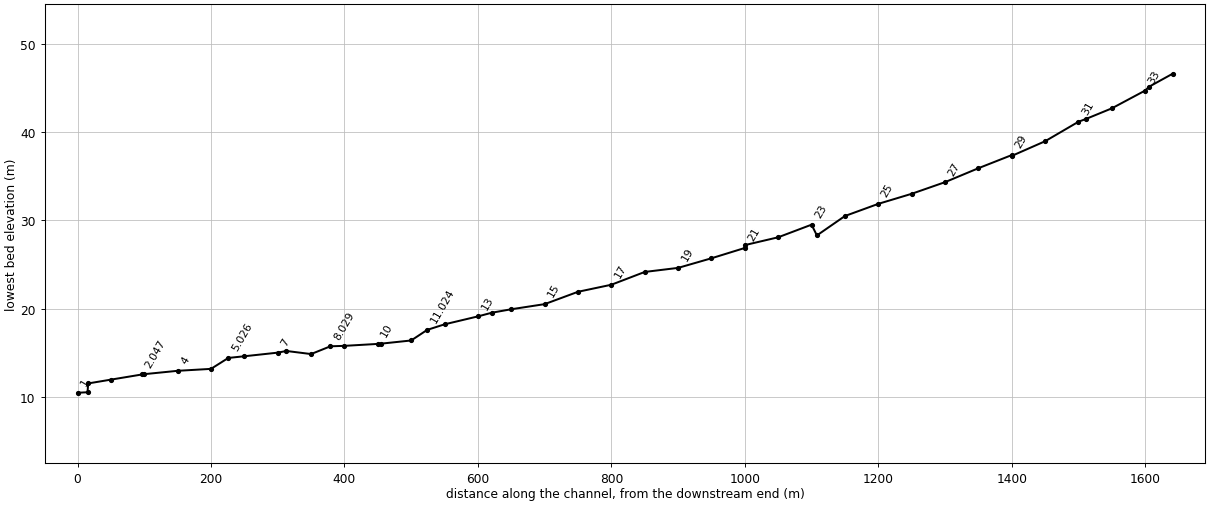
--- SDC.prj (project) ---

Proj Title=sadong-ch
Current Plan=p01
Default Exp/Contr=.3,.1
SI Units
Geom File=g01
Flow File=f01
Plan File=p01
Y Axis Title=Elevation
X Axis Title(PF)=Main Channel Distance
X Axis Title(XS)=Station
BEGIN DESCRIPTION:
           BACK WATER COMPUTATION
      APPLICATION OF HEC-2 BY Samju Construction Engineering
      sadong-ch: 10,20,30,50,80 yr
END DESCRIPTION:
DSS Export Rating Curves= 0
DSS Export Rating Curve Sorted= 0
DSS Export Volume Flow Curves= 0
DXF OffsetX= 0
DXF OffsetY= 0
DXF ScaleX= 1
DXF ScaleY= 10

--- SDC.p01 (plan) ---

Plan Title=Imported Plan 01
Version=Version 3.0.1  Mar 2001
Short Identifier=Imported Pla
Geom File=g01
Flow File=f01
Subcritical Flow
K Sum by GR= 0
Std Step Tol= 0.01
Critical Tol= 0.01
Num of Std Step Trials= 20
Max Error Tol= 0.3
Flow Tol Ratio= 0.001
Split Flow NTrial= 30
Split Flow Tol= 0.02
Split Flow Ratio= 0.02
Log Output Level= 0
Friction Slope Method= 1
Unsteady Friction Slope Method= 2
Parabolic Critical Depth
Global Vel Dist= 0 , 0 , 0
Global Log Level= 0
CheckData=True
Encroach Param=-1 ,0,0, 0
Computation Interval=1HOUR
Output Interval=1HOUR
Run HTab= 0
Run UNet= 0
Run PostProcess= 0
UNET Theta= 1
UNET ZTol= 0.02
UNET ZSATol= 0.1
UNET MxIter= 20
UNET MaxInSteps= 20
UNET DtIC= 0
UNET DtMin= 0
UNET MaxCRTS= 20
UNET WFStab= 2
UNET SFStab= 1
UNET WFX= 1
UNET SFX= 1
UNET Convert EG Bridges=-1
UNET Use Existing IB Tables=-1
Instantaneous Interval=1HOUR
Write IC File= 0
Write Velocity= 0
Write Detailed= 0

--- SDC.f01 (steady flow) ---

Flow Title=Imported Flow 01
Version=Version 3.0.1  Mar 2001
Number of Profiles= 5
Profile Names=10YR,20YR,30YR,50YR,80YR
River Rch & RM=RIVER-1,Reach-1         ,33.041
   17.86   19.69   20.76   22.11   23.36
River Rch & RM=SADONG,SADONG          ,33.041
   17.86   19.69   20.76   22.11   23.36
Boundary for River Rch & Prof#=SADONG,SADONG          , 1
Up Type= 0
Dn Type= 3
Dn Slope=.022
Boundary for River Rch & Prof#=SADONG,SADONG          , 2
Up Type= 0
Dn Type= 3
Dn Slope=.022
Boundary for River Rch & Prof#=SADONG,SADONG          , 3
Up Type= 0
Dn Type= 3
Dn Slope=.022
Boundary for River Rch & Prof#=SADONG,SADONG          , 4
Up Type= 0
Dn Type= 3
Dn Slope=.022
Boundary for River Rch & Prof#=SADONG,SADONG          , 5
Up Type= 0
Dn Type= 3
Dn Slope=.022
DSS Import GetInterval= 0
DSS Import GetPeak= 0
DSS Import FillOption= 0

--- SDC.g01 (geometry) ---

Geom Title=Imported Geom 01
Version=Version 3.0.1  Mar 2001

River Reach=SADONG          ,SADONG
Reach XY= 2
              .5             .95              .5             .05

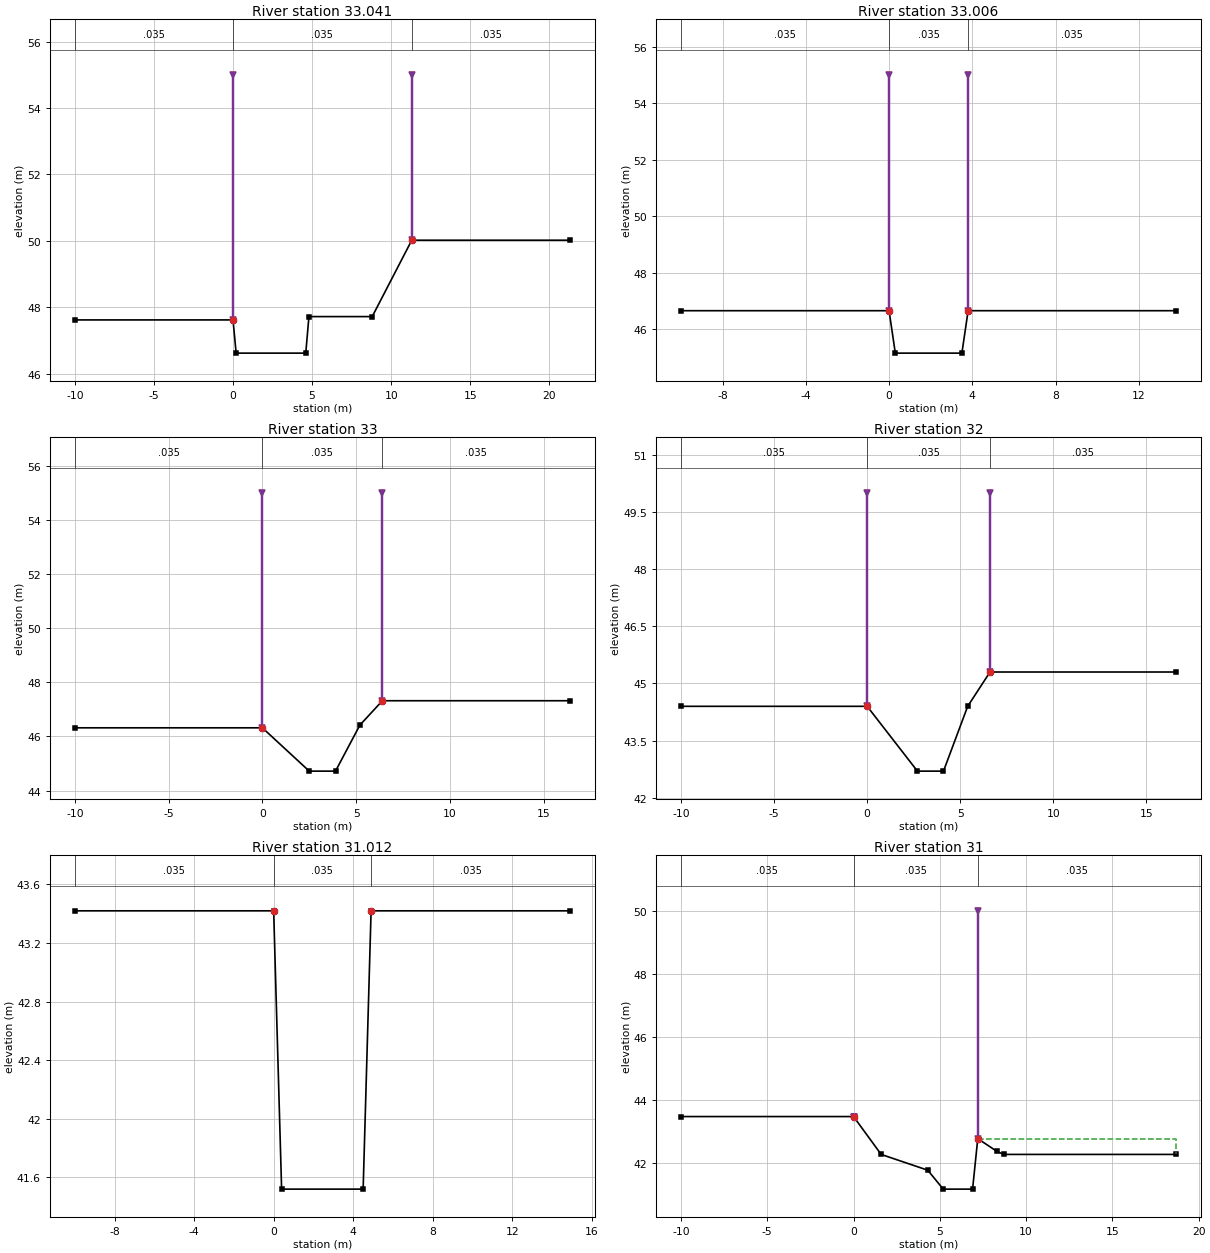
Type RM Length L Ch R = 1 ,33.041  ,35,35,35
#Sta/Elev= 8
     -10   47.62       0   47.62      .2   46.62     4.6   46.62     4.8   47.72
     8.8   47.72    11.3   50.02    21.3   50.02
#Mann= 3 , 0 , 0
     -10    .035       0       0    .035       0    11.3    .035       0
Levee=-1,0,55,-1,11.3,55,,
#XS Ineff= 2 , 0
               0   47.62    11.3           50.02
Permanent Ineff=
       F       F
Bank Sta=0,11.3
XS Rating Curve= 0
Exp/Cntr=.3,.1

Type RM Length L Ch R = 1 ,33.006  ,6,6,6
#Sta/Elev= 6
     -10   46.66       0   46.66      .3   45.16     3.5   45.16     3.8   46.66
    13.8   46.66
#Mann= 3 , 0 , 0
     -10    .035       0       0    .035       0     3.8    .035       0
Levee=-1,0,55,-1,3.8,55,,
#XS Ineff= 2 , 0
               0   46.66     3.8           46.66
Permanent Ineff=
       F       F
Bank Sta=0,3.8
XS Rating Curve= 0
Exp/Cntr=.3,.1

Type RM Length L Ch R = 1 ,33      ,50,50,50
#Sta/Elev= 7
     -10   46.32       0   46.32     2.5   44.72     3.9   44.72     5.2   46.42
     6.4   47.32    16.4   47.32
#Mann= 3 , 0 , 0
     -10    .035       0       0    .035       0     6.4    .035       0
Levee=-1,0,55,-1,6.4,55,,
#XS Ineff= 2 , 0
               0   46.32     6.4           47.32
Permanent Ineff=
       F       F
Bank Sta=0,6.4
XS Rating Curve= 0
Exp/Cntr=.3,.1

Type RM Length L Ch R = 1 ,32      ,38,38,38
#Sta/Elev= 7
     -10    44.4       0    44.4     2.7    42.7     4.1    42.7     5.4    44.4
     6.6    45.3    16.6    45.3
#Mann= 3 , 0 , 0
     -10    .035       0       0    .035       0     6.6    .035       0
Levee=-1,0,50,-1,6.6,50,,
#XS Ineff= 2 , 0
               0    44.4     6.6            45.3
Permanent Ineff=
       F       F
Bank Sta=0,6.6
XS Rating Curve= 0
Exp/Cntr=.3,.1

Type RM Length L Ch R = 1 ,31.012  ,12,12,12
#Sta/Elev= 6
     -10   43.42       0   43.42      .4   41.52     4.5   41.52     4.9   43.42
    14.9   43.42
#Mann= 3 , 0 , 0
     -10    .035       0       0    .035       0     4.9    .035       0
#XS Ineff= 2 , 0
               0   43.42     4.9           43.42
Permanent Ineff=
       F       F
Bank Sta=0,4.9
XS Rating Curve= 0
Exp/Cntr=.3,.1

Type RM Length L Ch R = 1 ,31      ,50,50,50
#Sta/Elev= 10
     -10   43.48       0   43.48     1.6   42.28     4.3   41.78     5.2   41.18
     6.9   41.18     7.2   42.78     8.3   42.38     8.7   42.28    18.7   42.28
#Mann= 3 , 0 , 0
     -10    .035       0       0    .035       0     7.2    .035       0
Levee=-1,0,43.48,-1,7.2,50,,
#XS Ineff= 2 , 0
               0   43.48     7.2           42.78
Permanent Ineff=
       F       F
Bank Sta=0,7.2
XS Rating Curve= 0
Exp/Cntr=.3,.1

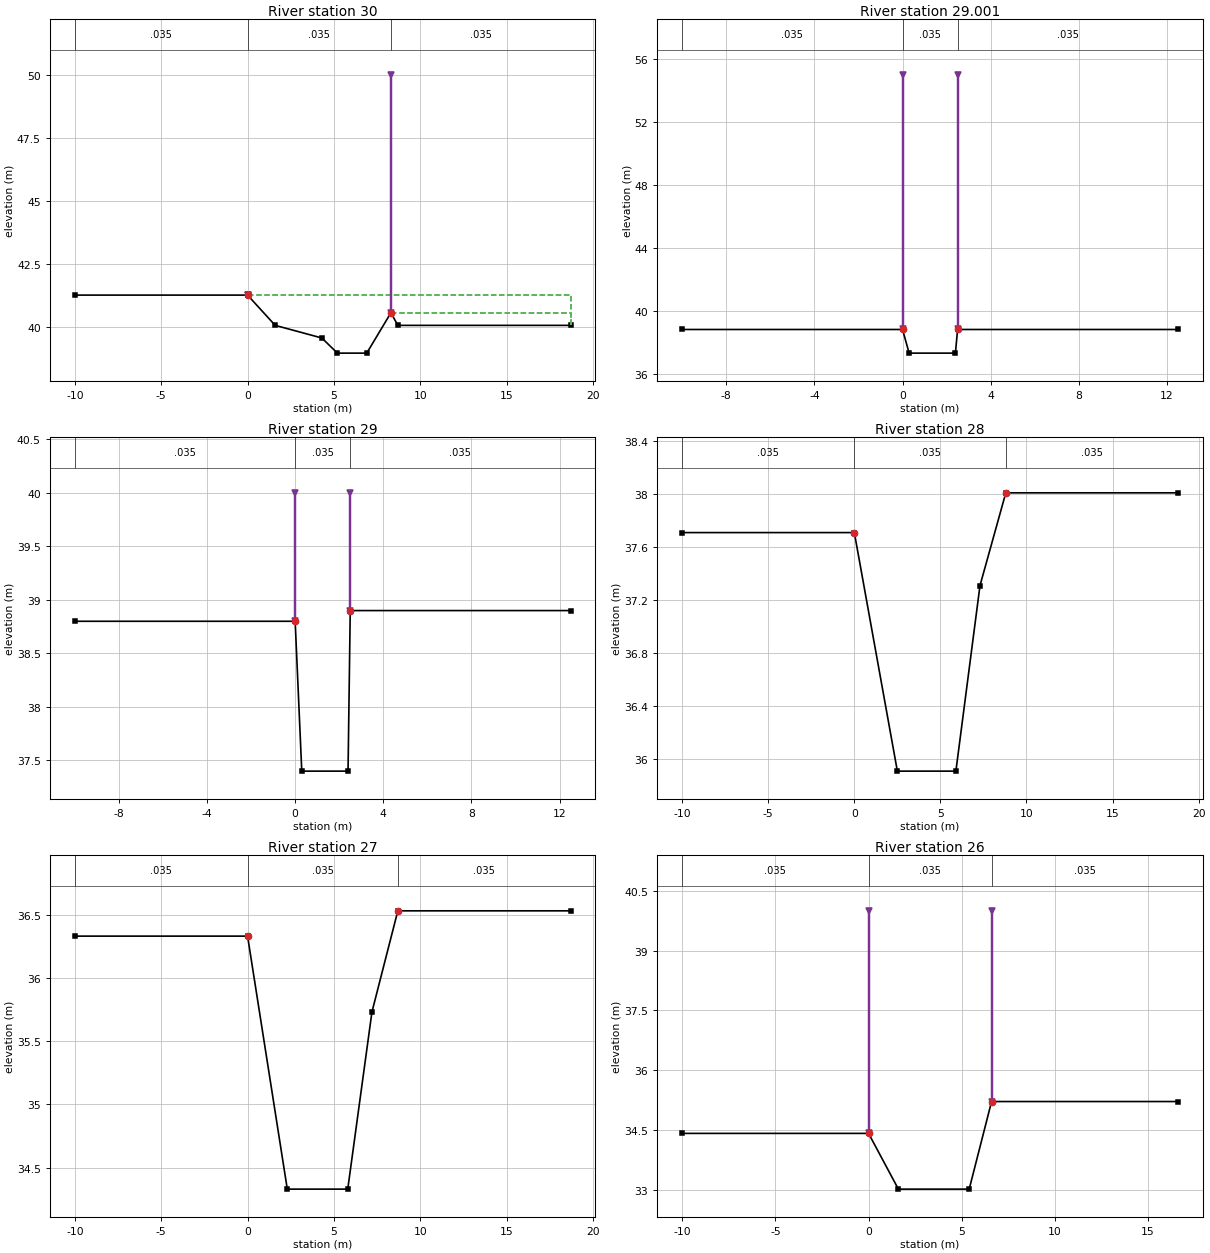
Type RM Length L Ch R = 1 ,30      ,49,49,49
#Sta/Elev= 9
     -10   41.27       0   41.27     1.6   40.07     4.3   39.57     5.2   38.97
     6.9   38.97     8.3   40.57     8.7   40.07    18.7   40.07
#Mann= 3 , 0 , 0
     -10    .035       0       0    .035       0     8.3    .035       0
Levee=-1,0,41.27,-1,8.3,50,,
#XS Ineff= 2 , 0
       0       0   41.27     8.3       0   40.57
Permanent Ineff=
       F       F
Bank Sta=0,8.3
XS Rating Curve= 0
Exp/Cntr=.3,.1

Type RM Length L Ch R = 1 ,29.001  ,1,1,1
#Sta/Elev= 6
     -10   38.84       0   38.84      .3   37.34     2.4   37.34     2.5   38.84
    12.5   38.84
#Mann= 3 , 0 , 0
     -10    .035       0       0    .035       0     2.5    .035       0
Levee=-1,0,55,-1,2.5,55,,
#XS Ineff= 2 , 0
               0   38.84     2.5           38.84
Permanent Ineff=
       F       F
Bank Sta=0,2.5
XS Rating Curve= 0
Exp/Cntr=.3,.1

Type RM Length L Ch R = 1 ,29      ,50,50,50
#Sta/Elev= 6
     -10    38.8       0    38.8      .3    37.4     2.4    37.4     2.5    38.9
    12.5    38.9
#Mann= 3 , 0 , 0
     -10    .035       0       0    .035       0     2.5    .035       0
Levee=-1,0,40,-1,2.5,40,,
#XS Ineff= 2 , 0
               0    38.8     2.5            38.9
Permanent Ineff=
       F       F
Bank Sta=0,2.5
XS Rating Curve= 0
Exp/Cntr=.3,.1

Type RM Length L Ch R = 1 ,28      ,50,50,50
#Sta/Elev= 7
     -10   37.71       0   37.71     2.5   35.91     5.9   35.91     7.3   37.31
     8.8   38.01    18.8   38.01
#Mann= 3 , 0 , 0
     -10    .035       0       0    .035       0     8.8    .035       0
#XS Ineff= 2 , 0
               0   37.71     8.8           38.01
Permanent Ineff=
       F       F
Bank Sta=0,8.8
XS Rating Curve= 0
Exp/Cntr=.3,.1

Type RM Length L Ch R = 1 ,27      ,50,50,50
#Sta/Elev= 7
     -10   36.33       0   36.33     2.3   34.33     5.8   34.33     7.2   35.73
     8.7   36.53    18.7   36.53
#Mann= 3 , 0 , 0
     -10    .035       0       0    .035       0     8.7    .035       0
#XS Ineff= 2 , 0
               0   36.33     8.7           36.53
Permanent Ineff=
       F       F
Bank Sta=0,8.7
XS Rating Curve= 0
Exp/Cntr=.3,.1

Type RM Length L Ch R = 1 ,26      ,50,50,50
#Sta/Elev= 6
     -10   34.41       0   34.41     1.6   33.01     5.4   33.01     6.6   35.21
    16.6   35.21
#Mann= 3 , 0 , 0
     -10    .035       0       0    .035       0     6.6    .035       0
Levee=-1,0,40,-1,6.6,40,,
#XS Ineff= 2 , 0
               0   34.41     6.6           35.21
Permanent Ineff=
       F       F
Bank Sta=0,6.6
XS Rating Curve= 0
Exp/Cntr=.3,.1

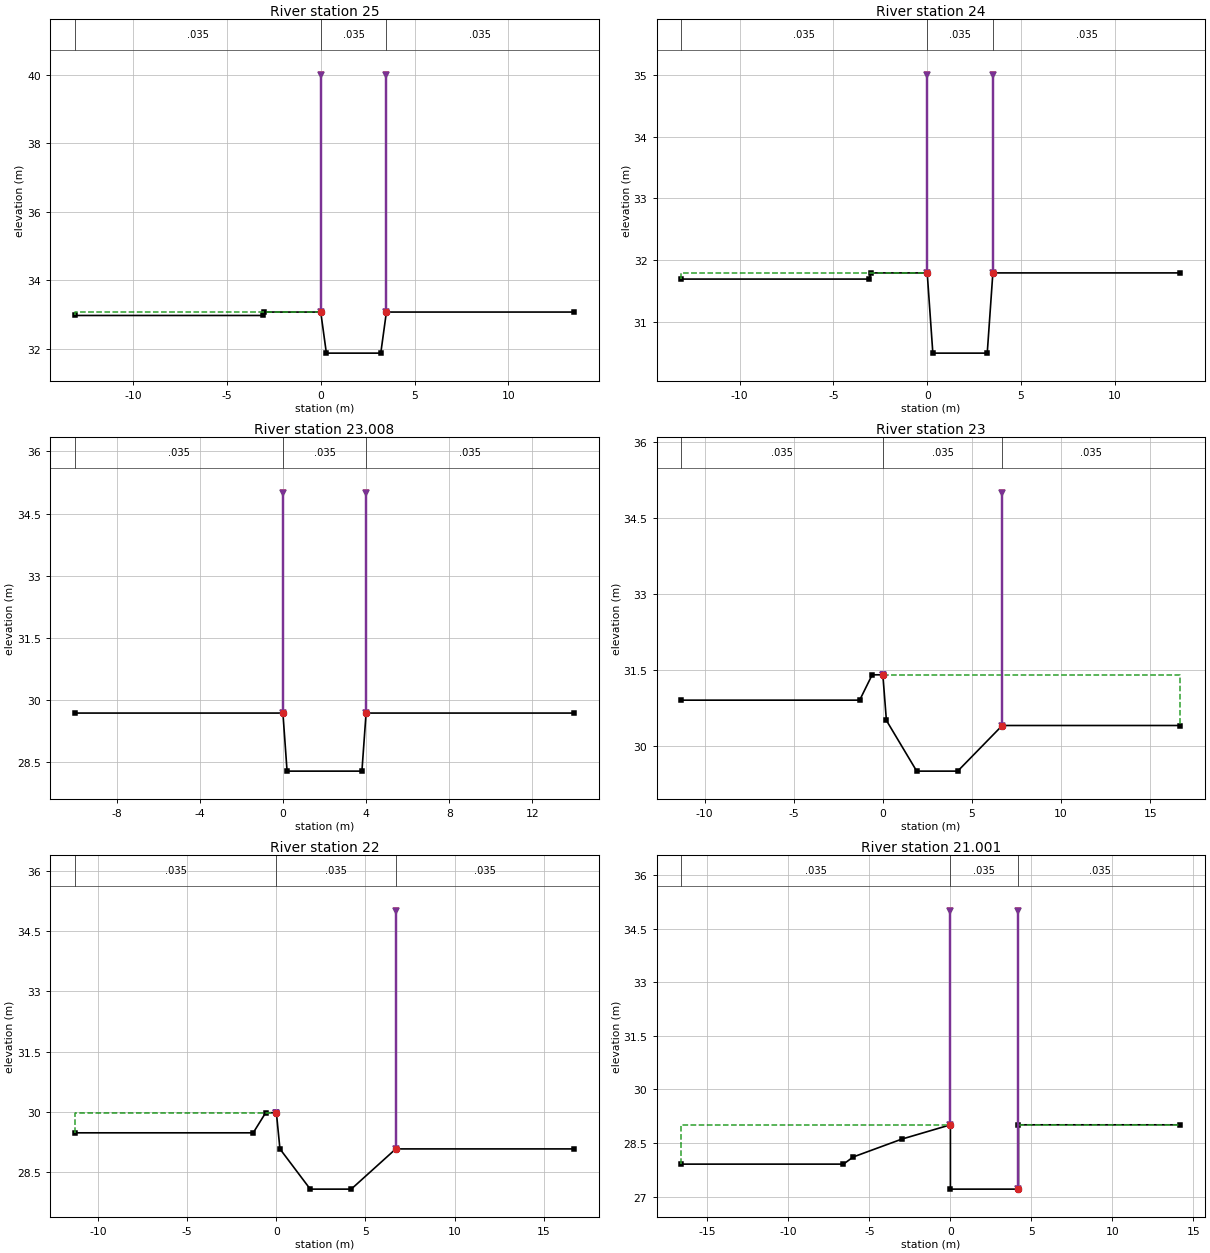
Type RM Length L Ch R = 1 ,25      ,50,50,50
#Sta/Elev= 8
   -13.1   32.97    -3.1   32.97      -3   33.07       0   33.07      .3   31.87
     3.2   31.87     3.5   33.07    13.5   33.07
#Mann= 3 , 0 , 0
   -13.1    .035       0       0    .035       0     3.5    .035       0
Levee=-1,0,40,-1,3.5,40,,
#XS Ineff= 2 , 0
               0   33.07     3.5           33.07
Permanent Ineff=
       F       F
Bank Sta=0,3.5
XS Rating Curve= 0
Exp/Cntr=.3,.1

Type RM Length L Ch R = 1 ,24      ,42,42,42
#Sta/Elev= 8
   -13.1   31.69    -3.1   31.69      -3   31.79       0   31.79      .3   30.49
     3.2   30.49     3.5   31.79    13.5   31.79
#Mann= 3 , 0 , 0
   -13.1    .035       0       0    .035       0     3.5    .035       0
Levee=-1,0,35,-1,3.5,35,,
#XS Ineff= 2 , 0
               0   31.79     3.5           31.79
Permanent Ineff=
       F       F
Bank Sta=0,3.5
XS Rating Curve= 0
Exp/Cntr=.3,.1

Type RM Length L Ch R = 1 ,23.008  ,8,8,8
#Sta/Elev= 6
     -10   29.69       0   29.69      .2   28.29     3.8   28.29       4   29.69
      14   29.69
#Mann= 3 , 0 , 0
     -10    .035       0       0    .035       0       4    .035       0
Levee=-1,0,35,-1,4,35,,
#XS Ineff= 2 , 0
               0   29.69       4           29.69
Permanent Ineff=
       F       F
Bank Sta=0,4
XS Rating Curve= 0
Exp/Cntr=.3,.1

Type RM Length L Ch R = 1 ,23      ,50,50,50
#Sta/Elev= 9
   -11.3   30.91    -1.3   30.91     -.6   31.41       0   31.41      .2   30.51
     1.9   29.51     4.2   29.51     6.7   30.41    16.7   30.41
#Mann= 3 , 0 , 0
   -11.3    .035       0       0    .035       0     6.7    .035       0
Levee=-1,0,31.41,-1,6.7,35,,
#XS Ineff= 2 , 0
       0       0   31.41     6.7       0   30.41
Permanent Ineff=
       F       F
Bank Sta=0,6.7
XS Rating Curve= 0
Exp/Cntr=.3,.1

Type RM Length L Ch R = 1 ,22      ,49,49,49
#Sta/Elev= 9
   -11.3   29.48    -1.3   29.48     -.6   29.98       0   29.98      .2   29.08
     1.9   28.08     4.2   28.08     6.7   29.08    16.7   29.08
#Mann= 3 , 0 , 0
   -11.3    .035       0       0    .035       0     6.7    .035       0
Levee=-1,0,29.98,-1,6.7,35,,
#XS Ineff= 2 , 0
               0   29.98     6.7           29.08
Permanent Ineff=
       F       F
Bank Sta=0,6.7
XS Rating Curve= 0
Exp/Cntr=.3,.1

Type RM Length L Ch R = 1 ,21.001  ,1,1,1
#Sta/Elev= 9
   -16.6   27.91    -6.6   27.91      -6   28.11      -3   28.61       0   29.01
       0   27.21     4.2   27.21     4.2   29.01    14.2   29.01
#Mann= 3 , 0 , 0
   -16.6    .035       0       0    .035       0     4.2    .035       0
Levee=-1,0,35,-1,4.2,35,,
#XS Ineff= 2 , 0
               0   29.01     4.2           29.01
Permanent Ineff=
       F       F
Bank Sta=0,4.2
XS Rating Curve= 0
Exp/Cntr=.3,.1

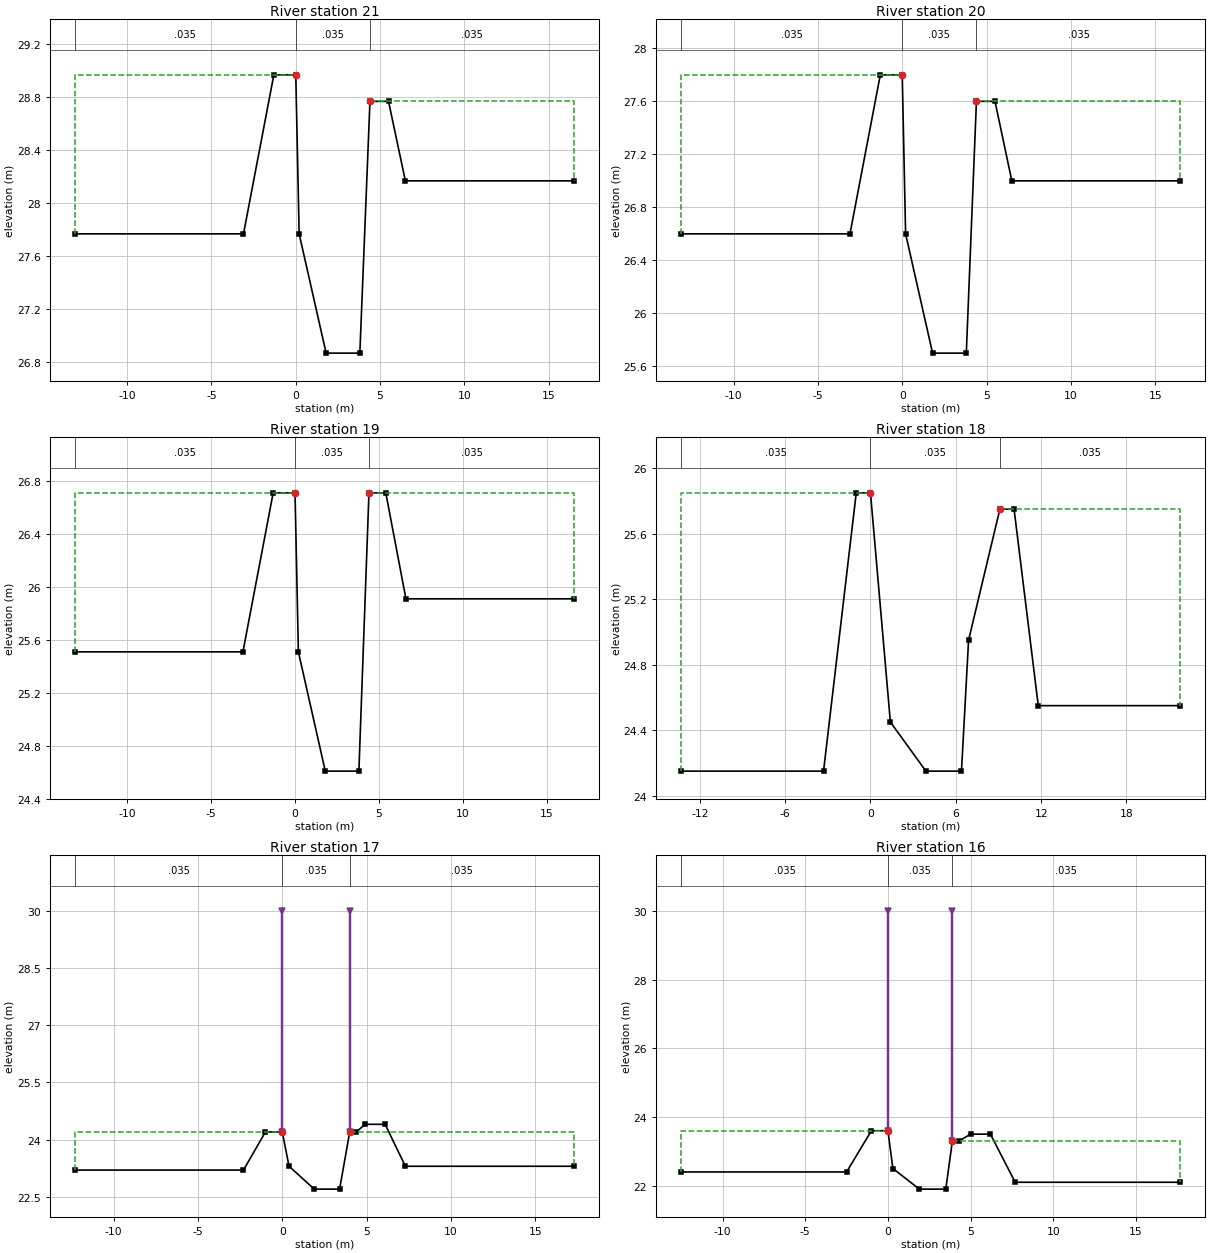
Type RM Length L Ch R = 1 ,21      ,50,50,50
#Sta/Elev= 11
   -13.1   27.77    -3.1   27.77    -1.3   28.97       0   28.97      .2   27.77
     1.8   26.87     3.8   26.87     4.4   28.77     5.5   28.77     6.5   28.17
    16.5   28.17
#Mann= 3 , 0 , 0
   -13.1    .035       0       0    .035       0     4.4    .035       0
#XS Ineff= 2 , 0
               0   28.97     4.4           28.77
Permanent Ineff=
       F       F
Bank Sta=0,4.4
XS Rating Curve= 0
Exp/Cntr=.3,.1

Type RM Length L Ch R = 1 ,20      ,50,50,50
#Sta/Elev= 11
   -13.1    26.6    -3.1    26.6    -1.3    27.8       0    27.8      .2    26.6
     1.8    25.7     3.8    25.7     4.4    27.6     5.5    27.6     6.5      27
    16.5      27
#Mann= 3 , 0 , 0
   -13.1    .035       0       0    .035       0     4.4    .035       0
#XS Ineff= 2 , 0
               0    27.8     4.4            27.6
Permanent Ineff=
       F       F
Bank Sta=0,4.4
XS Rating Curve= 0
Exp/Cntr=.3,.1

Type RM Length L Ch R = 1 ,19      ,50,50,50
#Sta/Elev= 11
   -13.1   25.51    -3.1   25.51    -1.3   26.71       0   26.71      .2   25.51
     1.8   24.61     3.8   24.61     4.4   26.71     5.4   26.71     6.6   25.91
    16.6   25.91
#Mann= 3 , 0 , 0
   -13.1    .035       0       0    .035       0     4.4    .035       0
#XS Ineff= 2 , 0
               0   26.71     4.4           26.71
Permanent Ineff=
       F       F
Bank Sta=0,4.4
XS Rating Curve= 0
Exp/Cntr=.3,.1

Type RM Length L Ch R = 1 ,18      ,50,50,50
#Sta/Elev= 12
   -13.3   24.15    -3.3   24.15      -1   25.85       0   25.85     1.4   24.45
     3.9   24.15     6.4   24.15     6.9   24.95     9.1   25.75    10.1   25.75
    11.8   24.55    21.8   24.55
#Mann= 3 , 0 , 0
   -13.3    .035       0       0    .035       0     9.1    .035       0
#XS Ineff= 2 , 0
               0   25.85     9.1           25.75
Permanent Ineff=
       F       F
Bank Sta=0,9.1
XS Rating Curve= 0
Exp/Cntr=.3,.1

Type RM Length L Ch R = 1 ,17      ,50,50,50
#Sta/Elev= 13
   -12.3    23.2    -2.3    23.2      -1    24.2       0    24.2      .4    23.3
     1.9    22.7     3.4    22.7       4    24.2     4.4    24.2     4.9    24.4
     6.1    24.4     7.3    23.3    17.3    23.3
#Mann= 3 , 0 , 0
   -12.3    .035       0       0    .035       0       4    .035       0
Levee=-1,0,30,-1,4,30,,
#XS Ineff= 2 , 0
               0    24.2       4            24.2
Permanent Ineff=
       F       F
Bank Sta=0,4
XS Rating Curve= 0
Exp/Cntr=.3,.1

Type RM Length L Ch R = 1 ,16      ,50,50,50
#Sta/Elev= 13
   -12.5    22.4    -2.5    22.4      -1    23.6       0    23.6      .3    22.5
     1.9    21.9     3.5    21.9     3.9    23.3     4.3    23.3       5    23.5
     6.2    23.5     7.7    22.1    17.7    22.1
#Mann= 3 , 0 , 0
   -12.5    .035       0       0    .035       0     3.9    .035       0
Levee=-1,0,30,-1,3.9,30,,
#XS Ineff= 2 , 0
               0    23.6     3.9            23.3
Permanent Ineff=
       F       F
Bank Sta=0,3.9
XS Rating Curve= 0
Exp/Cntr=.3,.1

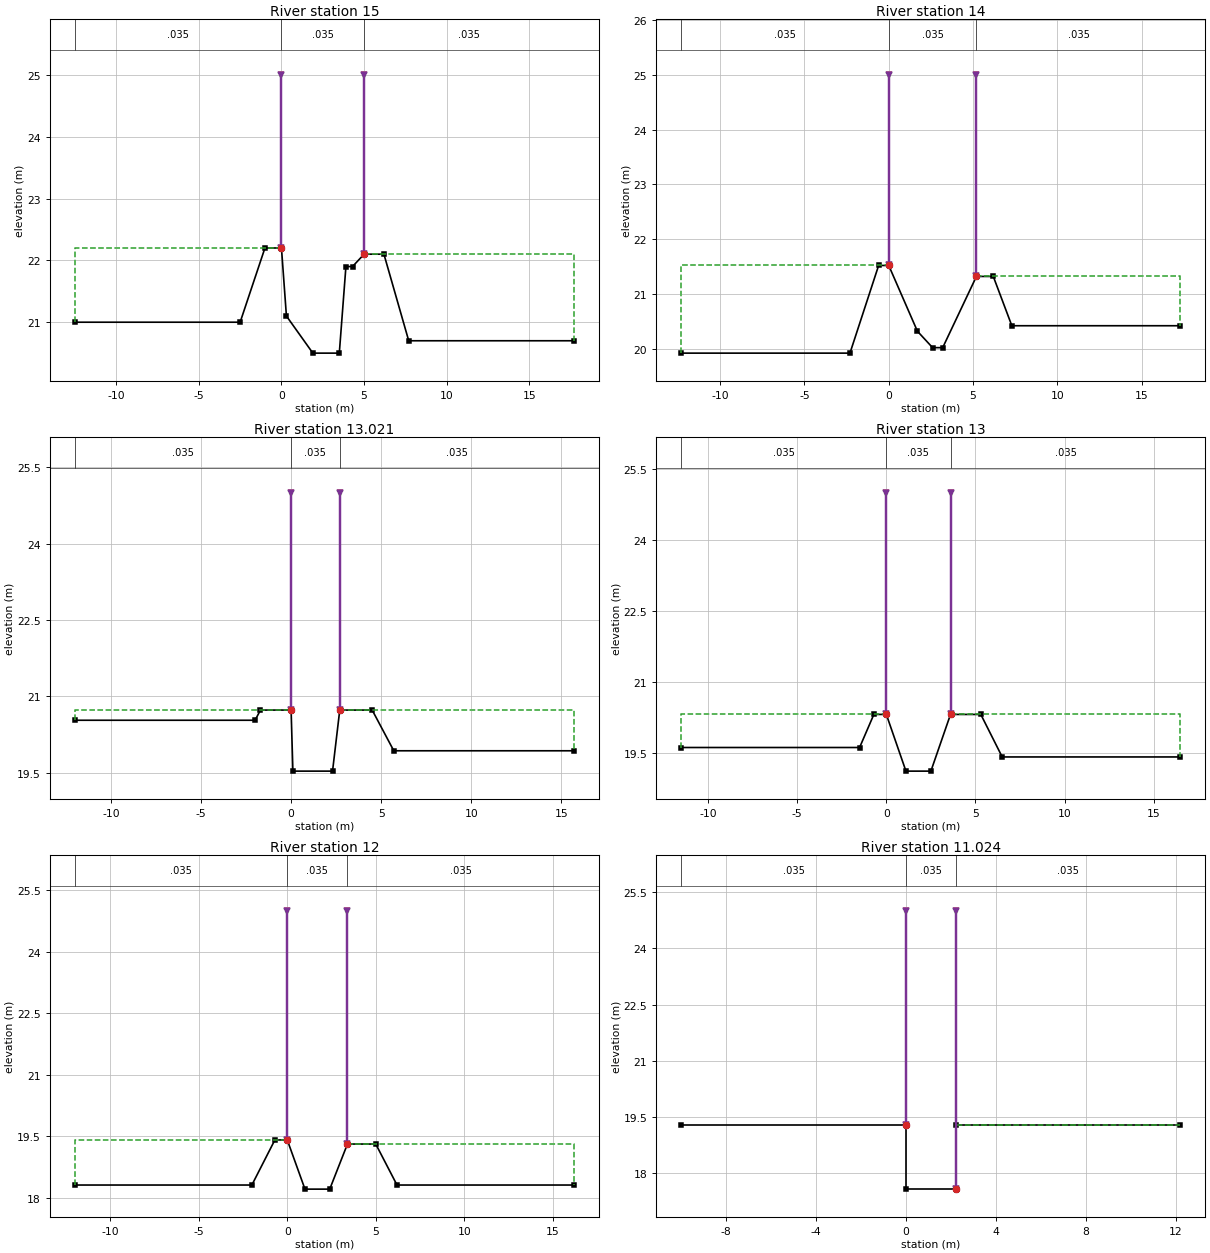
Type RM Length L Ch R = 1 ,15      ,50,50,50
#Sta/Elev= 13
   -12.5      21    -2.5      21      -1    22.2       0    22.2      .3    21.1
     1.9    20.5     3.5    20.5     3.9    21.9     4.3    21.9       5    22.1
     6.2    22.1     7.7    20.7    17.7    20.7
#Mann= 3 , 0 , 0
   -12.5    .035       0       0    .035       0       5    .035       0
Levee=-1,0,25,-1,5,25,,
#XS Ineff= 2 , 0
               0    22.2       5            22.1
Permanent Ineff=
       F       F
Bank Sta=0,5
XS Rating Curve= 0
Exp/Cntr=.3,.1

Type RM Length L Ch R = 1 ,14      ,29,29,29
#Sta/Elev= 11
   -12.3   19.92    -2.3   19.92     -.6   21.52       0   21.52     1.7   20.32
     2.6   20.02     3.2   20.02     5.2   21.32     6.2   21.32     7.3   20.42
    17.3   20.42
#Mann= 3 , 0 , 0
   -12.3    .035       0       0    .035       0     5.2    .035       0
Levee=-1,0,25,-1,5.2,25,,
#XS Ineff= 2 , 0
               0   21.52     5.2           21.32
Permanent Ineff=
       F       F
Bank Sta=0,5.2
XS Rating Curve= 0
Exp/Cntr=.3,.1

Type RM Length L Ch R = 1 ,13.021  ,21,21,21
#Sta/Elev= 10
     -12   20.53      -2   20.53    -1.7   20.73       0   20.73      .1   19.53
     2.3   19.53     2.7   20.73     4.5   20.73     5.7   19.93    15.7   19.93
#Mann= 3 , 0 , 0
     -12    .035       0       0    .035       0     2.7    .035       0
Levee=-1,0,25,-1,2.7,25,,
#XS Ineff= 2 , 0
               0   20.73     2.7           20.73
Permanent Ineff=
       F       F
Bank Sta=0,2.7
XS Rating Curve= 0
Exp/Cntr=.3,.1

Type RM Length L Ch R = 1 ,13      ,50,50,50
#Sta/Elev= 10
   -11.5   19.61    -1.5   19.61     -.7   20.31       0   20.31     1.1   19.11
     2.5   19.11     3.6   20.31     5.3   20.31     6.5   19.41    16.5   19.41
#Mann= 3 , 0 , 0
   -11.5    .035       0       0    .035       0     3.6    .035       0
Levee=-1,0,25,-1,3.6,25,,
#XS Ineff= 2 , 0
               0   20.31     3.6           20.31
Permanent Ineff=
       F       F
Bank Sta=0,3.6
XS Rating Curve= 0
Exp/Cntr=.3,.1

Type RM Length L Ch R = 1 ,12      ,26,26,26
#Sta/Elev= 10
     -12   18.31      -2   18.31     -.7   19.41       0   19.41       1   18.21
     2.4   18.21     3.4   19.31       5   19.31     6.2   18.31    16.2   18.31
#Mann= 3 , 0 , 0
     -12    .035       0       0    .035       0     3.4    .035       0
Levee=-1,0,25,-1,3.4,25,,
#XS Ineff= 2 , 0
               0   19.41     3.4           19.31
Permanent Ineff=
       F       F
Bank Sta=0,3.4
XS Rating Curve= 0
Exp/Cntr=.3,.1

Type RM Length L Ch R = 1 ,11.024  ,24,24,24
#Sta/Elev= 6
     -10   19.28       0   19.28       0   17.58     2.2   17.58     2.2   19.28
    12.2   19.28
#Mann= 3 , 0 , 0
     -10    .035       0       0    .035       0     2.2    .035       0
Levee=-1,0,25,-1,2.2,25,,
#XS Ineff= 2 , 0
               0   19.28     2.2           19.28
Permanent Ineff=
       F       F
Bank Sta=0,2.2
XS Rating Curve= 0
Exp/Cntr=.3,.1

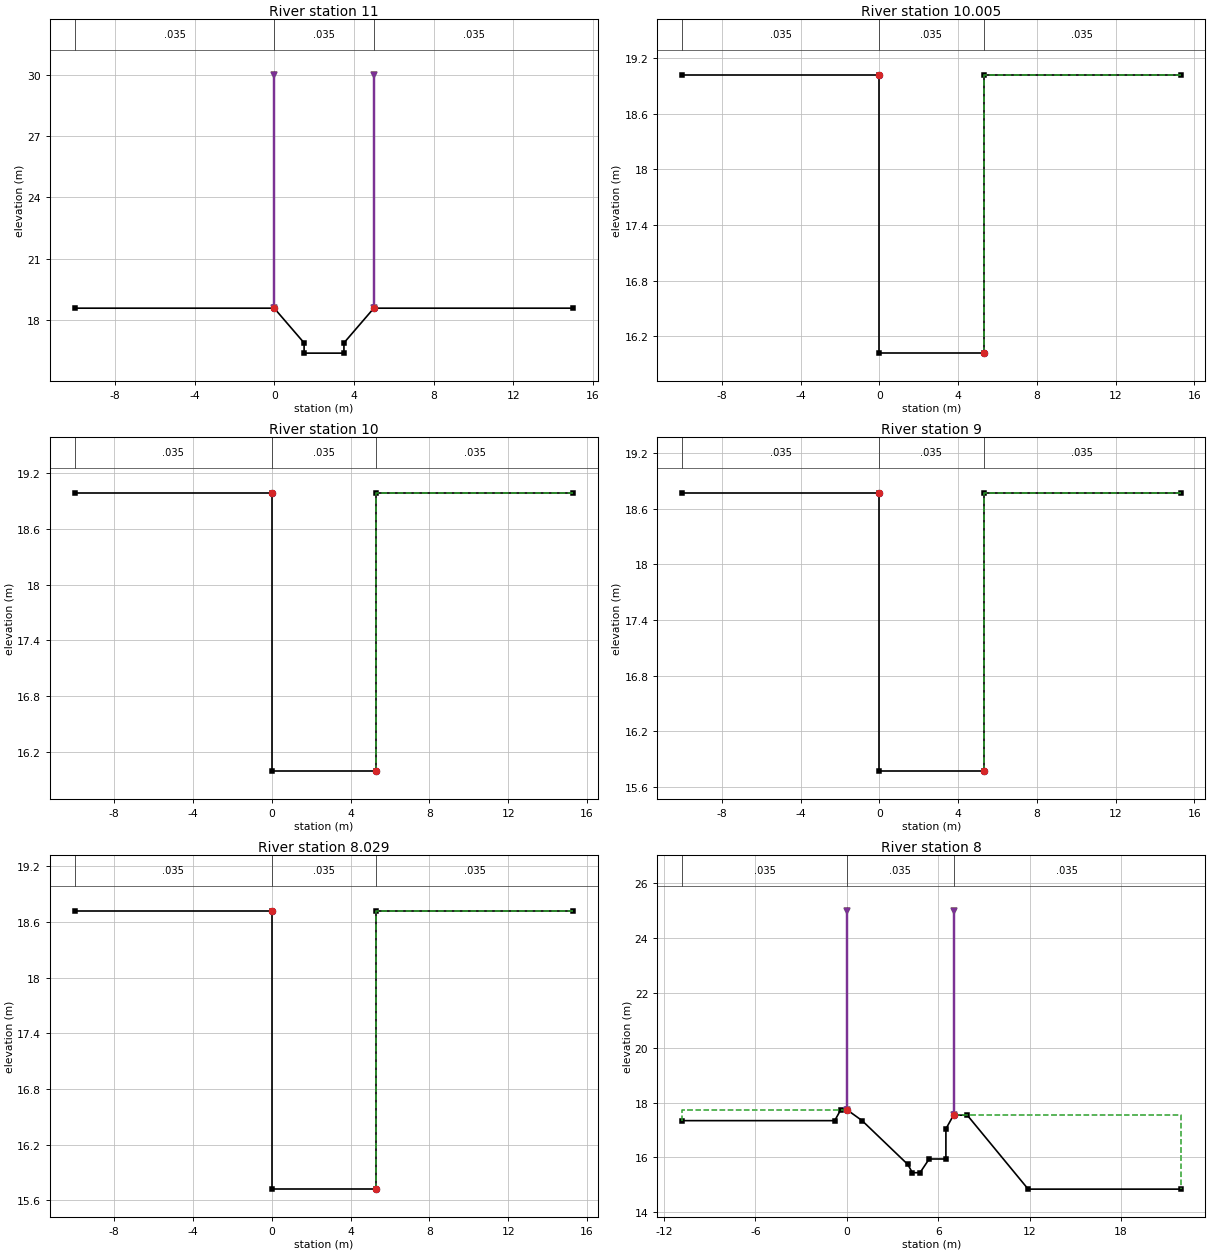
Type RM Length L Ch R = 1 ,11      ,45,45,45
#Sta/Elev= 8
     -10   18.58       0   18.58     1.5   16.88     1.5   16.38     3.5   16.38
     3.5   16.88       5   18.58      15   18.58
#Mann= 3 , 0 , 0
     -10    .035       0       0    .035       0       5    .035       0
Levee=-1,0,30,-1,5,30,,
#XS Ineff= 2 , 0
               0   18.58       5           18.58
Permanent Ineff=
       F       F
Bank Sta=0,5
XS Rating Curve= 0
Exp/Cntr=.3,.1

Type RM Length L Ch R = 1 ,10.005  ,5,5,5
#Sta/Elev= 6
     -10   19.02       0   19.02       0   16.02     5.3   16.02     5.3   19.02
    15.3   19.02
#Mann= 3 , 0 , 0
     -10    .035       0       0    .035       0     5.3    .035       0
#XS Ineff= 2 , 0
               0   19.02     5.3           19.02
Permanent Ineff=
       F       F
Bank Sta=0,5.3
XS Rating Curve= 0
Exp/Cntr=.3,.1

Type RM Length L Ch R = 1 ,10      ,50,50,50
#Sta/Elev= 6
     -10   18.99       0   18.99       0   15.99     5.3   15.99     5.3   18.99
    15.3   18.99
#Mann= 3 , 0 , 0
     -10    .035       0       0    .035       0     5.3    .035       0
#XS Ineff= 2 , 0
               0   18.99     5.3           18.99
Permanent Ineff=
       F       F
Bank Sta=0,5.3
XS Rating Curve= 0
Exp/Cntr=.3,.1

Type RM Length L Ch R = 1 ,9       ,21,21,21
#Sta/Elev= 6
     -10   18.77       0   18.77       0   15.77     5.3   15.77     5.3   18.77
    15.3   18.77
#Mann= 3 , 0 , 0
     -10    .035       0       0    .035       0     5.3    .035       0
#XS Ineff= 2 , 0
               0   18.77     5.3           18.77
Permanent Ineff=
       F       F
Bank Sta=0,5.3
XS Rating Curve= 0
Exp/Cntr=.3,.1

Type RM Length L Ch R = 1 ,8.029   ,29,29,29
#Sta/Elev= 6
     -10   18.72       0   18.72       0   15.72     5.3   15.72     5.3   18.72
    15.3   18.72
#Mann= 3 , 0 , 0
     -10    .035       0       0    .035       0     5.3    .035       0
#XS Ineff= 2 , 0
               0   18.72     5.3           18.72
Permanent Ineff=
       F       F
Bank Sta=0,5.3
XS Rating Curve= 0
Exp/Cntr=.3,.1

Type RM Length L Ch R = 1 ,8       ,37,37,37
#Sta/Elev= 15
   -10.8   17.34     -.8   17.34     -.4   17.74       0   17.74       1   17.34
       4   15.74     4.3   15.44     4.8   15.44     5.4   15.94     6.5   15.94
     6.5   17.04       7   17.54     7.9   17.54    11.9   14.84    21.9   14.84
#Mann= 3 , 0 , 0
   -10.8    .035       0       0    .035       0       7    .035       0
Levee=-1,0,25,-1,7,25,,
#XS Ineff= 2 , 0
               0   17.74       7           17.54
Permanent Ineff=
       F       F
Bank Sta=0,7
XS Rating Curve= 0
Exp/Cntr=.3,.1

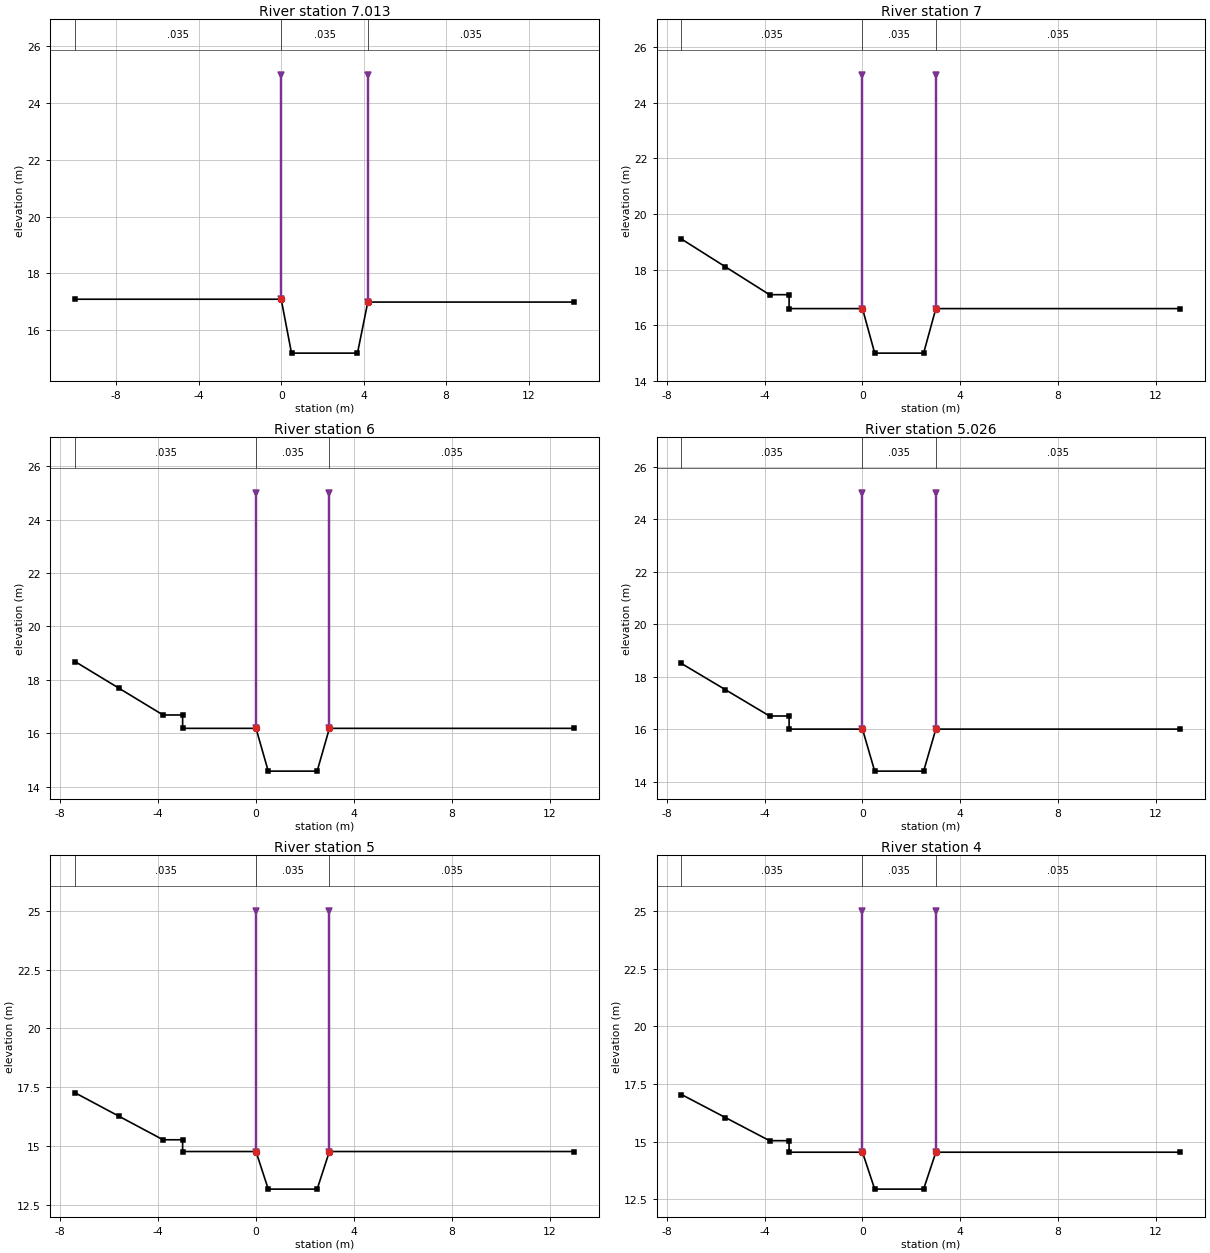
Type RM Length L Ch R = 1 ,7.013   ,13,13,13
#Sta/Elev= 6
     -10   17.09       0   17.09      .5   15.19     3.7   15.19     4.2   16.99
    14.2   16.99
#Mann= 3 , 0 , 0
     -10    .035       0       0    .035       0     4.2    .035       0
Levee=-1,0,25,-1,4.2,25,,
#XS Ineff= 2 , 0
               0   17.09     4.2           16.99
Permanent Ineff=
       F       F
Bank Sta=0,4.2
XS Rating Curve= 0
Exp/Cntr=.3,.1

Type RM Length L Ch R = 1 ,7       ,50,50,50
#Sta/Elev= 10
    -7.4    19.1    -5.6    18.1    -3.8    17.1      -3    17.1      -3    16.6
       0    16.6      .5      15     2.5      15       3    16.6      13    16.6
#Mann= 3 , 0 , 0
    -7.4    .035       0       0    .035       0       3    .035       0
Levee=-1,0,25,-1,3,25,,
#XS Ineff= 2 , 0
               0    16.6       3            16.6
Permanent Ineff=
       F       F
Bank Sta=0,3
XS Rating Curve= 0
Exp/Cntr=.3,.1

Type RM Length L Ch R = 1 ,6       ,24,24,24
#Sta/Elev= 10
    -7.4   18.69    -5.6   17.69    -3.8   16.69      -3   16.69      -3   16.19
       0   16.19      .5   14.59     2.5   14.59       3   16.19      13   16.19
#Mann= 3 , 0 , 0
    -7.4    .035       0       0    .035       0       3    .035       0
Levee=-1,0,25,-1,3,25,,
#XS Ineff= 2 , 0
               0   16.19       3           16.19
Permanent Ineff=
       F       F
Bank Sta=0,3
XS Rating Curve= 0
Exp/Cntr=.3,.1

Type RM Length L Ch R = 1 ,5.026   ,26,26,26
#Sta/Elev= 10
    -7.4    18.5    -5.6    17.5    -3.8    16.5      -3    16.5      -3      16
       0      16      .5    14.4     2.5    14.4       3      16      13      16
#Mann= 3 , 0 , 0
    -7.4    .035       0       0    .035       0       3    .035       0
Levee=-1,0,25,-1,3,25,,
#XS Ineff= 2 , 0
               0      16       3              16
Permanent Ineff=
       F       F
Bank Sta=0,3
XS Rating Curve= 0
Exp/Cntr=.3,.1

Type RM Length L Ch R = 1 ,5       ,50,50,50
#Sta/Elev= 10
    -7.4   17.26    -5.6   16.26    -3.8   15.26      -3   15.26      -3   14.76
       0   14.76      .5   13.16     2.5   13.16       3   14.76      13   14.76
#Mann= 3 , 0 , 0
    -7.4    .035       0       0    .035       0       3    .035       0
Levee=-1,0,25,-1,3,25,,
#XS Ineff= 2 , 0
               0   14.76       3           14.76
Permanent Ineff=
       F       F
Bank Sta=0,3
XS Rating Curve= 0
Exp/Cntr=.3,.1

Type RM Length L Ch R = 1 ,4       ,50,50,50
#Sta/Elev= 10
    -7.4   17.04    -5.6   16.04    -3.8   15.04      -3   15.04      -3   14.54
       0   14.54      .5   12.94     2.5   12.94       3   14.54      13   14.54
#Mann= 3 , 0 , 0
    -7.4    .035       0       0    .035       0       3    .035       0
Levee=-1,0,25,-1,3,25,,
#XS Ineff= 2 , 0
               0   14.54       3           14.54
Permanent Ineff=
       F       F
Bank Sta=0,3
XS Rating Curve= 0
Exp/Cntr=.3,.1

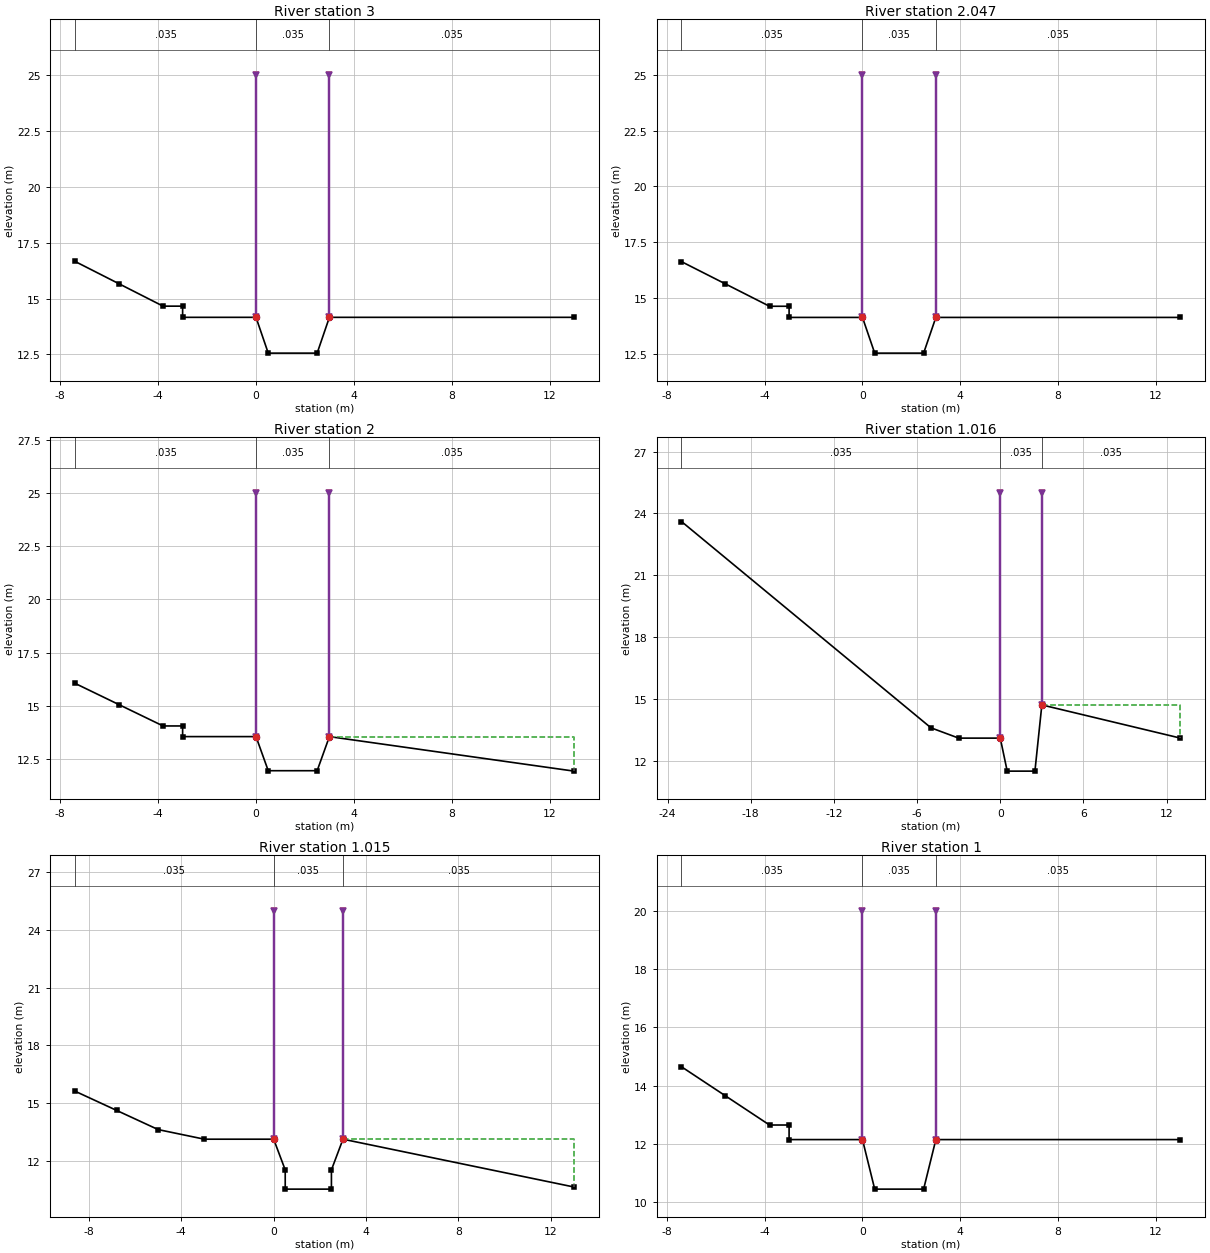
Type RM Length L Ch R = 1 ,3       ,3,3,3
#Sta/Elev= 10
    -7.4   16.66    -5.6   15.66    -3.8   14.66      -3   14.66      -3   14.16
       0   14.16      .5   12.56     2.5   12.56       3   14.16      13   14.16
#Mann= 3 , 0 , 0
    -7.4    .035       0       0    .035       0       3    .035       0
Levee=-1,0,25,-1,3,25,,
#XS Ineff= 2 , 0
               0   14.16       3           14.16
Permanent Ineff=
       F       F
Bank Sta=0,3
XS Rating Curve= 0
Exp/Cntr=.3,.1

Type RM Length L Ch R = 1 ,2.047   ,47,47,47
#Sta/Elev= 10
    -7.4   16.63    -5.6   15.63    -3.8   14.63      -3   14.63      -3   14.13
       0   14.13      .5   12.53     2.5   12.53       3   14.13      13   14.13
#Mann= 3 , 0 , 0
    -7.4    .035       0       0    .035       0       3    .035       0
Levee=-1,0,25,-1,3,25,,
#XS Ineff= 2 , 0
               0   14.13       3           14.13
Permanent Ineff=
       F       F
Bank Sta=0,3
XS Rating Curve= 0
Exp/Cntr=.3,.1

Type RM Length L Ch R = 1 ,2       ,34,34,34
#Sta/Elev= 10
    -7.4   16.06    -5.6   15.06    -3.8   14.06      -3   14.06      -3   13.56
       0   13.56      .5   11.96     2.5   11.96       3   13.56      13   11.94
#Mann= 3 , 0 , 0
    -7.4    .035       0       0    .035       0       3    .035       0
Levee=-1,0,25,-1,3,25,,
#XS Ineff= 2 , 0
               0   13.56       3           13.56
Permanent Ineff=
       F       F
Bank Sta=0,3
XS Rating Curve= 0
Exp/Cntr=.3,.1

Type RM Length L Ch R = 1 ,1.016   ,1,1,1
#Sta/Elev= 8
     -23   23.61      -5   13.61      -3   13.11       0   13.11      .5   11.51
     2.5   11.51       3   14.72      13   13.11
#Mann= 3 , 0 , 0
     -23    .035       0       0    .035       0       3    .035       0
Levee=-1,0,25,-1,3,25,,
#XS Ineff= 2 , 0
               0   13.11       3           14.72
Permanent Ineff=
       F       F
Bank Sta=0,3
XS Rating Curve= 0
Exp/Cntr=.3,.1

Type RM Length L Ch R = 1 ,1.015   ,15,15,15
#Sta/Elev= 11
    -8.6   15.61    -6.8   14.61      -5   13.61      -3   13.11       0   13.11
      .5   11.51      .5   10.51     2.5   10.51     2.5   11.51       3   13.11
      13   10.62
#Mann= 3 , 0 , 0
    -8.6    .035       0       0    .035       0       3    .035       0
Levee=-1,0,25,-1,3,25,,
#XS Ineff= 2 , 0
               0   13.11       3           13.11
Permanent Ineff=
       F       F
Bank Sta=0,3
XS Rating Curve= 0
Exp/Cntr=.3,.1

Type RM Length L Ch R = 1 ,1       ,5,5,5
#Sta/Elev= 10
    -7.4   14.65    -5.6   13.65    -3.8   12.65      -3   12.65      -3   12.15
       0   12.15      .5   10.45     2.5   10.45       3   12.15      13   12.15
#Mann= 3 , 0 , 0
    -7.4    .035       0       0    .035       0       3    .035       0
Levee=-1,0,20,-1,3,20,,
#XS Ineff= 2 , 0
               0   12.15       3           12.15
Permanent Ineff=
       F       F
Bank Sta=0,3
XS Rating Curve= 0
Exp/Cntr=.3,.1