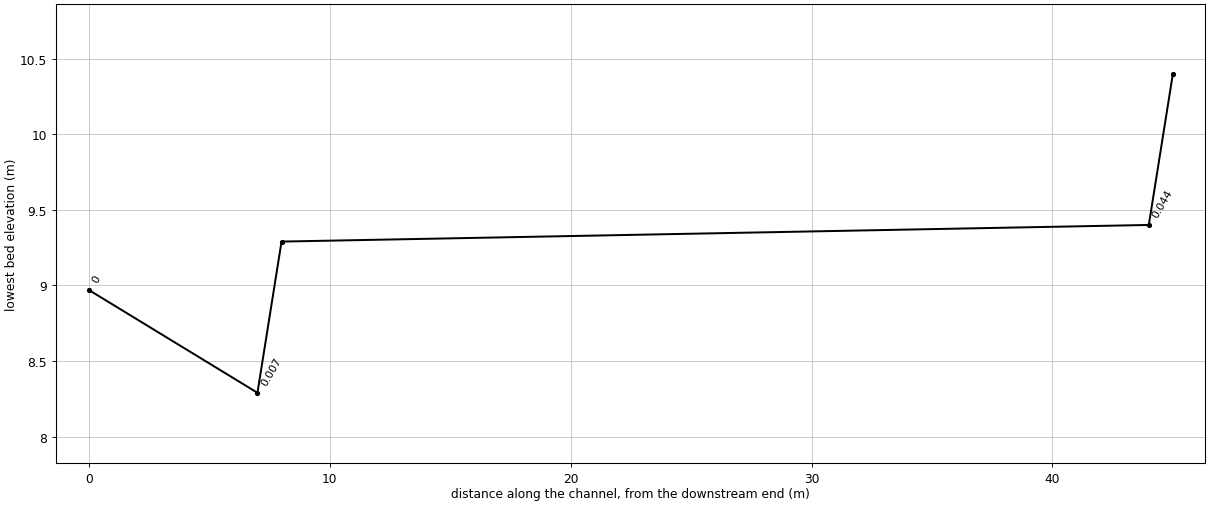
HEC-RAS study SDC.prj: sadong-ch

--- SDC.g01 (geometry) --- (continued)

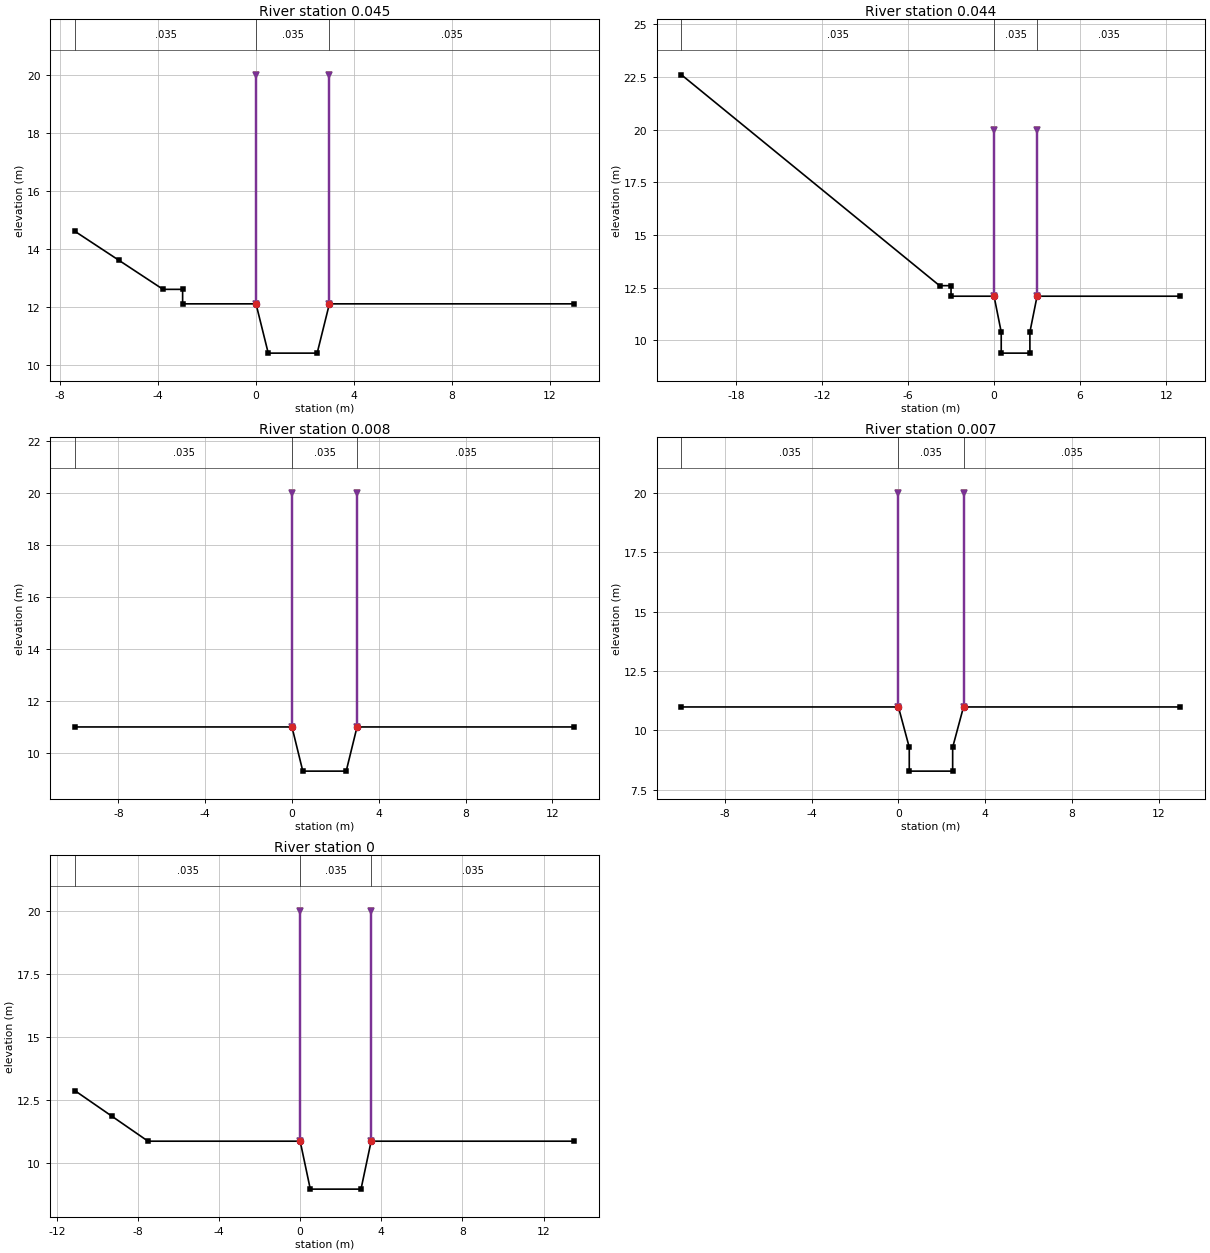
Type RM Length L Ch R = 1 ,0.045   ,1,1,1
#Sta/Elev= 10
    -7.4    14.6    -5.6    13.6    -3.8    12.6      -3    12.6      -3    12.1
       0    12.1      .5    10.4     2.5    10.4       3    12.1      13    12.1
#Mann= 3 , 0 , 0
    -7.4    .035       0       0    .035       0       3    .035       0
Levee=-1,0,20,-1,3,20,,
#XS Ineff= 2 , 0
               0    12.1       3            12.1
Permanent Ineff=
       F       F
Bank Sta=0,3
XS Rating Curve= 0
Exp/Cntr=.3,.1

Type RM Length L Ch R = 1 ,0.044   ,36,36,36
#Sta/Elev= 11
   -21.8    22.6    -3.8    12.6      -3    12.6      -3    12.1       0    12.1
      .5    10.4      .5     9.4     2.5     9.4     2.5    10.4       3    12.1
      13    12.1
#Mann= 3 , 0 , 0
   -21.8    .035       0       0    .035       0       3    .035       0
Levee=-1,0,20,-1,3,20,,
#XS Ineff= 2 , 0
               0    12.1       3            12.1
Permanent Ineff=
       F       F
Bank Sta=0,3
XS Rating Curve= 0
Exp/Cntr=.3,.1

Type RM Length L Ch R = 1 ,0.008   ,1,1,1
#Sta/Elev= 6
     -10   10.99       0   10.99      .5    9.29     2.5    9.29       3   10.99
      13   10.99
#Mann= 3 , 0 , 0
     -10    .035       0       0    .035       0       3    .035       0
Levee=-1,0,20,-1,3,20,,
#XS Ineff= 2 , 0
               0   10.99       3           10.99
Permanent Ineff=
       F       F
Bank Sta=0,3
XS Rating Curve= 0
Exp/Cntr=.3,.1

Type RM Length L Ch R = 1 ,0.007   ,7,7,7
#Sta/Elev= 8
     -10   10.99       0   10.99      .5    9.29      .5    8.29     2.5    8.29
     2.5    9.29       3   10.99      13   10.99
#Mann= 3 , 0 , 0
     -10    .035       0       0    .035       0       3    .035       0
Levee=-1,0,20,-1,3,20,,
#XS Ineff= 2 , 0
               0   10.99       3           10.99
Permanent Ineff=
       F       F
Bank Sta=0,3
XS Rating Curve= 0
Exp/Cntr=.3,.1

Type RM Length L Ch R = 1 ,0       ,0,0,0
#Sta/Elev= 8
   -11.1   12.87    -9.3   11.87    -7.5   10.87       0   10.87      .5    8.97
       3    8.97     3.5   10.87    13.5   10.87
#Mann= 3 , 0 , 0
   -11.1    .035       0       0    .035       0     3.5    .035       0
Levee=-1,0,20,-1,3.5,20,,
#XS Ineff= 2 , 0
               0   10.87     3.5           10.87
Permanent Ineff=
       F       F
Bank Sta=0,3.5
XS Rating Curve= 0
Exp/Cntr=.3,.1

Chan Stop Cuts=-1