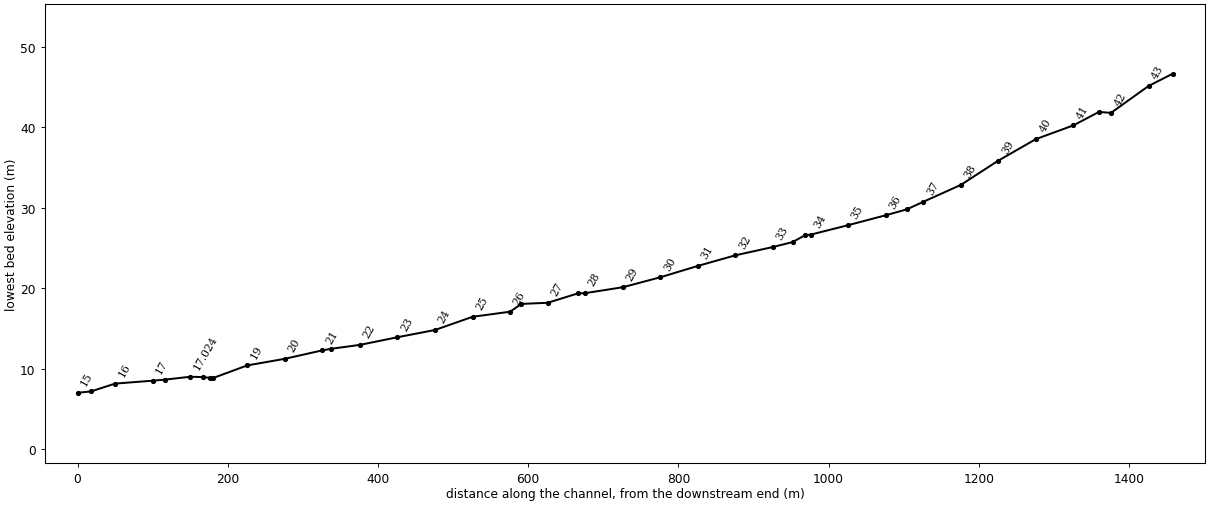
--- EJC.prj (project) ---

Proj Title=eucje-ch
Current Plan=p01
Default Exp/Contr=.3,.1
SI Units
Geom File=g01
Flow File=f01
Plan File=p01
Y Axis Title=Elevation
X Axis Title(PF)=Main Channel Distance
X Axis Title(XS)=Station
BEGIN DESCRIPTION:
           BACK WATER COMPUTATION
      APPLICATION OF HEC-2 BY Samju Construction Engineering
      eucje-ch: 10,20,30,50,80 yr
END DESCRIPTION:
DSS Export Rating Curves= 0
DSS Export Rating Curve Sorted= 0
DSS Export Volume Flow Curves= 0
DXF OffsetX= 0
DXF OffsetY= 0
DXF ScaleX= 1
DXF ScaleY= 10

--- EJC.p01 (plan) ---

Plan Title=Imported Plan 01
Version=Version 3.0.1  Mar 2001
Short Identifier=Imported Pla
Geom File=g01
Flow File=f01
Subcritical Flow
K Sum by GR= 0
Std Step Tol= 0.003
Critical Tol= 0.003
Num of Std Step Trials= 20
Max Error Tol= 0.1
Flow Tol Ratio= 0.001
Split Flow NTrial= 30
Split Flow Tol= 0.02
Split Flow Ratio= 0.02
Log Output Level= 0
Friction Slope Method= 1
Unsteady Friction Slope Method= 2
Parabolic Critical Depth
Global Vel Dist= 0 , 0 , 0
Global Log Level= 0
CheckData=True
Encroach Param=-1 ,0,0, 0
Computation Interval=1HOUR
Output Interval=1HOUR
Run HTab= 0
Run UNet= 0
Run PostProcess= 0
UNET Theta= 1
UNET ZTol= 0.02
UNET ZSATol= 0.1
UNET MxIter= 20
UNET MaxInSteps= 20
UNET DtIC= 0
UNET DtMin= 0
UNET MaxCRTS= 20
UNET WFStab= 2
UNET SFStab= 1
UNET WFX= 1
UNET SFX= 1
UNET Convert EG Bridges=-1
UNET Use Existing IB Tables=-1
Instantaneous Interval=1HOUR
Write IC File= 0
Write Velocity= 0
Write Detailed= 0

--- EJC.f01 (steady flow) ---

Flow Title=Imported Flow 01
Version=Version 3.0.1  Mar 2001
Number of Profiles= 5
Profile Names=10YR,20YR,30YR,50YR,80YR
River Rch & RM=RIVER-1,Reach-1         ,43.032
   15.21   16.75   17.66    18.8   19.84
River Rch & RM=RIVER-1,Reach-1         ,20
   32.29   35.59   37.52   39.96   42.19
River Rch & RM=EUKJE,EUKJE           ,43.032
   15.21   16.75   17.66    18.8   19.84
River Rch & RM=EUKJE,EUKJE           ,20
   32.29   35.59   37.52   39.96   42.19
Boundary for River Rch & Prof#=EUKJE,EUKJE           , 1
Up Type= 0
Dn Type= 3
Dn Slope=.019
Boundary for River Rch & Prof#=EUKJE,EUKJE           , 2
Up Type= 0
Dn Type= 3
Dn Slope=.019
Boundary for River Rch & Prof#=EUKJE,EUKJE           , 3
Up Type= 0
Dn Type= 3
Dn Slope=.019
Boundary for River Rch & Prof#=EUKJE,EUKJE           , 4
Up Type= 0
Dn Type= 3
Dn Slope=.019
Boundary for River Rch & Prof#=EUKJE,EUKJE           , 5
Up Type= 0
Dn Type= 3
Dn Slope=.019
DSS Import GetInterval= 0
DSS Import GetPeak= 0
DSS Import FillOption= 0

--- EJC.g01 (geometry) ---

Geom Title=Imported Geom 01
Version=Version 3.0.1  Mar 2001

River Reach=EUKJE           ,EUKJE
Reach XY= 2
              .5             .95              .5             .05

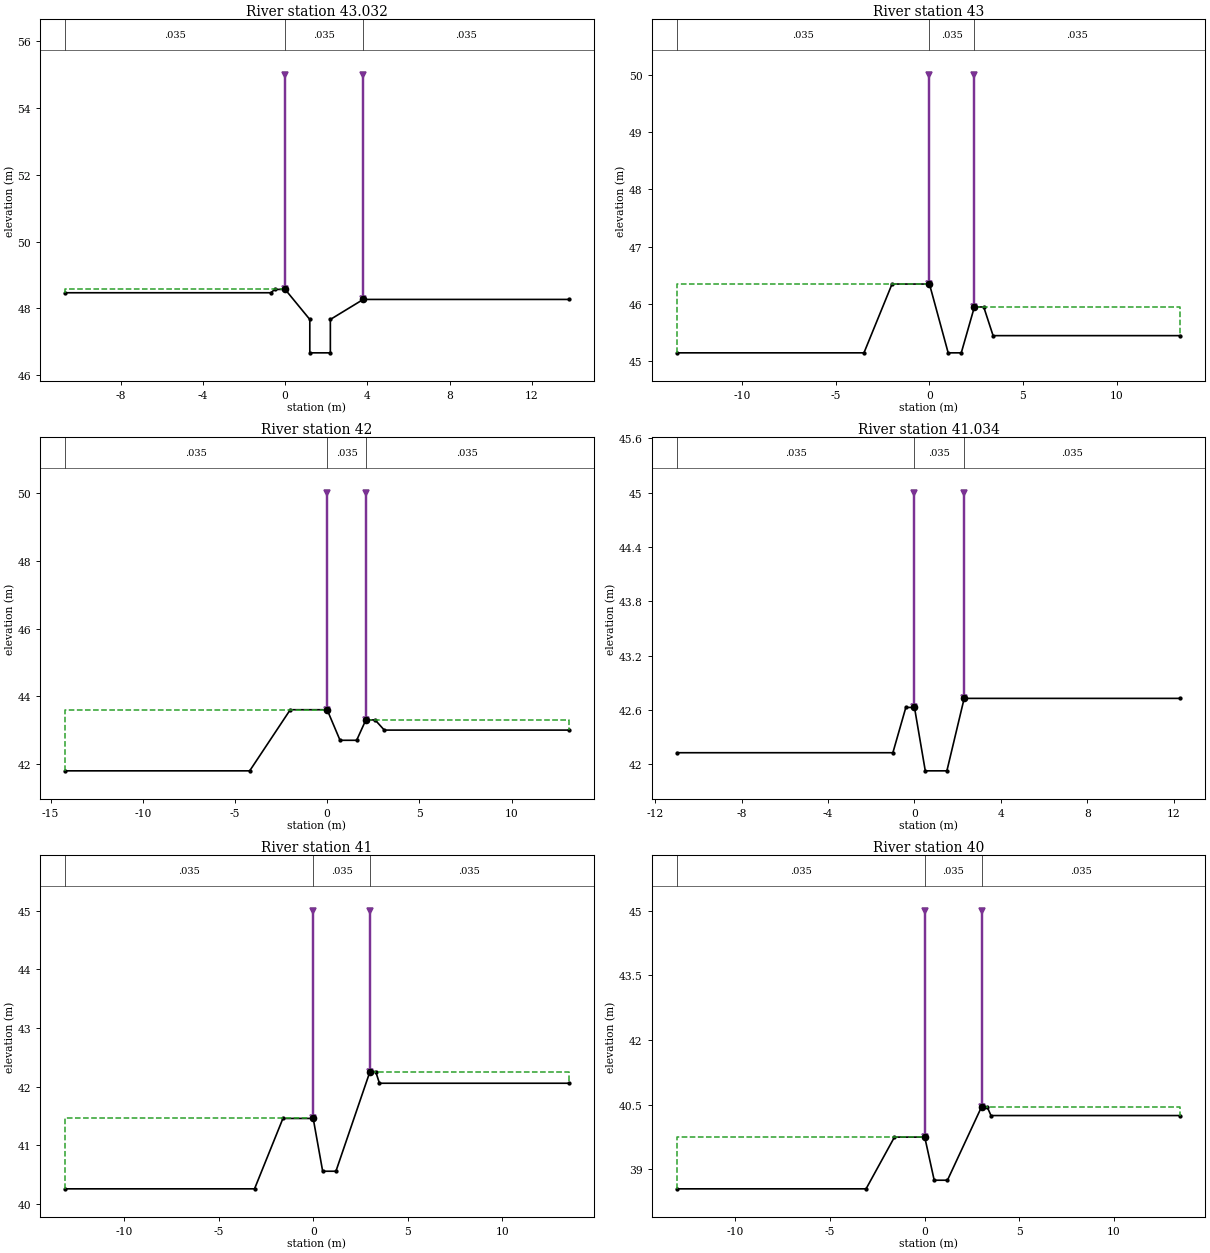
Type RM Length L Ch R = 1 ,43.032  ,32,32,32
#Sta/Elev= 10
   -10.7   48.47     -.7   48.47     -.5   48.57       0   48.57     1.2   47.67
     1.2   46.67     2.2   46.67     2.2   47.67     3.8   48.27    13.8   48.27
#Mann= 3 , 0 , 0
   -10.7    .035       0       0    .035       0     3.8    .035       0
Levee=-1,0,55,-1,3.8,55,,
#XS Ineff= 2 , 0
               0   48.57     3.8           48.27
Permanent Ineff=
       F       F
Bank Sta=0,3.8
XS Rating Curve= 0
Exp/Cntr=.3,.1

Type RM Length L Ch R = 1 ,43      ,50,50,50
#Sta/Elev= 10
   -13.5   45.15    -3.5   45.15      -2   46.35       0   46.35       1   45.15
     1.7   45.15     2.4   45.95     2.9   45.95     3.4   45.45    13.4   45.45
#Mann= 3 , 0 , 0
   -13.5    .035       0       0    .035       0     2.4    .035       0
Levee=-1,0,50,-1,2.4,50,,
#XS Ineff= 2 , 0
               0   46.35     2.4           45.95
Permanent Ineff=
       F       F
Bank Sta=0,2.4
XS Rating Curve= 0
Exp/Cntr=.3,.1

Type RM Length L Ch R = 1 ,42      ,16,16,16
#Sta/Elev= 10
   -14.2   41.81    -4.2   41.81      -2   43.61       0   43.61      .7   42.71
     1.6   42.71     2.1   43.31     2.6   43.31     3.1   43.01    13.1   43.01
#Mann= 3 , 0 , 0
   -14.2    .035       0       0    .035       0     2.1    .035       0
Levee=-1,0,50,-1,2.1,50,,
#XS Ineff= 2 , 0
               0   43.61     2.1           43.31
Permanent Ineff=
       F       F
Bank Sta=0,2.1
XS Rating Curve= 0
Exp/Cntr=.3,.1

Type RM Length L Ch R = 1 ,41.034  ,34,34,34
#Sta/Elev= 8
     -11   42.13      -1   42.13     -.4   42.63       0   42.63      .5   41.93
     1.5   41.93     2.3   42.73    12.3   42.73
#Mann= 3 , 0 , 0
     -11    .035       0       0    .035       0     2.3    .035       0
Levee=-1,0,45,-1,2.3,45,,
#XS Ineff= 2 , 0
       0       0   42.63     2.3       0   42.73
Permanent Ineff=
       F       F
Bank Sta=0,2.3
XS Rating Curve= 0
Exp/Cntr=.3,.1

Type RM Length L Ch R = 1 ,41      ,50,50,50
#Sta/Elev= 10
   -13.1   40.26    -3.1   40.26    -1.6   41.46       0   41.46      .5   40.56
     1.2   40.56       3   42.26     3.3   42.26     3.5   42.06    13.5   42.06
#Mann= 3 , 0 , 0
   -13.1    .035       0       0    .035       0       3    .035       0
Levee=-1,0,45,-1,3,45,,
#XS Ineff= 2 , 0
               0   41.46       3           42.26
Permanent Ineff=
       F       F
Bank Sta=0,3
XS Rating Curve= 0
Exp/Cntr=.3,.1

Type RM Length L Ch R = 1 ,40      ,50,50,50
#Sta/Elev= 10
   -13.1   38.55    -3.1   38.55    -1.6   39.75       0   39.75      .5   38.75
     1.2   38.75       3   40.45     3.3   40.45     3.5   40.25    13.5   40.25
#Mann= 3 , 0 , 0
   -13.1    .035       0       0    .035       0       3    .035       0
Levee=-1,0,45,-1,3,45,,
#XS Ineff= 2 , 0
               0   39.75       3           40.45
Permanent Ineff=
       F       F
Bank Sta=0,3
XS Rating Curve= 0
Exp/Cntr=.3,.1

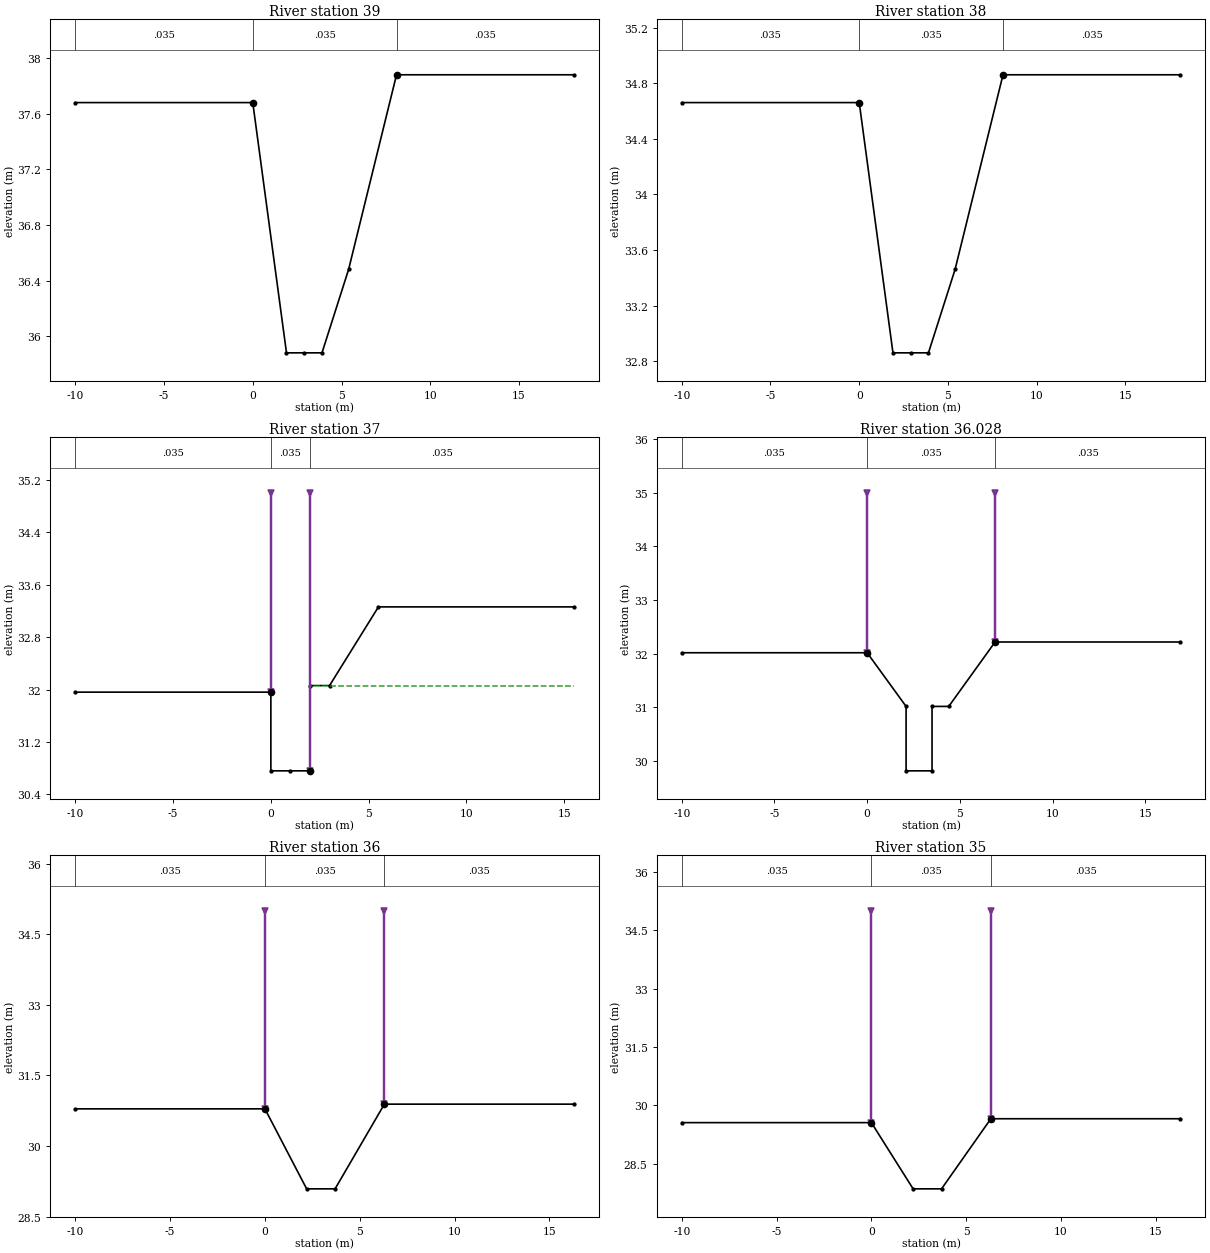
Type RM Length L Ch R = 1 ,39      ,50,50,50
#Sta/Elev= 8
     -10   37.68       0   37.68     1.9   35.88     2.9   35.88     3.9   35.88
     5.4   36.48     8.1   37.88    18.1   37.88
#Mann= 3 , 0 , 0
     -10    .035       0       0    .035       0     8.1    .035       0
#XS Ineff= 2 , 0
               0   37.68     8.1           37.88
Permanent Ineff=
       F       F
Bank Sta=0,8.1
XS Rating Curve= 0
Exp/Cntr=.3,.1

Type RM Length L Ch R = 1 ,38      ,50,50,50
#Sta/Elev= 8
     -10   34.66       0   34.66     1.9   32.86     2.9   32.86     3.9   32.86
     5.4   33.46     8.1   34.86    18.1   34.86
#Mann= 3 , 0 , 0
     -10    .035       0       0    .035       0     8.1    .035       0
#XS Ineff= 2 , 0
               0   34.66     8.1           34.86
Permanent Ineff=
       F       F
Bank Sta=0,8.1
XS Rating Curve= 0
Exp/Cntr=.3,.1

Type RM Length L Ch R = 1 ,37      ,22,22,22
#Sta/Elev= 9
     -10   31.96       0   31.96       0   30.76       1   30.76       2   30.76
       2   32.06       3   32.06     5.5   33.26    15.5   33.26
#Mann= 3 , 0 , 0
     -10    .035       0       0    .035       0       2    .035       0
Levee=-1,0,35,-1,2,35,,
#XS Ineff= 2 , 0
               0   31.96       2           32.06
Permanent Ineff=
       F       F
Bank Sta=0,2
XS Rating Curve= 0
Exp/Cntr=.3,.1

Type RM Length L Ch R = 1 ,36.028  ,28,28,28
#Sta/Elev= 9
     -10   32.02       0   32.02     2.1   31.02     2.1   29.82     3.5   29.82
     3.5   31.02     4.4   31.02     6.9   32.22    16.9   32.22
#Mann= 3 , 0 , 0
     -10    .035       0       0    .035       0     6.9    .035       0
Levee=-1,0,35,-1,6.9,35,,
#XS Ineff= 2 , 0
       0       0   32.02     6.9       0   32.22
Permanent Ineff=
       F       F
Bank Sta=0,6.9
XS Rating Curve= 0
Exp/Cntr=.3,.1

Type RM Length L Ch R = 1 ,36      ,50,50,50
#Sta/Elev= 6
     -10   30.79       0   30.79     2.2   29.09     3.7   29.09     6.3   30.89
    16.3   30.89
#Mann= 3 , 0 , 0
     -10    .035       0       0    .035       0     6.3    .035       0
Levee=-1,0,35,-1,6.3,35,,
#XS Ineff= 2 , 0
               0   30.79     6.3           30.89
Permanent Ineff=
       F       F
Bank Sta=0,6.3
XS Rating Curve= 0
Exp/Cntr=.3,.1

Type RM Length L Ch R = 1 ,35      ,50,50,50
#Sta/Elev= 6
     -10   29.56       0   29.56     2.2   27.86     3.7   27.86     6.3   29.66
    16.3   29.66
#Mann= 3 , 0 , 0
     -10    .035       0       0    .035       0     6.3    .035       0
Levee=-1,0,35,-1,6.3,35,,
#XS Ineff= 2 , 0
               0   29.56     6.3           29.66
Permanent Ineff=
       F       F
Bank Sta=0,6.3
XS Rating Curve= 0
Exp/Cntr=.3,.1

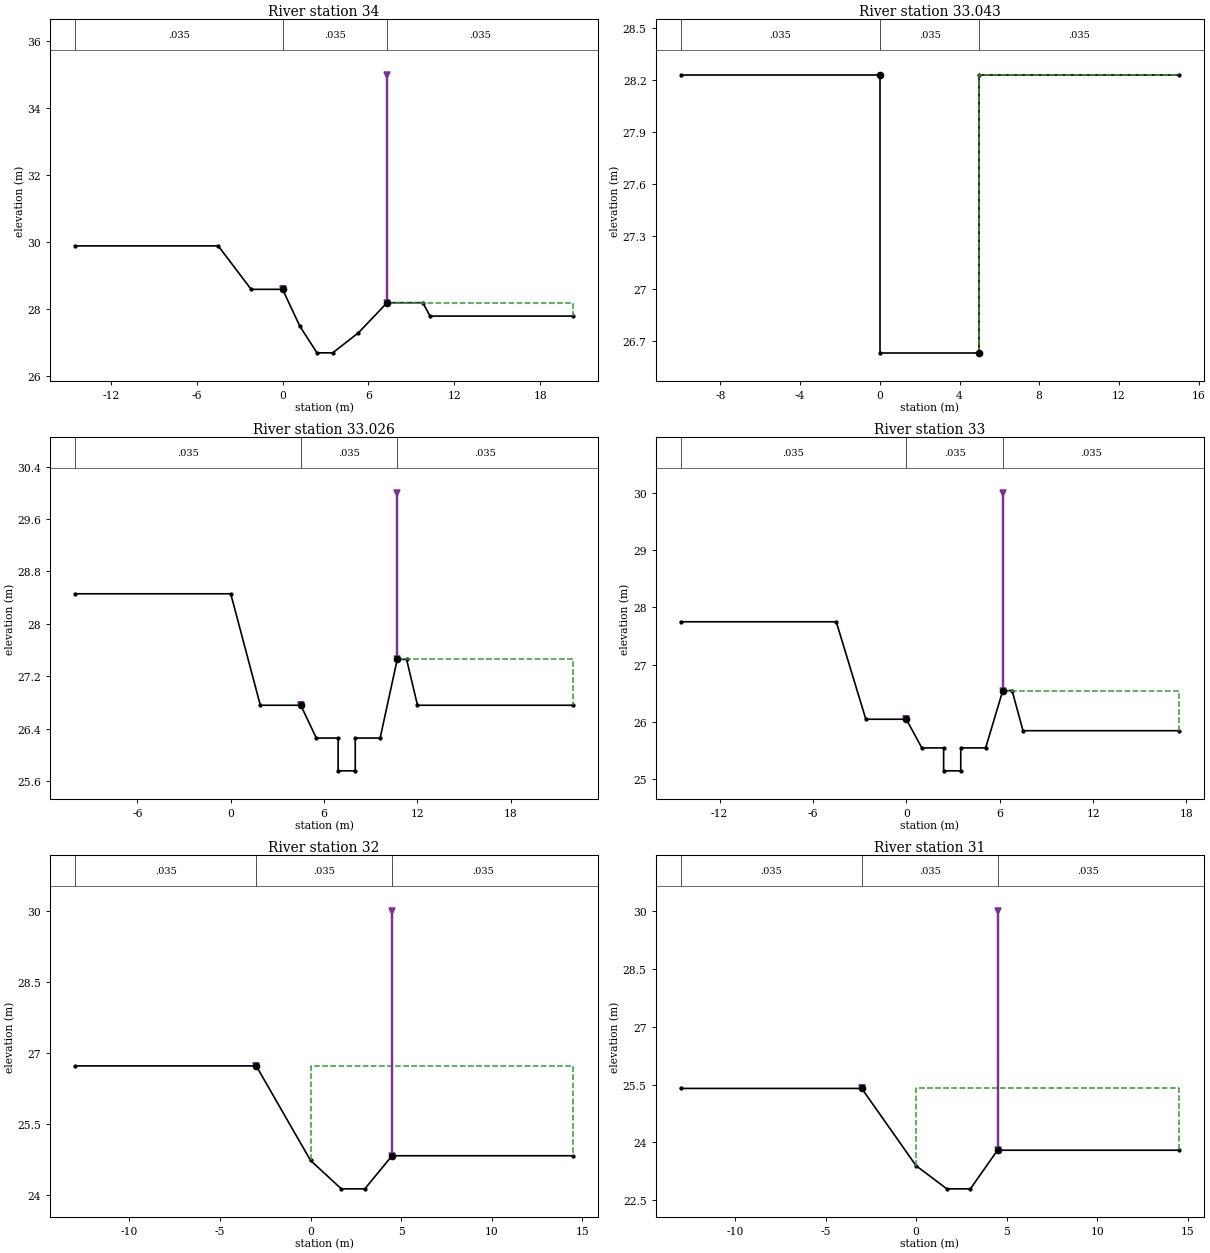
Type RM Length L Ch R = 1 ,34      ,7,7,7
#Sta/Elev= 12
   -14.5   29.88    -4.5   29.88    -2.2   28.58       0   28.58     1.2   27.48
     2.4   26.68     3.5   26.68     5.3   27.28     7.3   28.18     9.8   28.18
    10.3   27.78    20.3   27.78
#Mann= 3 , 0 , 0
   -14.5    .035       0       0    .035       0     7.3    .035       0
Levee=-1,0,28.58,-1,7.3,35,,
#XS Ineff= 2 , 0
               0   28.58     7.3           28.18
Permanent Ineff=
       F       F
Bank Sta=0,7.3
XS Rating Curve= 0
Exp/Cntr=.3,.1

Type RM Length L Ch R = 1 ,33.043  ,17,17,17
#Sta/Elev= 6
     -10   28.23       0   28.23       0   26.63       5   26.63       5   28.23
      15   28.23
#Mann= 3 , 0 , 0
     -10    .035       0       0    .035       0       5    .035       0
#XS Ineff= 2 , 0
               0   28.23       5           28.23
Permanent Ineff=
       F       F
Bank Sta=0,5
XS Rating Curve= 0
Exp/Cntr=.3,.1

Type RM Length L Ch R = 1 ,33.026  ,26,26,26
#Sta/Elev= 14
     -10   28.46       0   28.46     1.9   26.76     4.5   26.76     5.5   26.26
     6.9   26.26     6.9   25.76       8   25.76       8   26.26     9.6   26.26
    10.7   27.46    11.3   27.46      12   26.76      22   26.76
#Mann= 3 , 0 , 0
     -10    .035       0     4.5    .035       0    10.7    .035       0
Levee=-1,4.5,26.76,-1,10.7,30,,
#XS Ineff= 2 , 0
       0     4.5   26.76    10.7       0   27.46
Permanent Ineff=
       F       F
Bank Sta=4.5,10.7
XS Rating Curve= 0
Exp/Cntr=.3,.1

Type RM Length L Ch R = 1 ,33      ,50,50,50
#Sta/Elev= 14
   -14.5   27.75    -4.5   27.75    -2.6   26.05       0   26.05       1   25.55
     2.4   25.55     2.4   25.15     3.5   25.15     3.5   25.55     5.1   25.55
     6.2   26.55     6.8   26.55     7.5   25.85    17.5   25.85
#Mann= 3 , 0 , 0
   -14.5    .035       0       0    .035       0     6.2    .035       0
Levee=-1,0,26.05,-1,6.2,30,,
#XS Ineff= 2 , 0
               0   26.05     6.2           26.55
Permanent Ineff=
       F       F
Bank Sta=0,6.2
XS Rating Curve= 0
Exp/Cntr=.3,.1

Type RM Length L Ch R = 1 ,32      ,50,50,50
#Sta/Elev= 7
     -13   26.72      -3   26.72       0   24.72     1.7   24.12       3   24.12
     4.5   24.82    14.5   24.82
#Mann= 3 , 0 , 0
     -13    .035       0      -3    .035       0     4.5    .035       0
Levee=-1,-3,26.72,-1,4.5,30,,
#XS Ineff= 2 , 0
       0      -3   26.72     4.5       0   24.82
Permanent Ineff=
       F       F
Bank Sta=-3,4.5
XS Rating Curve= 0
Exp/Cntr=.3,.1

Type RM Length L Ch R = 1 ,31      ,50,50,50
#Sta/Elev= 7
     -13    25.4      -3    25.4       0    23.4     1.7    22.8       3    22.8
     4.5    23.8    14.5    23.8
#Mann= 3 , 0 , 0
     -13    .035       0      -3    .035       0     4.5    .035       0
Levee=-1,-3,25.4,-1,4.5,30,,
#XS Ineff= 2 , 0
       0      -3    25.4     4.5       0    23.8
Permanent Ineff=
       F       F
Bank Sta=-3,4.5
XS Rating Curve= 0
Exp/Cntr=.3,.1

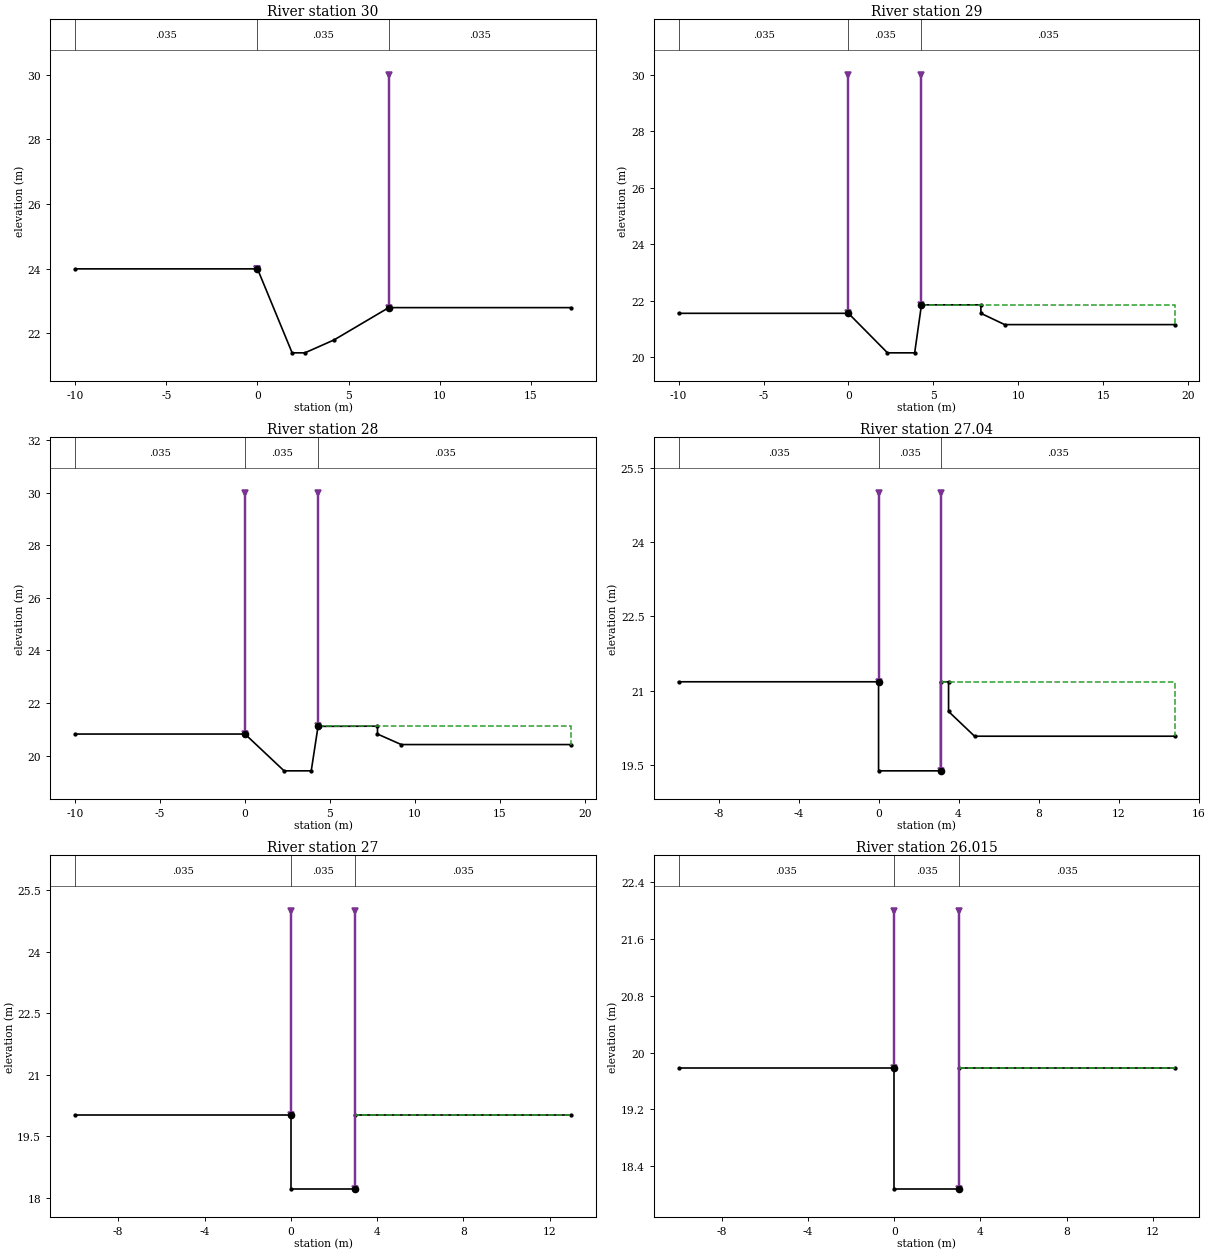
Type RM Length L Ch R = 1 ,30      ,50,50,50
#Sta/Elev= 7
     -10   23.99       0   23.99     1.9   21.39     2.6   21.39     4.2   21.79
     7.2   22.79    17.2   22.79
#Mann= 3 , 0 , 0
     -10    .035       0       0    .035       0     7.2    .035       0
Levee=-1,0,23.99,-1,7.2,30,,
#XS Ineff= 2 , 0
               0   23.99     7.2           22.79
Permanent Ineff=
       F       F
Bank Sta=0,7.2
XS Rating Curve= 0
Exp/Cntr=.3,.1

Type RM Length L Ch R = 1 ,29      ,50,50,50
#Sta/Elev= 9
     -10   21.55       0   21.55     2.3   20.15     3.9   20.15     4.3   21.85
     7.8   21.85     7.8   21.55     9.2   21.15    19.2   21.15
#Mann= 3 , 0 , 0
     -10    .035       0       0    .035       0     4.3    .035       0
Levee=-1,0,30,-1,4.3,30,,
#XS Ineff= 2 , 0
               0   21.55     4.3           21.85
Permanent Ineff=
       F       F
Bank Sta=0,4.3
XS Rating Curve= 0
Exp/Cntr=.3,.1

Type RM Length L Ch R = 1 ,28      ,10,10,10
#Sta/Elev= 9
     -10   20.82       0   20.82     2.3   19.42     3.9   19.42     4.3  21.112
     7.8   21.12     7.8   20.82     9.2   20.42    19.2   20.42
#Mann= 3 , 0 , 0
     -10    .035       0       0    .035       0     4.3    .035       0
Levee=-1,0,30,-1,4.3,30,,
#XS Ineff= 2 , 0
               0   20.82     4.3          21.112
Permanent Ineff=
       F       F
Bank Sta=0,4.3
XS Rating Curve= 0
Exp/Cntr=.3,.1

Type RM Length L Ch R = 1 ,27.04   ,40,40,40
#Sta/Elev= 9
     -10   21.18       0   21.18       0   19.38     3.1   19.38     3.1   21.18
     3.5   21.18     3.5   20.58     4.8   20.08    14.8   20.08
#Mann= 3 , 0 , 0
     -10    .035       0       0    .035       0     3.1    .035       0
Levee=-1,0,25,-1,3.1,25,,
#XS Ineff= 2 , 0
               0   21.18     3.1           21.18
Permanent Ineff=
       F       F
Bank Sta=0,3.1
XS Rating Curve= 0
Exp/Cntr=.3,.1

Type RM Length L Ch R = 1 ,27      ,35,35,35
#Sta/Elev= 6
     -10   20.02       0   20.02       0   18.22       3   18.22       3   20.02
      13   20.02
#Mann= 3 , 0 , 0
     -10    .035       0       0    .035       0       3    .035       0
Levee=-1,0,25,-1,3,25,,
#XS Ineff= 2 , 0
               0   20.02       3           20.02
Permanent Ineff=
       F       F
Bank Sta=0,3
XS Rating Curve= 0
Exp/Cntr=.3,.1

Type RM Length L Ch R = 1 ,26.015  ,15,15,15
#Sta/Elev= 6
     -10   19.78       0   19.78       0   18.08       3   18.08       3   19.78
      13   19.78
#Mann= 3 , 0 , 0
     -10    .035       0       0    .035       0       3    .035       0
Levee=-1,0,22,-1,3,22,,
#XS Ineff= 2 , 0
               0   19.78       3           19.78
Permanent Ineff=
       F       F
Bank Sta=0,3
XS Rating Curve= 0
Exp/Cntr=.3,.1

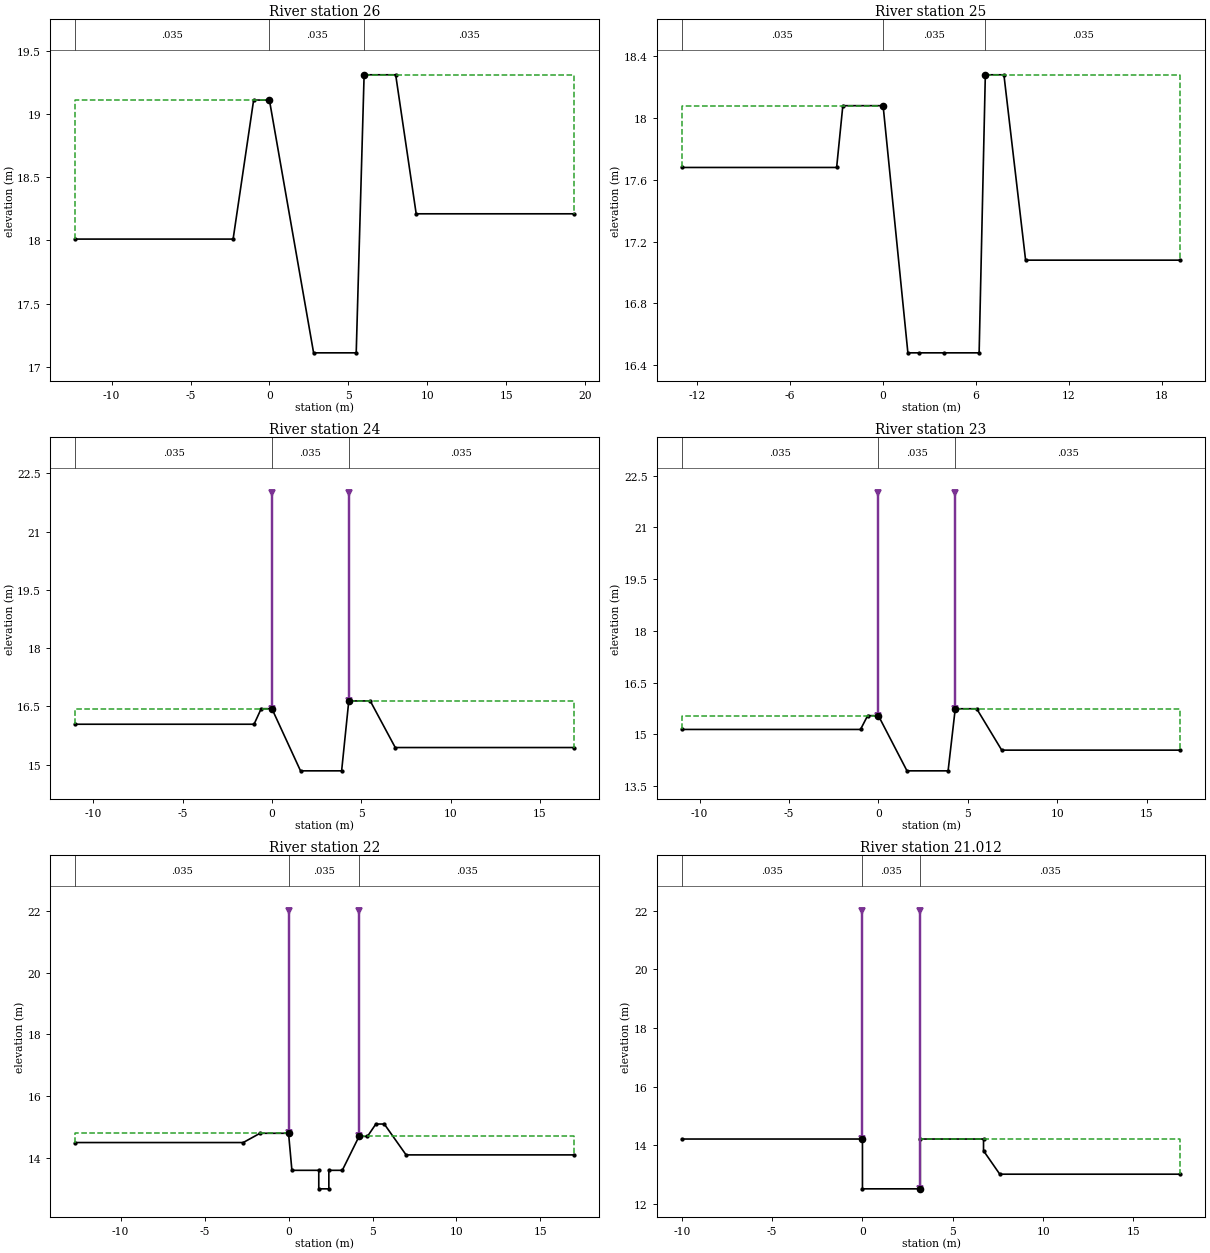
Type RM Length L Ch R = 1 ,26      ,50,50,50
#Sta/Elev= 10
   -12.3   18.01    -2.3   18.01      -1   19.11       0   19.11     2.8   17.11
     5.5   17.11       6   19.31       8   19.31     9.3   18.21    19.3   18.21
#Mann= 3 , 0 , 0
   -12.3    .035       0       0    .035       0       6    .035       0
#XS Ineff= 2 , 0
               0   19.11       6           19.31
Permanent Ineff=
       F       F
Bank Sta=0,6
XS Rating Curve= 0
Exp/Cntr=.3,.1

Type RM Length L Ch R = 1 ,25      ,50,50,50
#Sta/Elev= 12
     -13   17.68      -3   17.68    -2.6   18.08       0   18.08     1.6   16.48
     2.3   16.48     3.9   16.48     6.2   16.48     6.6   18.28     7.8   18.28
     9.2   17.08    19.2   17.08
#Mann= 3 , 0 , 0
     -13    .035       0       0    .035       0     6.6    .035       0
#XS Ineff= 2 , 0
               0   18.08     6.6           18.28
Permanent Ineff=
       F       F
Bank Sta=0,6.6
XS Rating Curve= 0
Exp/Cntr=.3,.1

Type RM Length L Ch R = 1 ,24      ,50,50,50
#Sta/Elev= 10
     -11   16.04      -1   16.04     -.6   16.44       0   16.44     1.6   14.84
     3.9   14.84     4.3   16.64     5.5   16.64     6.9   15.44    16.9   15.44
#Mann= 3 , 0 , 0
     -11    .035       0       0    .035       0     4.3    .035       0
Levee=-1,0,22,-1,4.3,22,,
#XS Ineff= 2 , 0
               0   16.44     4.3           16.64
Permanent Ineff=
       F       F
Bank Sta=0,4.3
XS Rating Curve= 0
Exp/Cntr=.3,.1

Type RM Length L Ch R = 1 ,23      ,50,50,50
#Sta/Elev= 10
     -11   15.14      -1   15.14     -.6   15.54       0   15.54     1.6   13.94
     3.9   13.94     4.3   15.74     5.5   15.74     6.9   14.54    16.9   14.54
#Mann= 3 , 0 , 0
     -11    .035       0       0    .035       0     4.3    .035       0
Levee=-1,0,22,-1,4.3,22,,
#XS Ineff= 2 , 0
               0   15.54     4.3           15.74
Permanent Ineff=
       F       F
Bank Sta=0,4.3
XS Rating Curve= 0
Exp/Cntr=.3,.1

Type RM Length L Ch R = 1 ,22      ,38,38,38
#Sta/Elev= 16
   -12.7   14.49    -2.7   14.49    -1.7   14.79       0   14.79      .2   13.59
     1.8   13.59     1.8   12.99     2.4   12.99     2.4   13.59     3.2   13.59
     4.2   14.69     4.7   14.69     5.2   15.09     5.7   15.09       7   14.09
      17   14.09
#Mann= 3 , 0 , 0
   -12.7    .035       0       0    .035       0     4.2    .035       0
Levee=-1,0,22,-1,4.2,22,,
#XS Ineff= 2 , 0
               0   14.79     4.2           14.69
Permanent Ineff=
       F       F
Bank Sta=0,4.2
XS Rating Curve= 0
Exp/Cntr=.3,.1

Type RM Length L Ch R = 1 ,21.012  ,12,12,12
#Sta/Elev= 9
     -10   14.21       0   14.21       0   12.51     3.2   12.51     3.2   14.21
     6.7   14.21     6.7   13.81     7.6   13.01    17.6   13.01
#Mann= 3 , 0 , 0
     -10    .035       0       0    .035       0     3.2    .035       0
Levee=-1,0,22,-1,3.2,22,,
#XS Ineff= 2 , 0
               0   14.21     3.2           14.21
Permanent Ineff=
       F       F
Bank Sta=0,3.2
XS Rating Curve= 0
Exp/Cntr=.3,.1

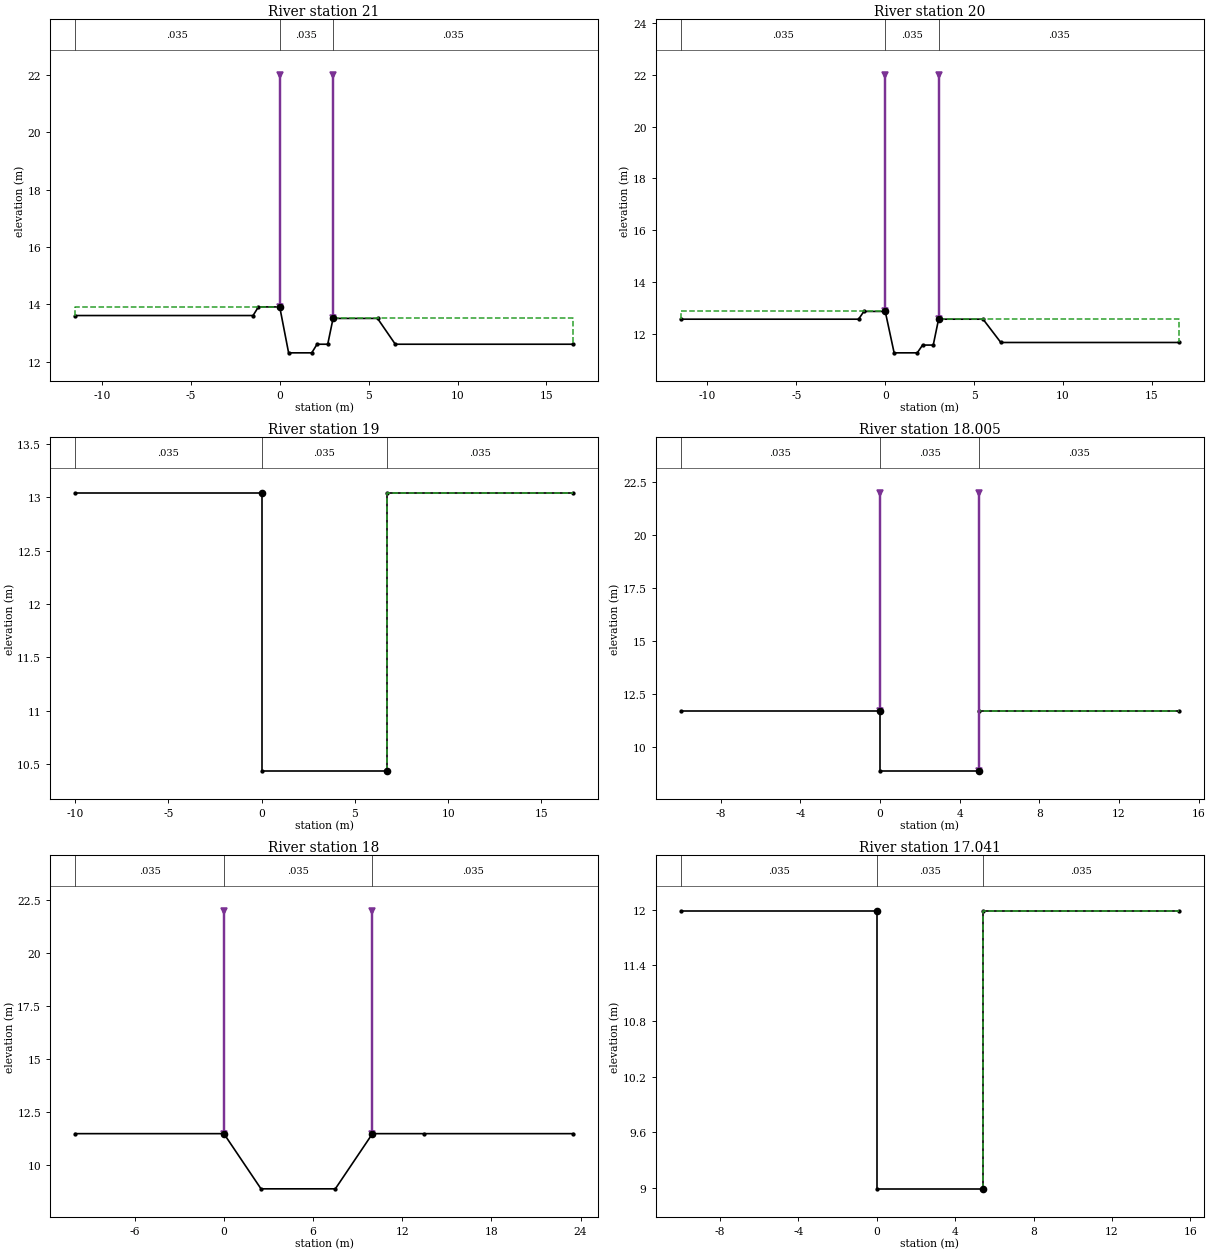
Type RM Length L Ch R = 1 ,21      ,50,50,50
#Sta/Elev= 12
   -11.5   13.61    -1.5   13.61    -1.2   13.91       0   13.91      .5   12.31
     1.8   12.31     2.1   12.61     2.7   12.61       3   13.51     5.5   13.51
     6.5   12.61    16.5   12.61
#Mann= 3 , 0 , 0
   -11.5    .035       0       0    .035       0       3    .035       0
Levee=-1,0,22,-1,3,22,,
#XS Ineff= 2 , 0
               0   13.91       3           13.51
Permanent Ineff=
       F       F
Bank Sta=0,3
XS Rating Curve= 0
Exp/Cntr=.3,.1

Type RM Length L Ch R = 1 ,20      ,50,50,50
#Sta/Elev= 12
   -11.5   12.56    -1.5   12.56    -1.2   12.86       0   12.86      .5   11.26
     1.8   11.26     2.1   11.56     2.7   11.56       3   12.56     5.5   12.56
     6.5   11.66    16.5   11.66
#Mann= 3 , 0 , 0
   -11.5    .035       0       0    .035       0       3    .035       0
Levee=-1,0,22,-1,3,22,,
#XS Ineff= 2 , 0
               0   12.86       3           12.56
Permanent Ineff=
       F       F
Bank Sta=0,3
XS Rating Curve= 0
Exp/Cntr=.3,.1

Type RM Length L Ch R = 1 ,19      ,45,45,45
#Sta/Elev= 6
     -10   13.04       0   13.04       0   10.44     6.7   10.44     6.7   13.04
    16.7   13.04
#Mann= 3 , 0 , 0
     -10    .035       0       0    .035       0     6.7    .035       0
#XS Ineff= 2 , 0
               0   13.04     6.7           13.04
Permanent Ineff=
       F       F
Bank Sta=0,6.7
XS Rating Curve= 0
Exp/Cntr=.3,.1

Type RM Length L Ch R = 1 ,18.005  ,5,5,5
#Sta/Elev= 6
     -10   11.69       0   11.69       0    8.89       5    8.89       5   11.69
      15   11.69
#Mann= 3 , 0 , 0
     -10    .035       0       0    .035       0       5    .035       0
Levee=-1,0,22,-1,5,22,,
#XS Ineff= 2 , 0
               0   11.69       5           11.69
Permanent Ineff=
       F       F
Bank Sta=0,5
XS Rating Curve= 0
Exp/Cntr=.3,.1

Type RM Length L Ch R = 1 ,18      ,9,9,9
#Sta/Elev= 7
     -10    11.5       0    11.5     2.5     8.9     7.5     8.9      10    11.5
    13.5    11.5    23.5    11.5
#Mann= 3 , 0 , 0
     -10    .035       0       0    .035       0      10    .035       0
Levee=-1,0,22,-1,10,22,,
#XS Ineff= 2 , 0
               0    11.5      10            11.5
Permanent Ineff=
       F       F
Bank Sta=0,10
XS Rating Curve= 0
Exp/Cntr=.3,.1

Type RM Length L Ch R = 1 ,17.041  ,17,17,17
#Sta/Elev= 6
     -10   11.99       0   11.99       0    8.99     5.4    8.99     5.4   11.99
    15.4   11.99
#Mann= 3 , 0 , 0
     -10    .035       0       0    .035       0     5.4    .035       0
#XS Ineff= 2 , 0
               0   11.99     5.4           11.99
Permanent Ineff=
       F       F
Bank Sta=0,5.4
XS Rating Curve= 0
Exp/Cntr=.3,.1

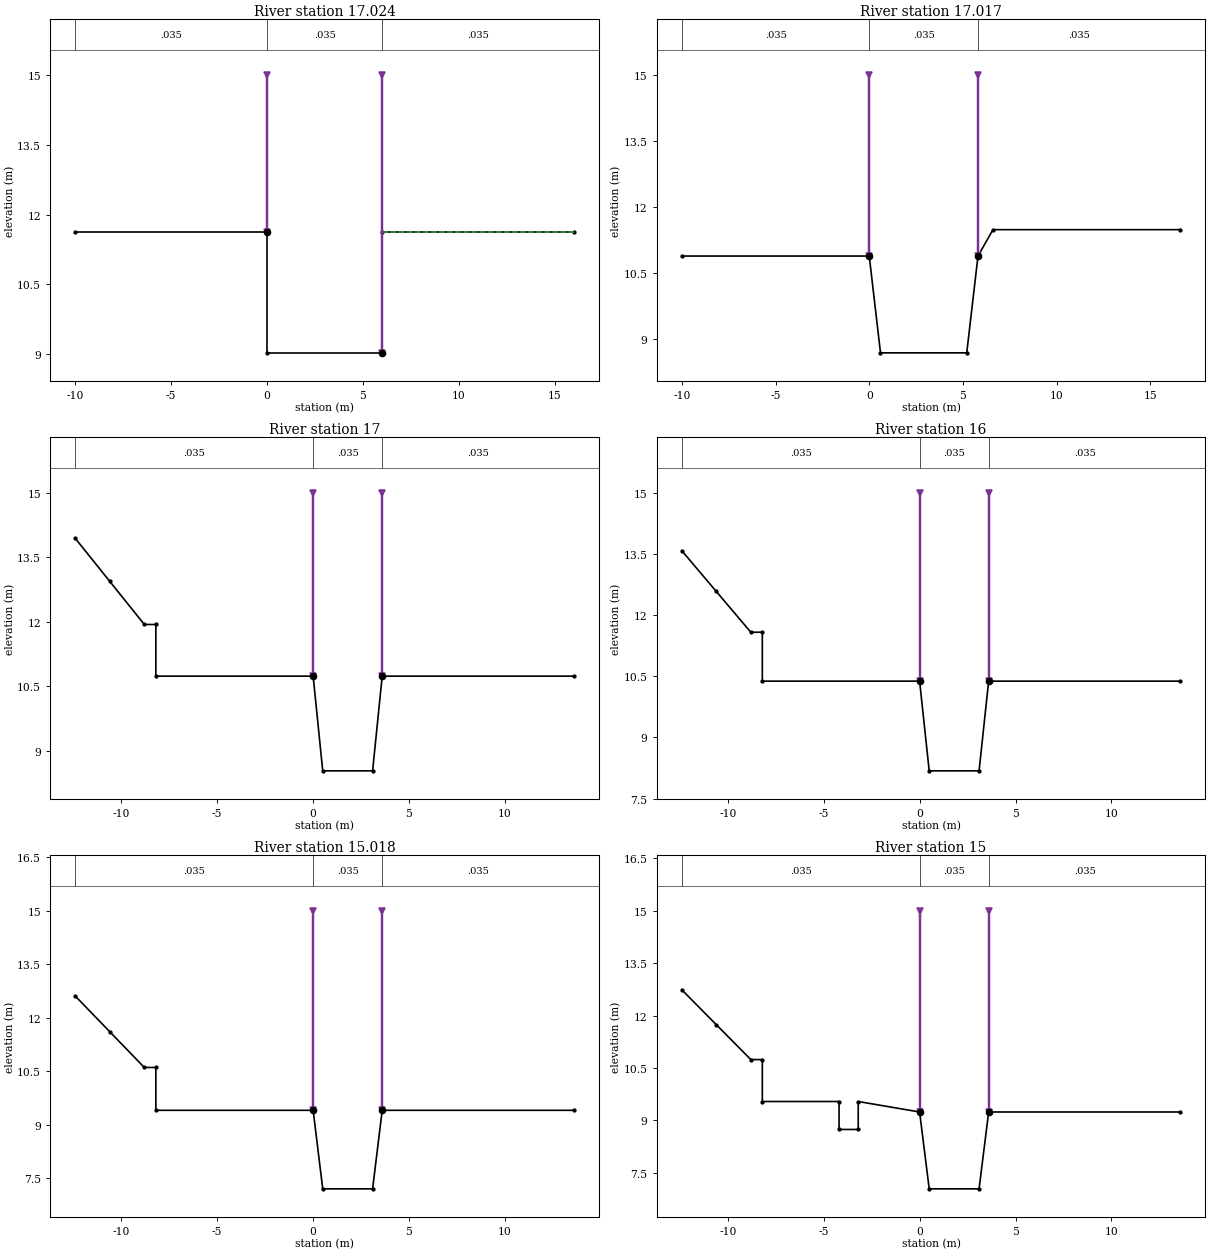
Type RM Length L Ch R = 1 ,17.024  ,33,33,33
#Sta/Elev= 6
     -10   11.63       0   11.63       0    9.03       6    9.03       6   11.63
      16   11.63
#Mann= 3 , 0 , 0
     -10    .035       0       0    .035       0       6    .035       0
Levee=-1,0,15,-1,6,15,,
#XS Ineff= 2 , 0
               0   11.63       6           11.63
Permanent Ineff=
       F       F
Bank Sta=0,6
XS Rating Curve= 0
Exp/Cntr=.3,.1

Type RM Length L Ch R = 1 ,17.017  ,17,17,17
#Sta/Elev= 7
     -10   10.88       0   10.88      .6    8.68     5.2    8.68     5.8   10.88
     6.6   11.48    16.6   11.48
#Mann= 3 , 0 , 0
     -10    .035       0       0    .035       0     5.8    .035       0
Levee=-1,0,15,-1,5.8,15,,
#XS Ineff= 2 , 0
               0   10.88     5.8           10.88
Permanent Ineff=
       F       F
Bank Sta=0,5.8
XS Rating Curve= 0
Exp/Cntr=.3,.1

Type RM Length L Ch R = 1 ,17      ,50,50,50
#Sta/Elev= 10
   -12.4   13.94   -10.6   12.94    -8.8   11.94    -8.2   11.94    -8.2   10.74
       0   10.74      .5    8.54     3.1    8.54     3.6   10.74    13.6   10.74
#Mann= 3 , 0 , 0
   -12.4    .035       0       0    .035       0     3.6    .035       0
Levee=-1,0,15,-1,3.6,15,,
#XS Ineff= 2 , 0
               0   10.74     3.6           10.74
Permanent Ineff=
       F       F
Bank Sta=0,3.6
XS Rating Curve= 0
Exp/Cntr=.3,.1

Type RM Length L Ch R = 1 ,16      ,32,32,32
#Sta/Elev= 10
   -12.4   13.58   -10.6   12.58    -8.8   11.58    -8.2   11.58    -8.2   10.38
       0   10.38      .5    8.18     3.1    8.18     3.6   10.38    13.6   10.38
#Mann= 3 , 0 , 0
   -12.4    .035       0       0    .035       0     3.6    .035       0
Levee=-1,0,15,-1,3.6,15,,
#XS Ineff= 2 , 0
               0   10.38     3.6           10.38
Permanent Ineff=
       F       F
Bank Sta=0,3.6
XS Rating Curve= 0
Exp/Cntr=.3,.1

Type RM Length L Ch R = 1 ,15.018  ,18,18,18
#Sta/Elev= 10
   -12.4   12.61   -10.6   11.61    -8.8   10.61    -8.2   10.61    -8.2    9.41
       0    9.41      .5    7.21     3.1    7.21     3.6    9.41    13.6    9.41
#Mann= 3 , 0 , 0
   -12.4    .035       0       0    .035       0     3.6    .035       0
Levee=-1,0,15,-1,3.6,15,,
#XS Ineff= 2 , 0
               0    9.41     3.6            9.41
Permanent Ineff=
       F       F
Bank Sta=0,3.6
XS Rating Curve= 0
Exp/Cntr=.3,.1

Type RM Length L Ch R = 1 ,15      ,50,50,50
#Sta/Elev= 14
   -12.4   12.74   -10.6   11.74    -8.8   10.74    -8.2   10.74    -8.2    9.54
    -4.2    9.54    -4.2    8.74    -3.2    8.74    -3.2    9.54       0    9.24
      .5    7.04     3.1    7.04     3.6    9.24    13.6    9.24
#Mann= 3 , 0 , 0
   -12.4    .035       0       0    .035       0     3.6    .035       0
Levee=-1,0,15,-1,3.6,15,,
#XS Ineff= 2 , 0
               0    9.24     3.6            9.24
Permanent Ineff=
       F       F
Bank Sta=0,3.6
XS Rating Curve= 0
Exp/Cntr=.3,.1