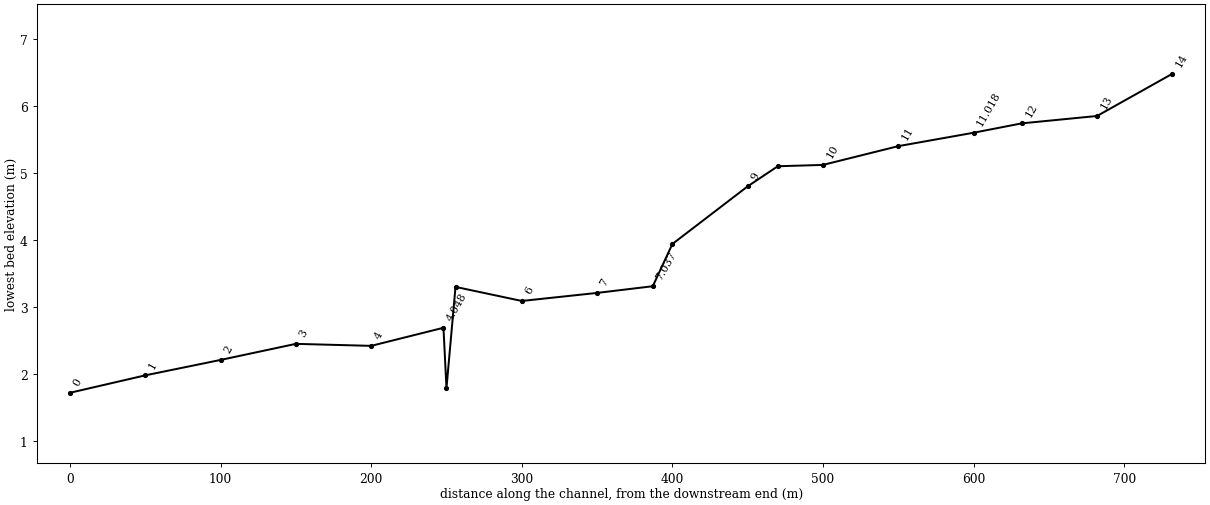
HEC-RAS study EJC.prj: eucje-ch

--- EJC.g01 (geometry) --- (continued)

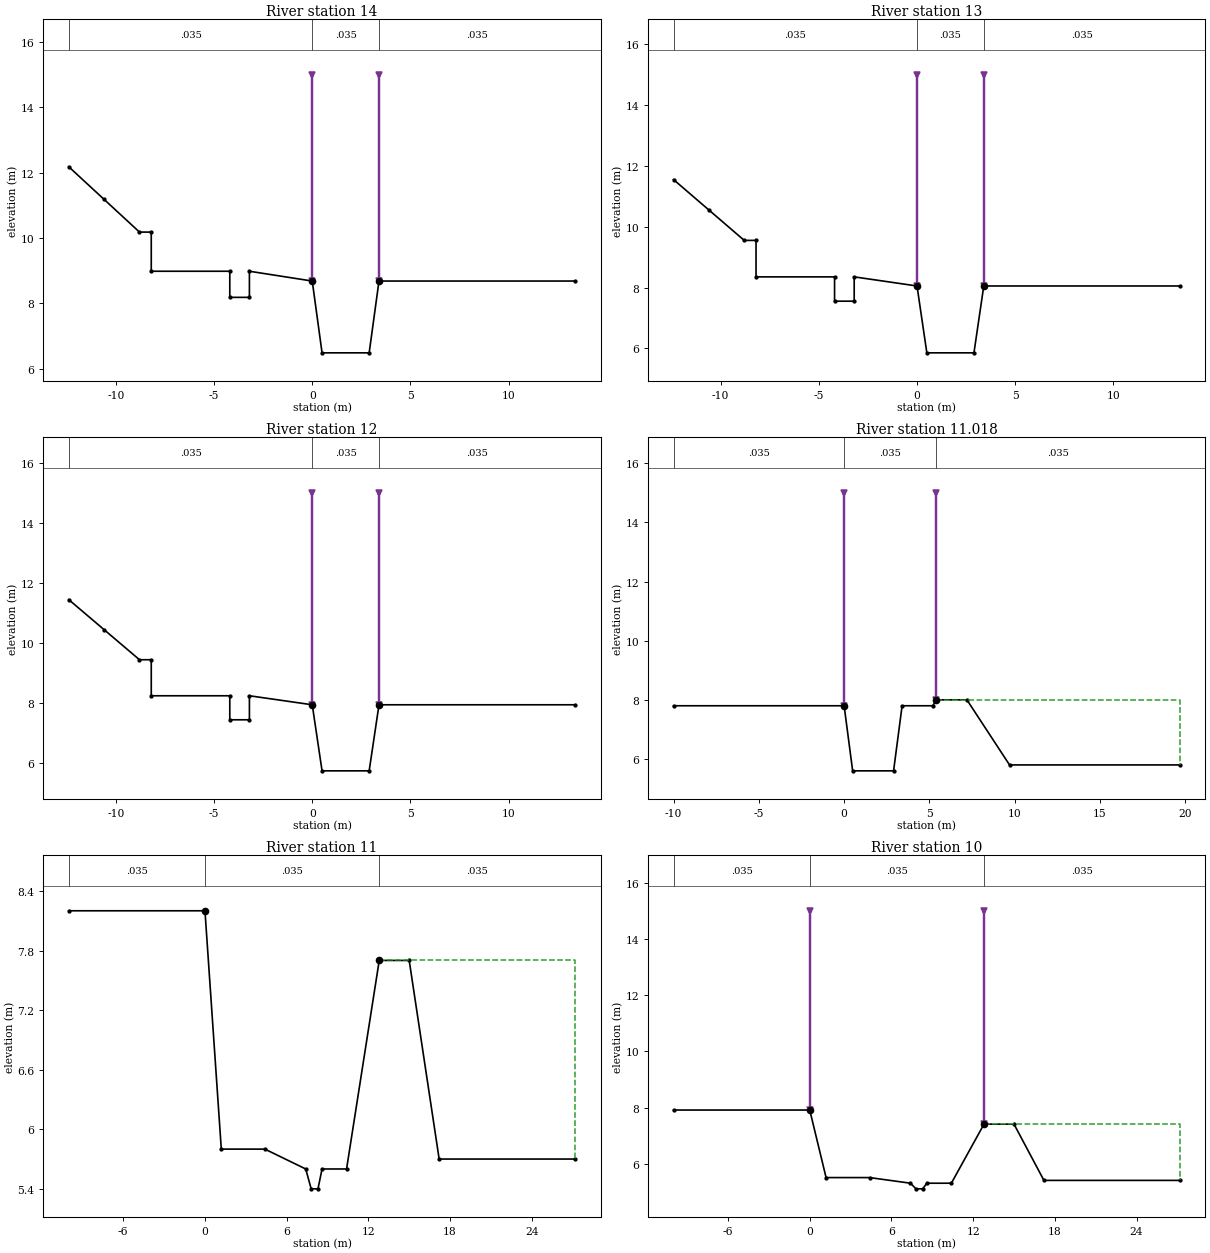
Type RM Length L Ch R = 1 ,14      ,50,50,50
#Sta/Elev= 14
   -12.4   12.18   -10.6   11.18    -8.8   10.18    -8.2   10.18    -8.2    8.98
    -4.2    8.98    -4.2    8.18    -3.2    8.18    -3.2    8.98       0    8.68
      .5    6.48     2.9    6.48     3.4    8.68    13.4    8.68
#Mann= 3 , 0 , 0
   -12.4    .035       0       0    .035       0     3.4    .035       0
Levee=-1,0,15,-1,3.4,15,,
#XS Ineff= 2 , 0
               0    8.68     3.4            8.68
Permanent Ineff=
       F       F
Bank Sta=0,3.4
XS Rating Curve= 0
Exp/Cntr=.3,.1

Type RM Length L Ch R = 1 ,13      ,50,50,50
#Sta/Elev= 14
   -12.4   11.55   -10.6   10.55    -8.8    9.55    -8.2    9.55    -8.2    8.35
    -4.2    8.35    -4.2    7.55    -3.2    7.55    -3.2    8.35       0    8.05
      .5    5.85     2.9    5.85     3.4    8.05    13.4    8.05
#Mann= 3 , 0 , 0
   -12.4    .035       0       0    .035       0     3.4    .035       0
Levee=-1,0,15,-1,3.4,15,,
#XS Ineff= 2 , 0
               0    8.05     3.4            8.05
Permanent Ineff=
       F       F
Bank Sta=0,3.4
XS Rating Curve= 0
Exp/Cntr=.3,.1

Type RM Length L Ch R = 1 ,12      ,32,32,32
#Sta/Elev= 14
   -12.4   11.44   -10.6   10.44    -8.8    9.44    -8.2    9.44    -8.2    8.24
    -4.2    8.24    -4.2    7.44    -3.2    7.44    -3.2    8.24       0    7.94
      .5    5.74     2.9    5.74     3.4    7.94    13.4    7.94
#Mann= 3 , 0 , 0
   -12.4    .035       0       0    .035       0     3.4    .035       0
Levee=-1,0,15,-1,3.4,15,,
#XS Ineff= 2 , 0
               0    7.94     3.4            7.94
Permanent Ineff=
       F       F
Bank Sta=0,3.4
XS Rating Curve= 0
Exp/Cntr=.3,.1

Type RM Length L Ch R = 1 ,11.018  ,50,50,50
#Sta/Elev= 10
     -10     7.8       0     7.8      .5     5.6     2.9     5.6     3.4     7.8
     5.2     7.8     5.4       8     7.2       8     9.7     5.8    19.7     5.8
#Mann= 3 , 0 , 0
     -10    .035       0       0    .035       0     5.4    .035       0
Levee=-1,0,15,-1,5.4,15,,
#XS Ineff= 2 , 0
               0     7.8     5.4               8
Permanent Ineff=
       F       F
Bank Sta=0,5.4
XS Rating Curve= 0
Exp/Cntr=.3,.1

Type RM Length L Ch R = 1 ,11      ,50,50,50
#Sta/Elev= 13
     -10     8.2       0     8.2     1.2     5.8     4.4     5.8     7.4     5.6
     7.8     5.4     8.3     5.4     8.6     5.6    10.4     5.6    12.8     7.7
      15     7.7    17.2     5.7    27.2     5.7
#Mann= 3 , 0 , 0
     -10    .035       0       0    .035       0    12.8    .035       0
#XS Ineff= 2 , 0
               0     8.2    12.8             7.7
Permanent Ineff=
       F       F
Bank Sta=0,12.8
XS Rating Curve= 0
Exp/Cntr=.3,.1

Type RM Length L Ch R = 1 ,10      ,30,30,30
#Sta/Elev= 13
     -10    7.92       0    7.92     1.2    5.52     4.4    5.52     7.4    5.32
     7.8    5.12     8.3    5.12     8.6    5.32    10.4    5.32    12.8    7.42
      15    7.42    17.2    5.42    27.2    5.42
#Mann= 3 , 0 , 0
     -10    .035       0       0    .035       0    12.8    .035       0
Levee=-1,0,15,-1,12.8,15,,
#XS Ineff= 2 , 0
               0    7.92    12.8            7.42
Permanent Ineff=
       F       F
Bank Sta=0,12.8
XS Rating Curve= 0
Exp/Cntr=.3,.1

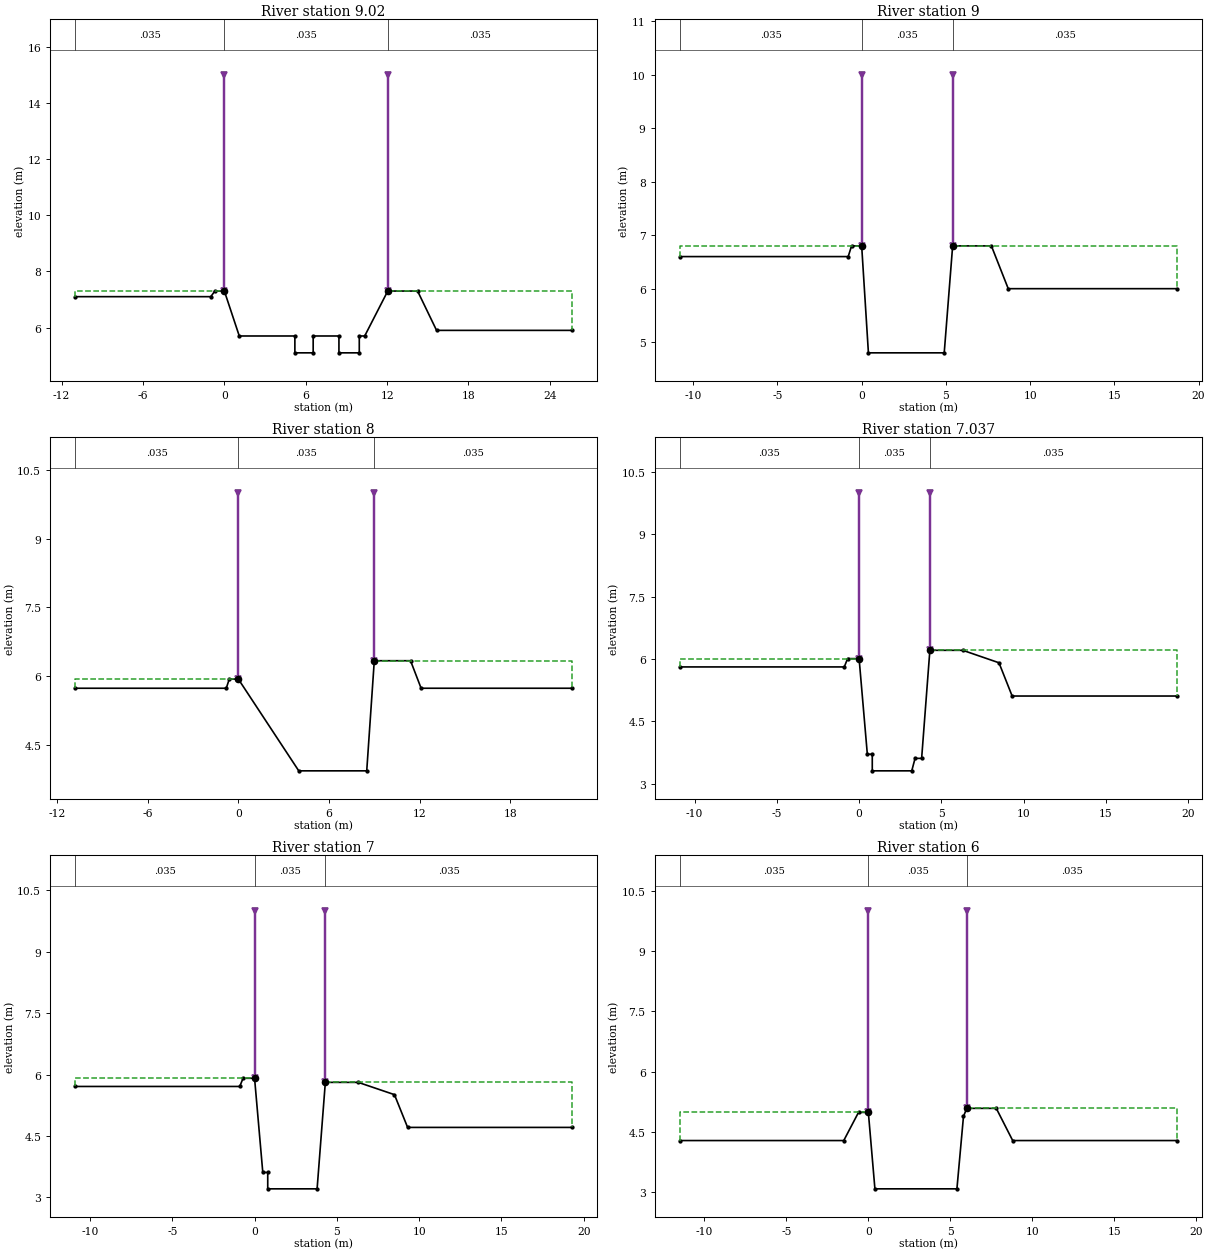
Type RM Length L Ch R = 1 ,9.02    ,20,20,20
#Sta/Elev= 18
     -11     7.1      -1     7.1     -.7     7.3       0     7.3     1.1     5.7
     5.2     5.7     5.2     5.1    6.55     5.1    6.55     5.7    8.45     5.7
    8.45     5.1    9.95     5.1    9.95     5.7   10.35     5.7   12.05     7.3
   14.25     7.3   15.65     5.9   25.65     5.9
#Mann= 3 , 0 , 0
     -11    .035       0       0    .035       0   12.05    .035       0
Levee=-1,0,15,-1,12.05,15,,
#XS Ineff= 2 , 0
               0     7.3   12.05             7.3
Permanent Ineff=
       F       F
Bank Sta=0,12.05
XS Rating Curve= 0
Exp/Cntr=.3,.1

Type RM Length L Ch R = 1 ,9       ,50,50,50
#Sta/Elev= 10
   -10.8     6.6     -.8     6.6     -.6     6.8       0     6.8      .4     4.8
     4.9     4.8     5.4     6.8     7.7     6.8     8.7       6    18.7       6
#Mann= 3 , 0 , 0
   -10.8    .035       0       0    .035       0     5.4    .035       0
Levee=-1,0,10,-1,5.4,10,,
#XS Ineff= 2 , 0
               0     6.8     5.4             6.8
Permanent Ineff=
       F       F
Bank Sta=0,5.4
XS Rating Curve= 0
Exp/Cntr=.3,.1

Type RM Length L Ch R = 1 ,8       ,13,13,13
#Sta/Elev= 10
   -10.8    5.74     -.8    5.74     -.6    5.94       0    5.94       4    3.94
     8.5    3.94       9    6.34    11.4    6.34    12.1    5.74    22.1    5.74
#Mann= 3 , 0 , 0
   -10.8    .035       0       0    .035       0       9    .035       0
Levee=-1,0,10,-1,9,10,,
#XS Ineff= 2 , 0
               0    5.94       9            6.34
Permanent Ineff=
       F       F
Bank Sta=0,9
XS Rating Curve= 0
Exp/Cntr=.3,.1

Type RM Length L Ch R = 1 ,7.037   ,37,37,37
#Sta/Elev= 15
   -10.9    5.81     -.9    5.81     -.7    6.01       0    6.01      .5    3.71
      .8    3.71      .8    3.31     3.2    3.31     3.4    3.61     3.8    3.61
     4.3    6.21     6.3    6.21     8.5    5.91     9.3    5.11    19.3    5.11
#Mann= 3 , 0 , 0
   -10.9    .035       0       0    .035       0     4.3    .035       0
Levee=-1,0,10,-1,4.3,10,,
#XS Ineff= 2 , 0
               0    6.01     4.3            6.21
Permanent Ineff=
       F       F
Bank Sta=0,4.3
XS Rating Curve= 0
Exp/Cntr=.3,.1

Type RM Length L Ch R = 1 ,7       ,50,50,50
#Sta/Elev= 13
   -10.9    5.71     -.9    5.71     -.7    5.91       0    5.91      .5    3.61
      .8    3.61      .8    3.21     3.8    3.21     4.3    5.81     6.3    5.81
     8.5    5.51     9.3    4.71    19.3    4.71
#Mann= 3 , 0 , 0
   -10.9    .035       0       0    .035       0     4.3    .035       0
Levee=-1,0,10,-1,4.3,10,,
#XS Ineff= 2 , 0
               0    5.91     4.3            5.81
Permanent Ineff=
       F       F
Bank Sta=0,4.3
XS Rating Curve= 0
Exp/Cntr=.3,.1

Type RM Length L Ch R = 1 ,6       ,44,44,44
#Sta/Elev= 11
   -11.5    4.29    -1.5    4.29     -.6    4.99       0    4.99      .4    3.09
     5.4    3.09     5.8    4.89       6    5.09     7.8    5.09     8.8    4.29
    18.8    4.29
#Mann= 3 , 0 , 0
   -11.5    .035       0       0    .035       0       6    .035       0
Levee=-1,0,10,-1,6,10,,
#XS Ineff= 2 , 0
               0    4.99       6            5.09
Permanent Ineff=
       F       F
Bank Sta=0,6
XS Rating Curve= 0
Exp/Cntr=.3,.1

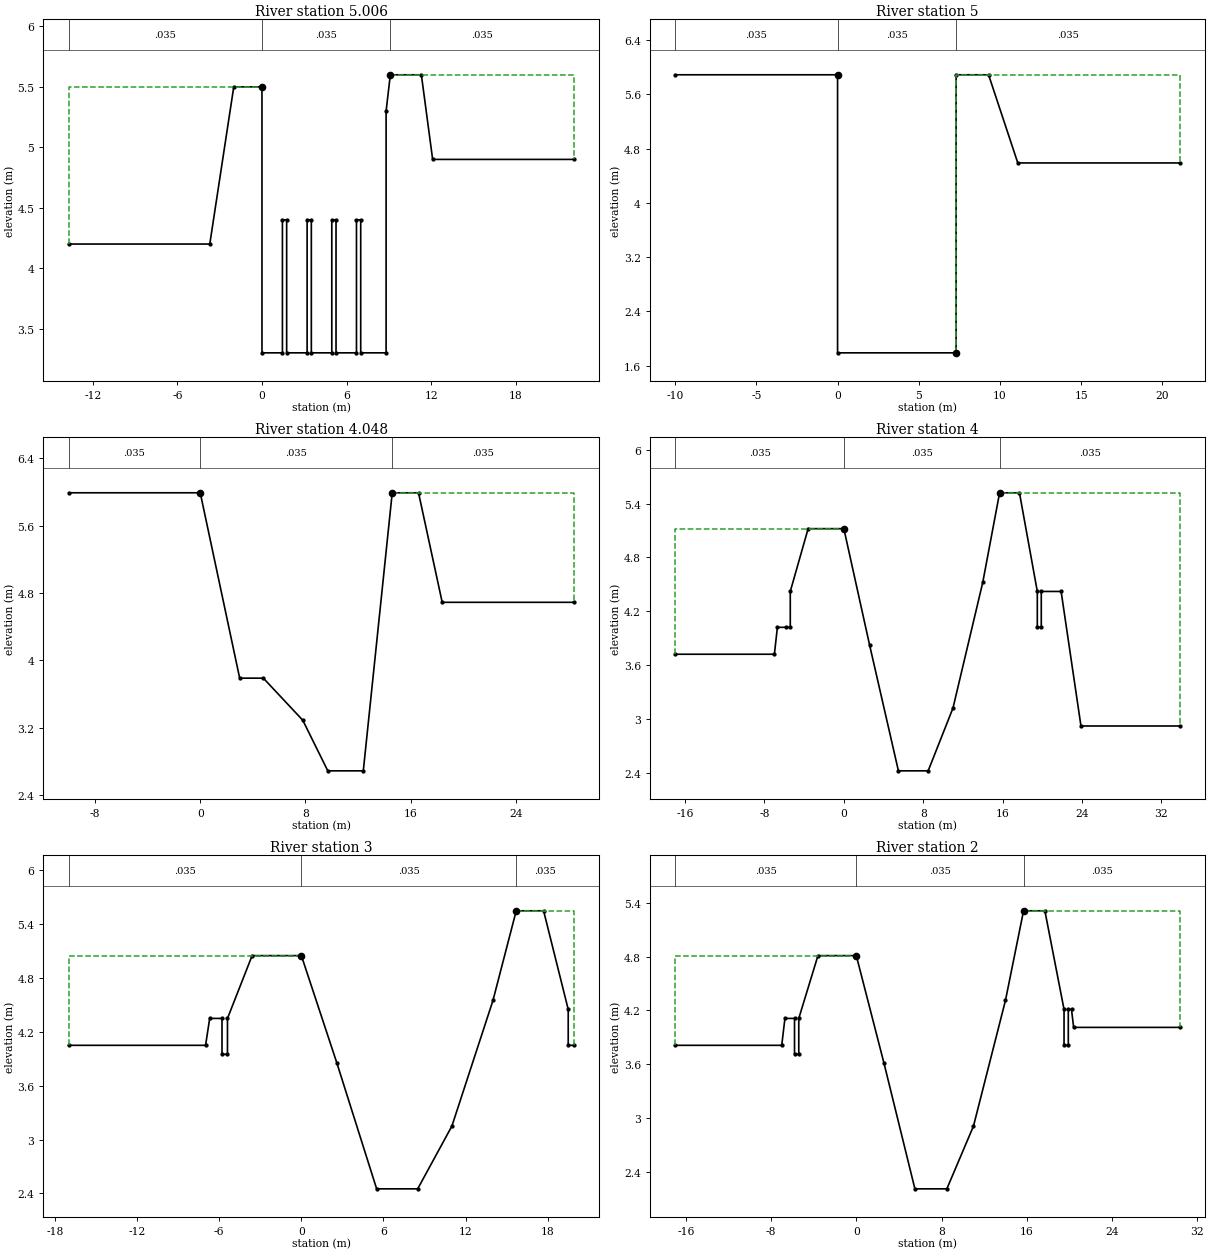
Type RM Length L Ch R = 1 ,5.006   ,6,6,6
#Sta/Elev= 27
   -13.7     4.2    -3.7     4.2      -2     5.5       0     5.5       0     3.3
    1.45     3.3    1.45     4.4    1.75     4.4    1.75     3.3     3.2     3.3
     3.2     4.4     3.5     4.4     3.5     3.3    4.95     3.3    4.95     4.4
    5.25     4.4    5.25     3.3     6.7     3.3     6.7     4.4       7     4.4
       7     3.3     8.8     3.3     8.8     5.3     9.1     5.6    11.3     5.6
    12.1     4.9    22.1     4.9
#Mann= 3 , 0 , 0
   -13.7    .035       0       0    .035       0     9.1    .035       0
#XS Ineff= 2 , 0
               0     5.5     9.1             5.6
Permanent Ineff=
       F       F
Bank Sta=0,9.1
XS Rating Curve= 0
Exp/Cntr=.3,.1

Type RM Length L Ch R = 1 ,5       ,2,2,2
#Sta/Elev= 8
     -10    5.89       0    5.89       0    1.79     7.3    1.79     7.3    5.89
     9.3    5.89    11.1    4.59    21.1    4.59
#Mann= 3 , 0 , 0
     -10    .035       0       0    .035       0     7.3    .035       0
#XS Ineff= 2 , 0
               0    5.89     7.3            5.89
Permanent Ineff=
       F       F
Bank Sta=0,7.3
XS Rating Curve= 0
Exp/Cntr=.3,.1

Type RM Length L Ch R = 1 ,4.048   ,48,48,48
#Sta/Elev= 11
     -10    5.99       0    5.99       3    3.79     4.8    3.79     7.8    3.29
     9.7    2.69    12.4    2.69    14.6    5.99    16.6    5.99    18.4    4.69
    28.4    4.69
#Mann= 3 , 0 , 0
     -10    .035       0       0    .035       0    14.6    .035       0
#XS Ineff= 2 , 0
               0    5.99    14.6            5.99
Permanent Ineff=
       F       F
Bank Sta=0,14.6
XS Rating Curve= 0
Exp/Cntr=.3,.1

Type RM Length L Ch R = 1 ,4       ,50,50,50
#Sta/Elev= 22
     -17    3.72      -7    3.72    -6.7    4.02    -5.8    4.02    -5.4    4.02
    -5.4    4.42    -3.6    5.12       0    5.12     2.6    3.82     5.5    2.42
     8.5    2.42      11    3.12      14    4.52    15.7    5.52    17.7    5.52
    19.5    4.42    19.5    4.02    19.9    4.02    19.9    4.42    21.9    4.42
    23.9    2.92    33.9    2.92
#Mann= 3 , 0 , 0
     -17    .035       0       0    .035       0    15.7    .035       0
#XS Ineff= 2 , 0
               0    5.12    15.7            5.52
Permanent Ineff=
       F       F
Bank Sta=0,15.7
XS Rating Curve= 0
Exp/Cntr=.3,.1

Type RM Length L Ch R = 1 ,3       ,50,50,50
#Sta/Elev= 19
     -17    4.05      -7    4.05    -6.7    4.35    -5.8    4.35    -5.8    3.95
    -5.4    3.95    -5.4    4.35    -3.6    5.05       0    5.05     2.6    3.85
     5.5    2.45     8.5    2.45      11    3.15      14    4.55    15.7    5.55
    17.7    5.55    19.5    4.45    19.5    4.05    19.9    4.05
#Mann= 3 , 0 , 0
     -17    .035       0       0    .035       0    15.7    .035       0
#XS Ineff= 2 , 0
               0    5.05    15.7            5.55
Permanent Ineff=
       F       F
Bank Sta=0,15.7
XS Rating Curve= 0
Exp/Cntr=.3,.1

Type RM Length L Ch R = 1 ,2       ,50,50,50
#Sta/Elev= 23
     -17    3.81      -7    3.81    -6.7    4.11    -5.8    4.11    -5.8    3.71
    -5.4    3.71    -5.4    4.11    -3.6    4.81       0    4.81     2.6    3.61
     5.5    2.21     8.5    2.21      11    2.91      14    4.31    15.7    5.31
    17.7    5.31    19.5    4.21    19.5    3.81    19.9    3.81    19.9    4.21
    20.2    4.21    20.4    4.01    30.4    4.01
#Mann= 3 , 0 , 0
     -17    .035       0       0    .035       0    15.7    .035       0
#XS Ineff= 2 , 0
               0    4.81    15.7            5.31
Permanent Ineff=
       F       F
Bank Sta=0,15.7
XS Rating Curve= 0
Exp/Cntr=.3,.1

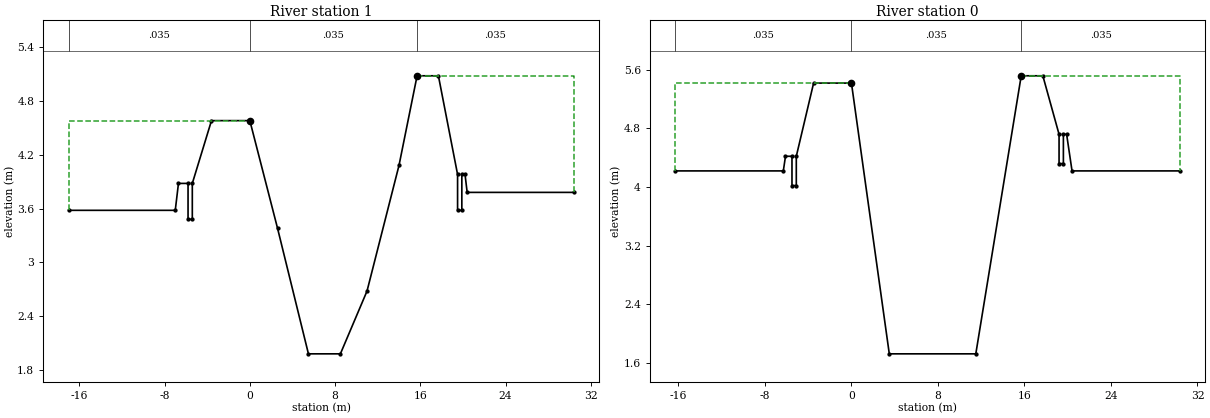
Type RM Length L Ch R = 1 ,1       ,50,50,50
#Sta/Elev= 23
     -17    3.58      -7    3.58    -6.7    3.88    -5.8    3.88    -5.8    3.48
    -5.4    3.48    -5.4    3.88    -3.6    4.58       0    4.58     2.6    3.38
     5.5    1.98     8.5    1.98      11    2.68      14    4.08    15.7    5.08
    17.7    5.08    19.5    3.98    19.5    3.58    19.9    3.58    19.9    3.98
    20.2    3.98    20.4    3.78    30.4    3.78
#Mann= 3 , 0 , 0
     -17    .035       0       0    .035       0    15.7    .035       0
#XS Ineff= 2 , 0
               0    4.58    15.7            5.08
Permanent Ineff=
       F       F
Bank Sta=0,15.7
XS Rating Curve= 0
Exp/Cntr=.3,.1

Type RM Length L Ch R = 1 ,0       ,0,0,0
#Sta/Elev= 20
   -16.3    4.22    -6.3    4.22    -6.1    4.42    -5.5    4.42    -5.5    4.02
    -5.1    4.02    -5.1    4.42    -3.5    5.42       0    5.42     3.5    1.72
    11.5    1.72    15.7    5.52    17.7    5.52    19.2    4.72    19.2    4.32
    19.6    4.32    19.6    4.72    19.9    4.72    20.4    4.22    30.4    4.22
#Mann= 3 , 0 , 0
   -16.3    .035       0       0    .035       0    15.7    .035       0
#XS Ineff= 2 , 0
               0    5.42    15.7            5.52
Permanent Ineff=
       F       F
Bank Sta=0,15.7
XS Rating Curve= 0
Exp/Cntr=.3,.1

Chan Stop Cuts=-1