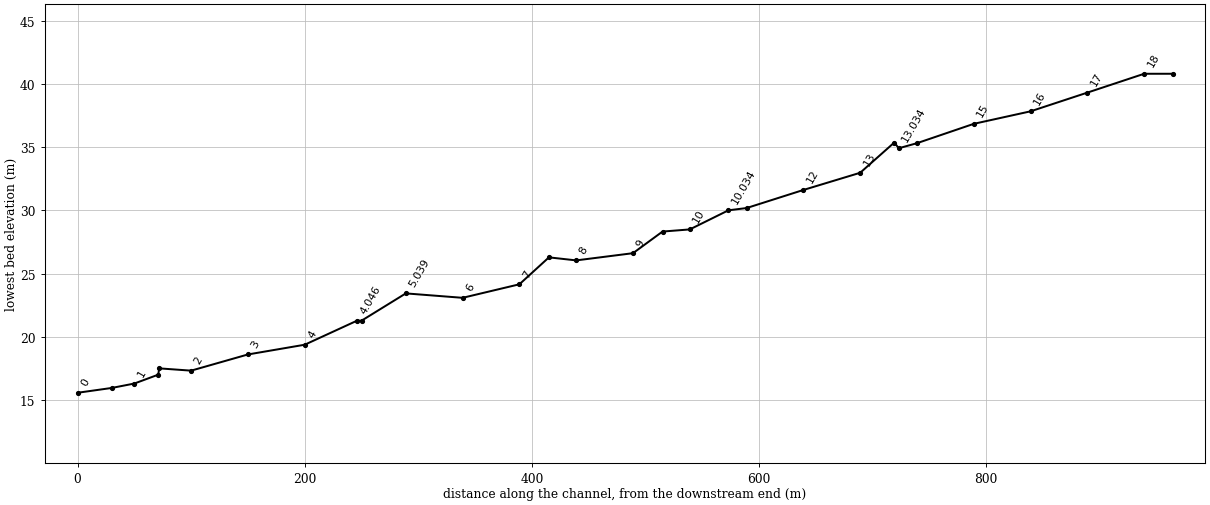
--- NMD.prj (project) ---

Proj Title=namuldong-ch
Current Plan=p01
Default Exp/Contr=.3,.1
SI Units
Geom File=g01
Flow File=f01
Plan File=p01
Y Axis Title=Elevation
X Axis Title(PF)=Main Channel Distance
X Axis Title(XS)=Station
BEGIN DESCRIPTION:
           BACK WATER COMPUTATION
      APPLICATION OF HEC-2 BY Samju Construction Engineering
     namuldong-ch: 10,20,30,50,80 yr
END DESCRIPTION:
DSS Export Rating Curves= 0
DSS Export Rating Curve Sorted= 0
DSS Export Volume Flow Curves= 0
DXF OffsetX= 0
DXF OffsetY= 0
DXF ScaleX= 1
DXF ScaleY= 10

--- NMD.p01 (plan) ---

Plan Title=Imported Plan 01
Version=Version 3.0.1  Mar 2001
Short Identifier=Imported Pla
Geom File=g01
Flow File=f01
Subcritical Flow
K Sum by GR= 0
Std Step Tol= 0.003
Critical Tol= 0.003
Num of Std Step Trials= 20
Max Error Tol= 0.1
Flow Tol Ratio= 0.001
Split Flow NTrial= 30
Split Flow Tol= 0.02
Split Flow Ratio= 0.02
Log Output Level= 0
Friction Slope Method= 1
Unsteady Friction Slope Method= 2
Parabolic Critical Depth
Global Vel Dist= 0 , 0 , 0
Global Log Level= 0
CheckData=True
Encroach Param=-1 ,0,0, 0
Computation Interval=1HOUR
Output Interval=1HOUR
Run HTab= 0
Run UNet= 0
Run PostProcess= 0
UNET Theta= 1
UNET ZTol= 0.02
UNET ZSATol= 0.1
UNET MxIter= 20
UNET MaxInSteps= 20
UNET DtIC= 0
UNET DtMin= 0
UNET MaxCRTS= 20
UNET WFStab= 2
UNET SFStab= 1
UNET WFX= 1
UNET SFX= 1
UNET Convert EG Bridges=-1
UNET Use Existing IB Tables=-1
Instantaneous Interval=1HOUR
Write IC File= 0
Write Velocity= 0
Write Detailed= 0

--- NMD.f01 (steady flow) ---

Flow Title=Imported Flow 01
Version=Version 3.0.1  Mar 2001
Number of Profiles= 5
Profile Names=10YR,20YR,30YR,50YR,80YR
River Rch & RM=RIVER-1,Reach-1         ,18.025
   16.57   18.26   19.25    20.5   21.64
River Rch & RM=NAMULDONG,NAMULDONG       ,18.025
   16.57   18.26   19.25    20.5   21.64
Boundary for River Rch & Prof#=NAMULDONG,NAMULDONG       , 1
Up Type= 0
Dn Type= 3
Dn Slope=.028
Boundary for River Rch & Prof#=NAMULDONG,NAMULDONG       , 2
Up Type= 0
Dn Type= 3
Dn Slope=.028
Boundary for River Rch & Prof#=NAMULDONG,NAMULDONG       , 3
Up Type= 0
Dn Type= 3
Dn Slope=.028
Boundary for River Rch & Prof#=NAMULDONG,NAMULDONG       , 4
Up Type= 0
Dn Type= 3
Dn Slope=.028
Boundary for River Rch & Prof#=NAMULDONG,NAMULDONG       , 5
Up Type= 0
Dn Type= 3
Dn Slope=.028
DSS Import GetInterval= 0
DSS Import GetPeak= 0
DSS Import FillOption= 0

--- NMD.g01 (geometry) ---

Geom Title=Imported Geom 01
Version=Version 3.0.1  Mar 2001

River Reach=NAMULDONG       ,NAMULDONG
Reach XY= 2
              .5             .95              .5             .05

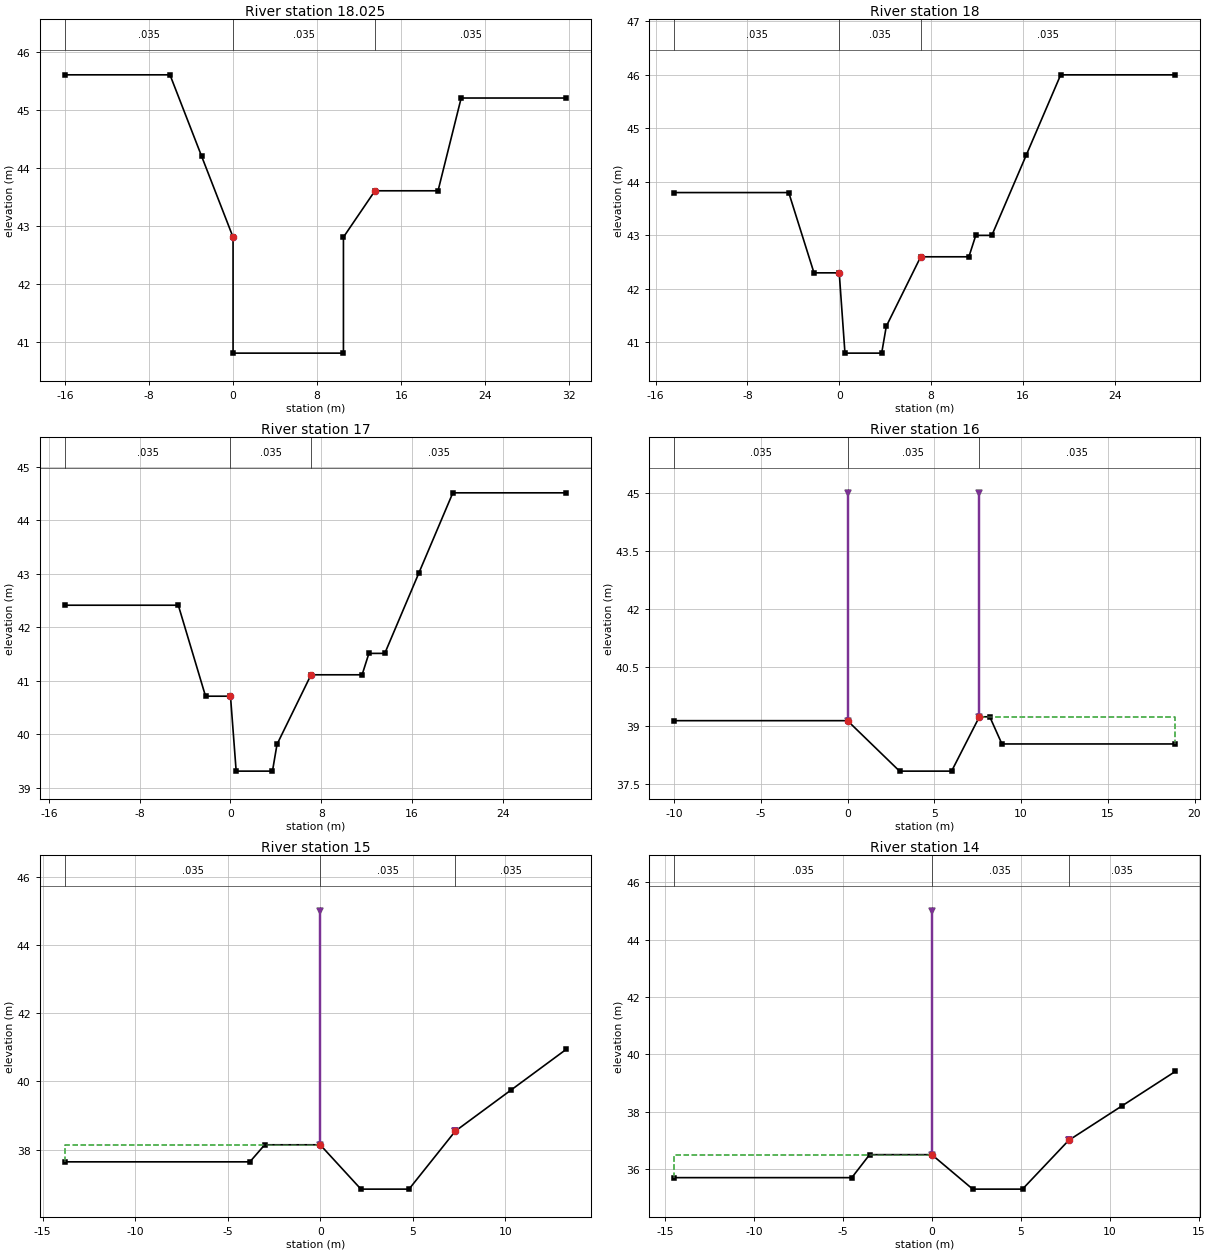
Type RM Length L Ch R = 1 ,18.025  ,25,25,25
#Sta/Elev= 11
     -16    45.6      -6    45.6      -3    44.2       0    42.8       0    40.8
    10.5    40.8    10.5    42.8    13.5    43.6    19.5    43.6    21.7    45.2
    31.7    45.2
#Mann= 3 , 0 , 0
     -16    .035       0       0    .035       0    13.5    .035       0
#XS Ineff= 2 , 0
               0    42.8    13.5            43.6
Permanent Ineff=
       F       F
Bank Sta=0,13.5
XS Rating Curve= 0
Exp/Cntr=.3,.1

Type RM Length L Ch R = 1 ,18      ,50,50,50
#Sta/Elev= 14
   -14.4    43.8    -4.4    43.8    -2.2    42.3       0    42.3      .5    40.8
     3.7    40.8     4.1    41.3     7.1    42.6    11.3    42.6    11.9      43
    13.3      43    16.3    44.5    19.3      46    29.3      46
#Mann= 3 , 0 , 0
   -14.4    .035       0       0    .035       0     7.1    .035       0
#XS Ineff= 2 , 0
               0    42.3     7.1            42.6
Permanent Ineff=
       F       F
Bank Sta=0,7.1
XS Rating Curve= 0
Exp/Cntr=.3,.1

Type RM Length L Ch R = 1 ,17      ,50,50,50
#Sta/Elev= 14
   -14.6   42.41    -4.6   42.41    -2.2   40.71       0   40.71      .5   39.31
     3.7   39.31     4.1   39.81     7.1   41.11    11.6   41.11    12.2   41.51
    13.6   41.51    16.6   43.01    19.6   44.51    29.6   44.51
#Mann= 3 , 0 , 0
   -14.6    .035       0       0    .035       0     7.1    .035       0
#XS Ineff= 2 , 0
               0   40.71     7.1           41.11
Permanent Ineff=
       F       F
Bank Sta=0,7.1
XS Rating Curve= 0
Exp/Cntr=.3,.1

Type RM Length L Ch R = 1 ,16      ,50,50,50
#Sta/Elev= 8
     -10   39.13       0   39.13       3   37.83       6   37.83     7.6   39.23
     8.2   39.23     8.9   38.53    18.9   38.53
#Mann= 3 , 0 , 0
     -10    .035       0       0    .035       0     7.6    .035       0
Levee=-1,0,45,-1,7.6,45,,
#XS Ineff= 2 , 0
               0   39.13     7.6           39.23
Permanent Ineff=
       F       F
Bank Sta=0,7.6
XS Rating Curve= 0
Exp/Cntr=.3,.1

Type RM Length L Ch R = 1 ,15      ,50,50,50
#Sta/Elev= 9
   -13.8   37.64    -3.8   37.64      -3   38.14       0   38.14     2.2   36.84
     4.8   36.84     7.3   38.54    10.3   39.74    13.3   40.94
#Mann= 3 , 0 , 0
   -13.8    .035       0       0    .035       0     7.3    .035       0
Levee=-1,0,45,-1,7.3,38.54,,
#XS Ineff= 2 , 0
               0   38.14     7.3           38.54
Permanent Ineff=
       F       F
Bank Sta=0,7.3
XS Rating Curve= 0
Exp/Cntr=.3,.1

Type RM Length L Ch R = 1 ,14      ,16,16,16
#Sta/Elev= 9
   -14.5   35.71    -4.5   35.71    -3.5   36.51       0   36.51     2.3   35.31
     5.1   35.31     7.7   37.01    10.7   38.21    13.7   39.41
#Mann= 3 , 0 , 0
   -14.5    .035       0       0    .035       0     7.7    .035       0
Levee=-1,0,45,-1,7.7,37.01,,
#XS Ineff= 2 , 0
               0   36.51     7.7           37.01
Permanent Ineff=
       F       F
Bank Sta=0,7.7
XS Rating Curve= 0
Exp/Cntr=.3,.1

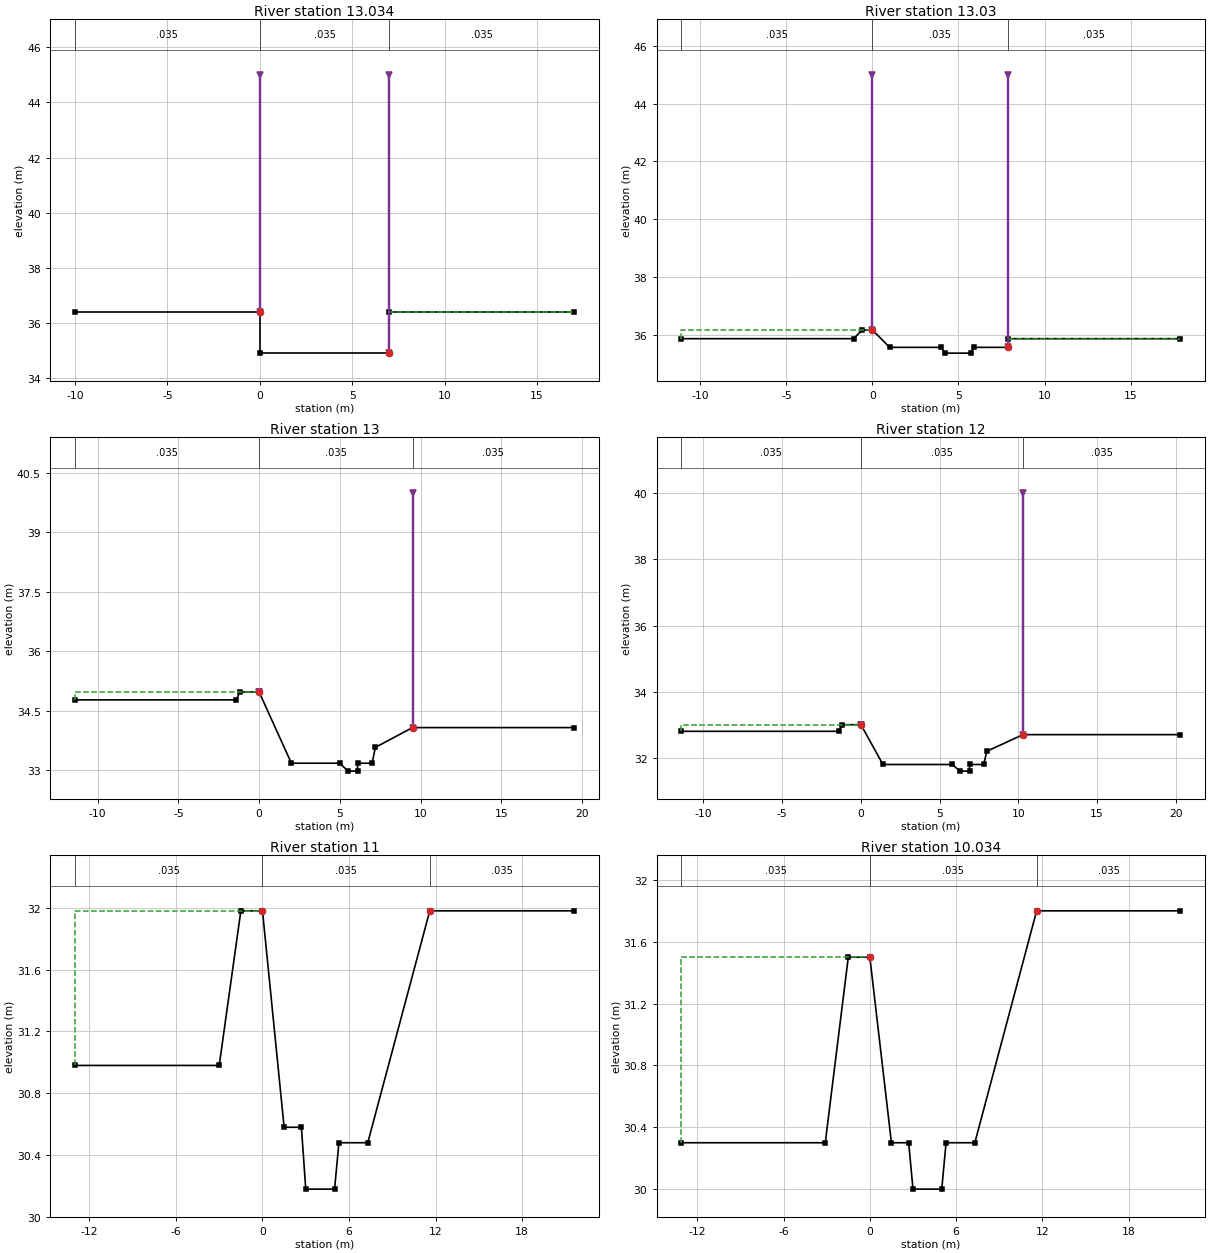
Type RM Length L Ch R = 1 ,13.034  ,4,4,4
#Sta/Elev= 6
     -10   36.41       0   36.41       0   34.91       7   34.91       7   36.41
      17   36.41
#Mann= 3 , 0 , 0
     -10    .035       0       0    .035       0       7    .035       0
Levee=-1,0,45,-1,7,45,,
#XS Ineff= 2 , 0
               0   36.41       7           36.41
Permanent Ineff=
       F       F
Bank Sta=0,7
XS Rating Curve= 0
Exp/Cntr=.3,.1

Type RM Length L Ch R = 1 ,13.03   ,30,30,30
#Sta/Elev= 12
   -11.1   35.86    -1.1   35.86     -.6   36.16       0   36.16       1   35.56
       4   35.56     4.2   35.36     5.7   35.36     5.9   35.56     7.9   35.56
     7.9   35.86    17.9   35.86
#Mann= 3 , 0 , 0
   -11.1    .035       0       0    .035       0     7.9    .035       0
Levee=-1,0,45,-1,7.9,45,,
#XS Ineff= 2 , 0
               0   36.16     7.9           35.86
Permanent Ineff=
       F       F
Bank Sta=0,7.9
XS Rating Curve= 0
Exp/Cntr=.3,.1

Type RM Length L Ch R = 1 ,13      ,50,50,50
#Sta/Elev= 13
   -11.4   34.77    -1.4   34.77    -1.2   34.97       0   34.97       2   33.17
       5   33.17     5.5   32.97     6.1   32.97     6.1   33.17       7   33.17
     7.2   33.57     9.5   34.07    19.5   34.07
#Mann= 3 , 0 , 0
   -11.4    .035       0       0    .035       0     9.5    .035       0
Levee=-1,0,34.97,-1,9.5,40,,
#XS Ineff= 2 , 0
               0   34.97     9.5           34.07
Permanent Ineff=
       F       F
Bank Sta=0,9.5
XS Rating Curve= 0
Exp/Cntr=.3,.1

Type RM Length L Ch R = 1 ,12      ,50,50,50
#Sta/Elev= 13
   -11.4   32.81    -1.4   32.81    -1.2   33.01       0   33.01     1.4   31.81
     5.8   31.81     6.3   31.61     6.9   31.61     6.9   31.81     7.8   31.81
       8   32.21    10.3   32.71    20.3   32.71
#Mann= 3 , 0 , 0
   -11.4    .035       0       0    .035       0    10.3    .035       0
Levee=-1,0,33.01,-1,10.3,40,,
#XS Ineff= 2 , 0
               0   33.01    10.3           32.71
Permanent Ineff=
       F       F
Bank Sta=0,10.3
XS Rating Curve= 0
Exp/Cntr=.3,.1

Type RM Length L Ch R = 1 ,11      ,16,16,16
#Sta/Elev= 12
     -13   30.98      -3   30.98    -1.5   31.98       0   31.98     1.5   30.58
     2.7   30.58       3   30.18       5   30.18     5.3   30.48     7.3   30.48
    11.6   31.98    21.6   31.98
#Mann= 3 , 0 , 0
     -13    .035       0       0    .035       0    11.6    .035       0
#XS Ineff= 2 , 0
               0   31.98    11.6           31.98
Permanent Ineff=
       F       F
Bank Sta=0,11.6
XS Rating Curve= 0
Exp/Cntr=.3,.1

Type RM Length L Ch R = 1 ,10.034  ,34,34,34
#Sta/Elev= 12
   -13.1    30.3    -3.1    30.3    -1.5    31.5       0    31.5     1.5    30.3
     2.7    30.3       3      30       5      30     5.3    30.3     7.3    30.3
    11.6    31.8    21.6    31.8
#Mann= 3 , 0 , 0
   -13.1    .035       0       0    .035       0    11.6    .035       0
#XS Ineff= 2 , 0
               0    31.5    11.6            31.8
Permanent Ineff=
       F       F
Bank Sta=0,11.6
XS Rating Curve= 0
Exp/Cntr=.3,.1

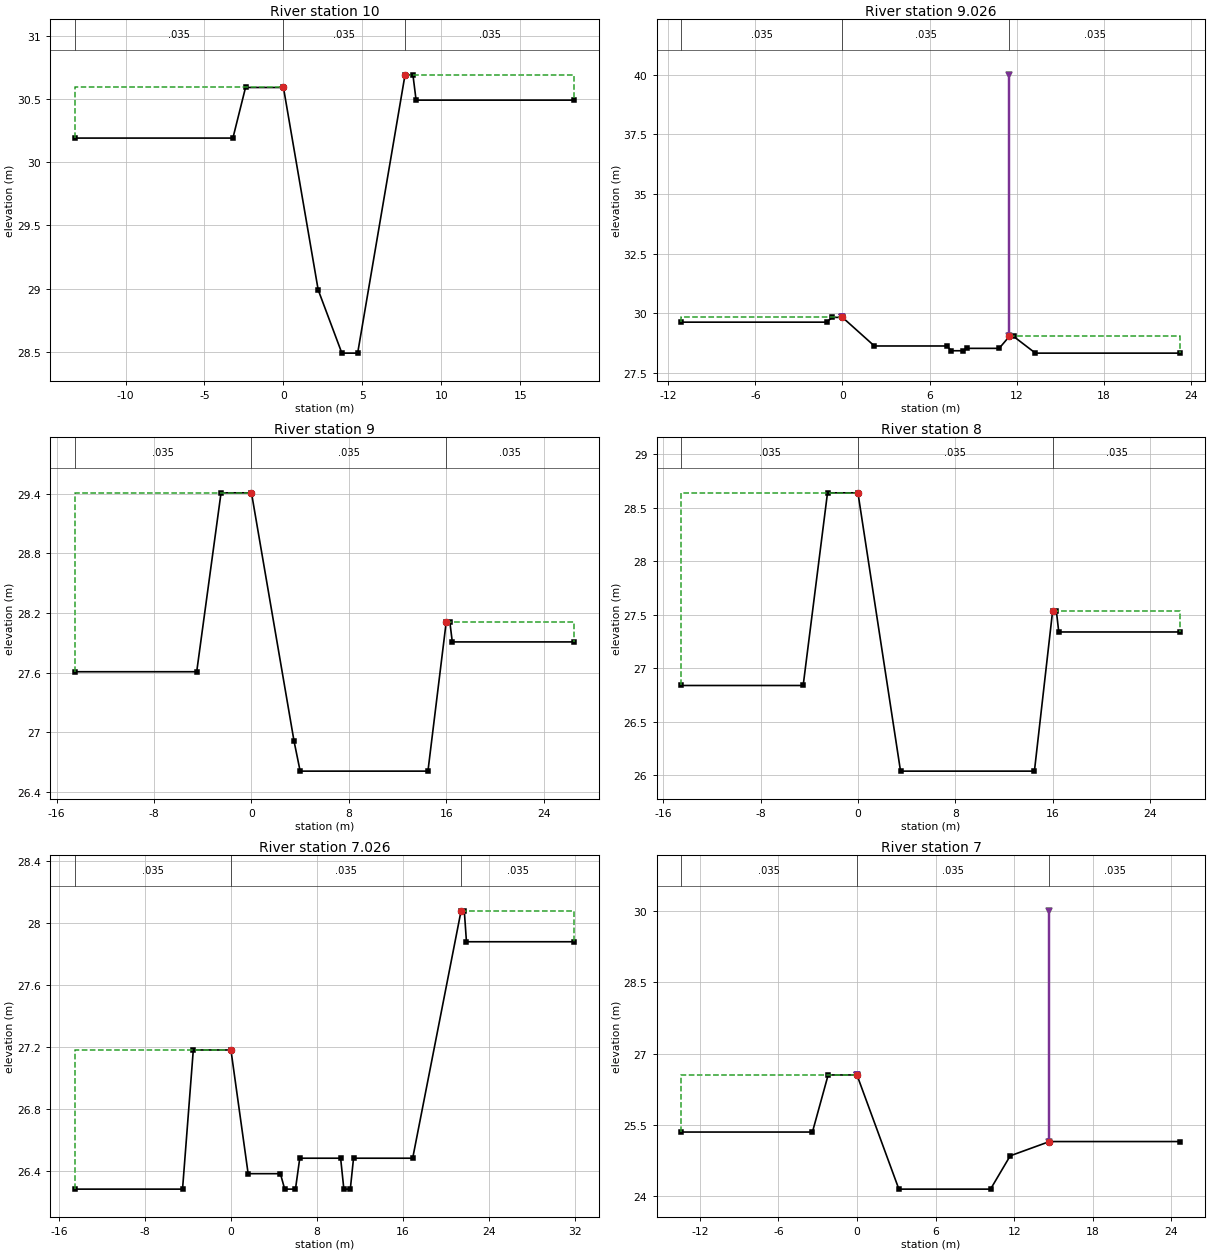
Type RM Length L Ch R = 1 ,10      ,24,24,24
#Sta/Elev= 11
   -13.2   30.19    -3.2   30.19    -2.4   30.59       0   30.59     2.2   28.99
     3.7   28.49     4.7   28.49     7.7   30.69     8.2   30.69     8.4   30.49
    18.4   30.49
#Mann= 3 , 0 , 0
   -13.2    .035       0       0    .035       0     7.7    .035       0
#XS Ineff= 2 , 0
               0   30.59     7.7           30.69
Permanent Ineff=
       F       F
Bank Sta=0,7.7
XS Rating Curve= 0
Exp/Cntr=.3,.1

Type RM Length L Ch R = 1 ,9.026   ,26,26,26
#Sta/Elev= 14
   -11.1   29.62    -1.1   29.62     -.7   29.82       0   29.82     2.2   28.62
     7.2   28.62     7.5   28.42     8.3   28.42     8.6   28.52    10.8   28.52
    11.5   29.02    11.8   29.02    13.3   28.32    23.3   28.32
#Mann= 3 , 0 , 0
   -11.1    .035       0       0    .035       0    11.5    .035       0
Levee=-1,0,29.82,-1,11.5,40,,
#XS Ineff= 2 , 0
               0   29.82    11.5           29.02
Permanent Ineff=
       F       F
Bank Sta=0,11.5
XS Rating Curve= 0
Exp/Cntr=.3,.1

Type RM Length L Ch R = 1 ,9       ,50,50,50
#Sta/Elev= 11
   -14.5   27.61    -4.5   27.61    -2.5   29.41       0   29.41     3.5   26.91
       4   26.61    14.5   26.61      16   28.11    16.3   28.11    16.5   27.91
    26.5   27.91
#Mann= 3 , 0 , 0
   -14.5    .035       0       0    .035       0      16    .035       0
#XS Ineff= 2 , 0
               0   29.41      16           28.11
Permanent Ineff=
       F       F
Bank Sta=0,16
XS Rating Curve= 0
Exp/Cntr=.3,.1

Type RM Length L Ch R = 1 ,8       ,24,24,24
#Sta/Elev= 10
   -14.5   26.84    -4.5   26.84    -2.5   28.64       0   28.64     3.5   26.04
    14.5   26.04      16   27.54    16.3   27.54    16.5   27.34    26.5   27.34
#Mann= 3 , 0 , 0
   -14.5    .035       0       0    .035       0      16    .035       0
#XS Ineff= 2 , 0
               0   28.64      16           27.54
Permanent Ineff=
       F       F
Bank Sta=0,16
XS Rating Curve= 0
Exp/Cntr=.3,.1

Type RM Length L Ch R = 1 ,7.026   ,26,26,26
#Sta/Elev= 18
   -14.5   26.28    -4.5   26.28    -3.5   27.18       0   27.18     1.6   26.38
     4.6   26.38       5   26.28       6   26.28     6.4   26.48    10.2   26.48
    10.5   26.28    11.1   26.28    11.4   26.48    16.9   26.48    21.4   28.08
    21.7   28.08    21.9   27.88    31.9   27.88
#Mann= 3 , 0 , 0
   -14.5    .035       0       0    .035       0    21.4    .035       0
#XS Ineff= 2 , 0
               0   27.18    21.4           28.08
Permanent Ineff=
       F       F
Bank Sta=0,21.4
XS Rating Curve= 0
Exp/Cntr=.3,.1

Type RM Length L Ch R = 1 ,7       ,50,50,50
#Sta/Elev= 9
   -13.4   25.35    -3.4   25.35    -2.2   26.55       0   26.55     3.2   24.15
    10.2   24.15    11.7   24.85    14.7   25.15    24.7   25.15
#Mann= 3 , 0 , 0
   -13.4    .035       0       0    .035       0    14.7    .035       0
Levee=-1,0,26.55,-1,14.7,30,,
#XS Ineff= 2 , 0
               0   26.55    14.7           25.15
Permanent Ineff=
       F       F
Bank Sta=0,14.7
XS Rating Curve= 0
Exp/Cntr=.3,.1

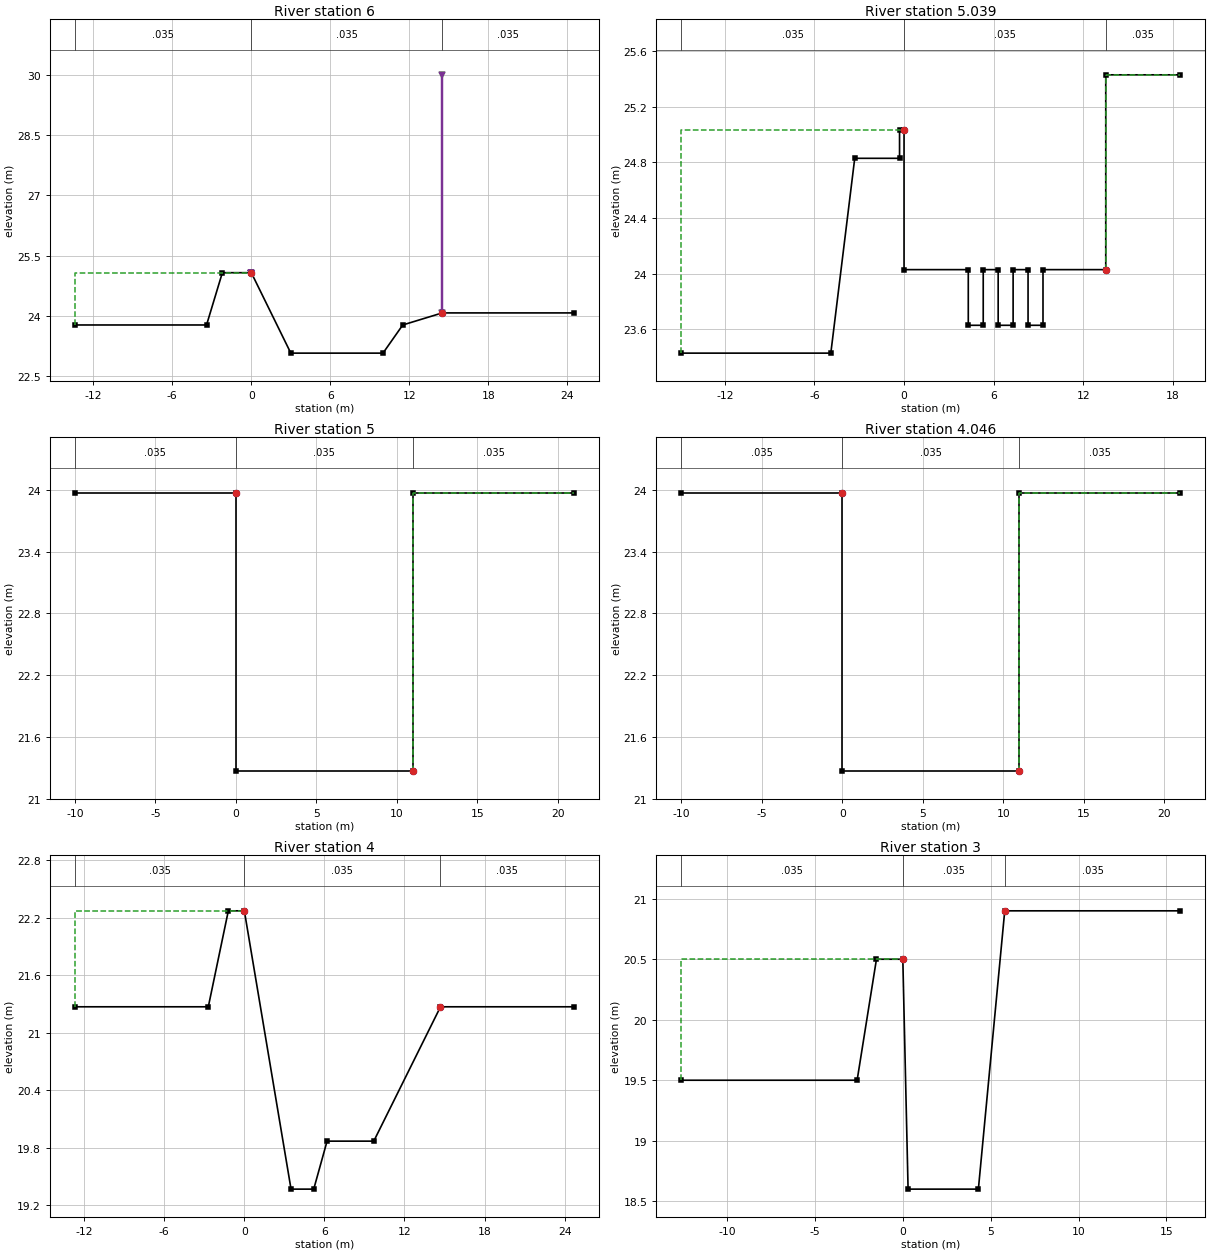
Type RM Length L Ch R = 1 ,6       ,50,50,50
#Sta/Elev= 9
   -13.4   23.78    -3.4   23.78    -2.2   25.08       0   25.08       3   23.08
      10   23.08    11.5   23.78    14.5   24.08    24.5   24.08
#Mann= 3 , 0 , 0
   -13.4    .035       0       0    .035       0    14.5    .035       0
Levee=-1,0,25.08,-1,14.5,30,,
#XS Ineff= 2 , 0
               0   25.08    14.5           24.08
Permanent Ineff=
       F       F
Bank Sta=0,14.5
XS Rating Curve= 0
Exp/Cntr=.3,.1

Type RM Length L Ch R = 1 ,5.039   ,39,39,39
#Sta/Elev= 22
   -14.9   23.43    -4.9   23.43    -3.3   24.83     -.3   24.83     -.3   25.03
       0   25.03       0   24.03     4.3   24.03     4.3   23.63     5.3   23.63
     5.3   24.03     6.3   24.03     6.3   23.63     7.3   23.63     7.3   24.03
     8.3   24.03     8.3   23.63     9.3   23.63     9.3   24.03    13.5   24.03
    13.5   25.43    18.5   25.43
#Mann= 3 , 0 , 0
   -14.9    .035       0       0    .035       0    13.5    .035       0
#XS Ineff= 2 , 0
               0   25.03    13.5           25.43
Permanent Ineff=
       F       F
Bank Sta=0,13.5
XS Rating Curve= 0
Exp/Cntr=.3,.1

Type RM Length L Ch R = 1 ,5       ,4,4,4
#Sta/Elev= 6
     -10   23.97       0   23.97       0   21.27      11   21.27      11   23.97
      21   23.97
#Mann= 3 , 0 , 0
     -10    .035       0       0    .035       0      11    .035       0
#XS Ineff= 2 , 0
               0   23.97      11           23.97
Permanent Ineff=
       F       F
Bank Sta=0,11
XS Rating Curve= 0
Exp/Cntr=.3,.1

Type RM Length L Ch R = 1 ,4.046   ,46,46,46
#Sta/Elev= 6
     -10   23.97       0   23.97       0   21.27      11   21.27      11   23.97
      21   23.97
#Mann= 3 , 0 , 0
     -10    .035       0       0    .035       0      11    .035       0
#XS Ineff= 2 , 0
               0   23.97      11           23.97
Permanent Ineff=
       F       F
Bank Sta=0,11
XS Rating Curve= 0
Exp/Cntr=.3,.1

Type RM Length L Ch R = 1 ,4       ,50,50,50
#Sta/Elev= 10
   -12.7   21.27    -2.7   21.27    -1.2   22.27       0   22.27     3.5   19.37
     5.2   19.37     6.2   19.87     9.7   19.87    14.7   21.27    24.7   21.27
#Mann= 3 , 0 , 0
   -12.7    .035       0       0    .035       0    14.7    .035       0
#XS Ineff= 2 , 0
               0   22.27    14.7           21.27
Permanent Ineff=
       F       F
Bank Sta=0,14.7
XS Rating Curve= 0
Exp/Cntr=.3,.1

Type RM Length L Ch R = 1 ,3       ,50,50,50
#Sta/Elev= 8
   -12.6    19.5    -2.6    19.5    -1.5    20.5       0    20.5      .3    18.6
     4.3    18.6     5.8    20.9    15.8    20.9
#Mann= 3 , 0 , 0
   -12.6    .035       0       0    .035       0     5.8    .035       0
#XS Ineff= 2 , 0
               0    20.5     5.8            20.9
Permanent Ineff=
       F       F
Bank Sta=0,5.8
XS Rating Curve= 0
Exp/Cntr=.3,.1

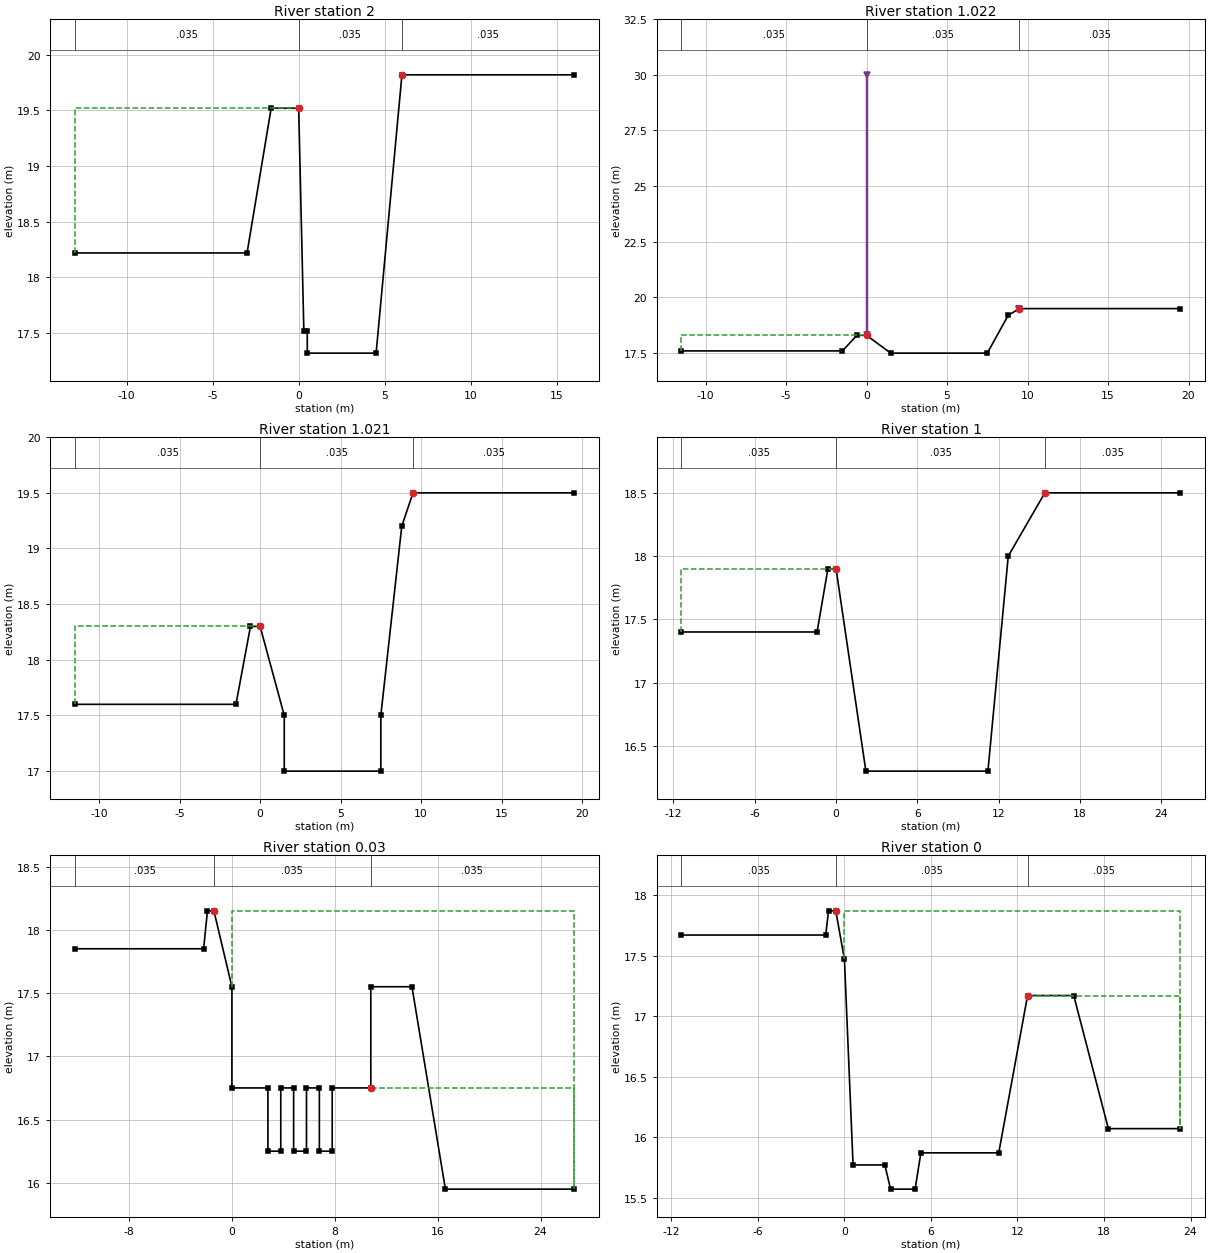
Type RM Length L Ch R = 1 ,2       ,28,28,28
#Sta/Elev= 10
     -13   18.22      -3   18.22    -1.6   19.52       0   19.52      .3   17.52
      .5   17.52      .5   17.32     4.5   17.32       6   19.82      16   19.82
#Mann= 3 , 0 , 0
     -13    .035       0       0    .035       0       6    .035       0
#XS Ineff= 2 , 0
               0   19.52       6           19.82
Permanent Ineff=
       F       F
Bank Sta=0,6
XS Rating Curve= 0
Exp/Cntr=.3,.1

Type RM Length L Ch R = 1 ,1.022   ,1,1,1
#Sta/Elev= 9
   -11.5    17.6    -1.5    17.6     -.6    18.3       0    18.3     1.5    17.5
     7.5    17.5     8.8    19.2     9.5    19.5    19.5    19.5
#Mann= 3 , 0 , 0
   -11.5    .035       0       0    .035       0     9.5    .035       0
Levee=-1,0,30,-1,9.5,19.5,,
#XS Ineff= 2 , 0
               0    18.3     9.5            19.5
Permanent Ineff=
       F       F
Bank Sta=0,9.5
XS Rating Curve= 0
Exp/Cntr=.3,.1

Type RM Length L Ch R = 1 ,1.021   ,21,21,21
#Sta/Elev= 11
   -11.5    17.6    -1.5    17.6     -.6    18.3       0    18.3     1.5    17.5
     1.5      17     7.5      17     7.5    17.5     8.8    19.2     9.5    19.5
    19.5    19.5
#Mann= 3 , 0 , 0
   -11.5    .035       0       0    .035       0     9.5    .035       0
#XS Ineff= 2 , 0
               0    18.3     9.5            19.5
Permanent Ineff=
       F       F
Bank Sta=0,9.5
XS Rating Curve= 0
Exp/Cntr=.3,.1

Type RM Length L Ch R = 1 ,1       ,20,20,20
#Sta/Elev= 9
   -11.4    17.4    -1.4    17.4     -.6    17.9       0    17.9     2.2    16.3
    11.2    16.3    12.7      18    15.4    18.5    25.4    18.5
#Mann= 3 , 0 , 0
   -11.4    .035       0       0    .035       0    15.4    .035       0
#XS Ineff= 2 , 0
               0    17.9    15.4            18.5
Permanent Ineff=
       F       F
Bank Sta=0,15.4
XS Rating Curve= 0
Exp/Cntr=.3,.1

Type RM Length L Ch R = 1 ,0.03    ,30,30,30
#Sta/Elev= 23
   -12.2   17.85    -2.2   17.85    -1.9   18.15    -1.4   18.15       0   17.55
       0   16.75     2.8   16.75     2.8   16.25     3.8   16.25     3.8   16.75
     4.8   16.75     4.8   16.25     5.8   16.25     5.8   16.75     6.8   16.75
     6.8   16.25     7.8   16.25     7.8   16.75    10.8   16.75    10.8   17.55
      14   17.55    16.6   15.95    26.6   15.95
#Mann= 3 , 0 , 0
   -12.2    .035       0    -1.4    .035       0    10.8    .035       0
#XS Ineff= 2 , 0
       0    -1.4   18.15    10.8       0   16.75
Permanent Ineff=
       F       F
Bank Sta=-1.4,10.8
XS Rating Curve= 0
Exp/Cntr=.3,.1

Type RM Length L Ch R = 1 ,0       ,0,0,0
#Sta/Elev= 15
   -11.3   17.67    -1.3   17.67    -1.1   17.87     -.6   17.87       0   17.47
      .6   15.77     2.8   15.77     3.2   15.57     4.9   15.57     5.3   15.87
    10.7   15.87    12.7   17.17    15.9   17.17    18.3   16.07    23.3   16.07
#Mann= 3 , 0 , 0
   -11.3    .035       0     -.6    .035       0    12.7    .035       0
#XS Ineff= 2 , 0
       0     -.6   17.87    12.7       0   17.17
Permanent Ineff=
       F       F
Bank Sta=-.6,12.7
XS Rating Curve= 0
Exp/Cntr=.3,.1

Chan Stop Cuts=-1