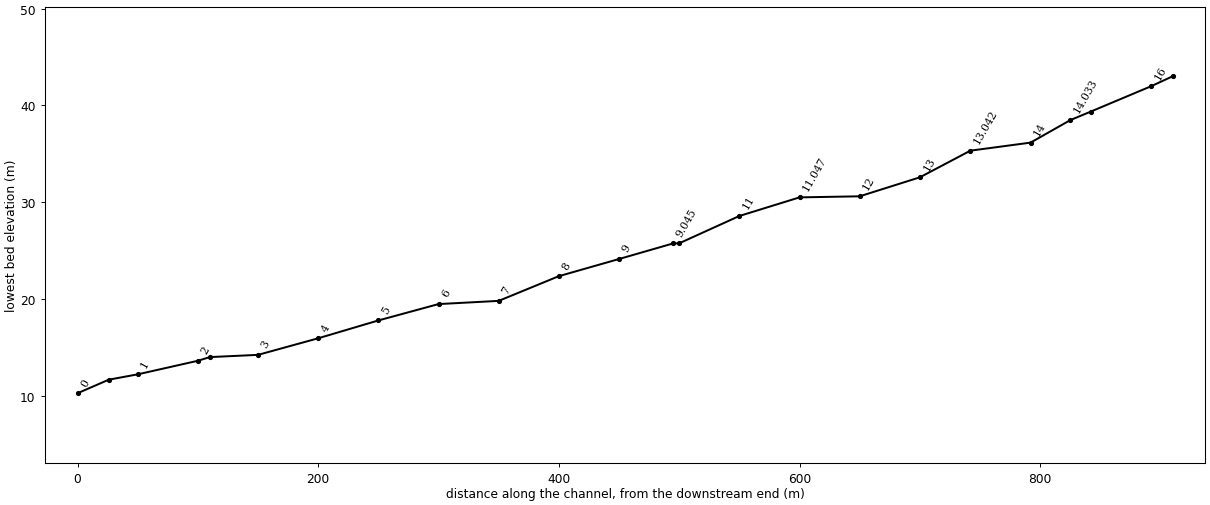
--- ECC.prj (project) ---

Proj Title=eocho-ch
Current Plan=p01
Default Exp/Contr=.3,.1
SI Units
Geom File=g01
Flow File=f01
Plan File=p01
Y Axis Title=Elevation
X Axis Title(PF)=Main Channel Distance
X Axis Title(XS)=Station
BEGIN DESCRIPTION:
           BACK WATER COMPUTATION
      APPLICATION OF HEC-2 BY Samju Construction Engineering
      eocho-ch: 10,20,30,50,80 yr
END DESCRIPTION:
DSS Export Rating Curves= 0
DSS Export Rating Curve Sorted= 0
DSS Export Volume Flow Curves= 0
DXF OffsetX= 0
DXF OffsetY= 0
DXF ScaleX= 1
DXF ScaleY= 10

--- ECC.p01 (plan) ---

Plan Title=Imported Plan 01
Version=Version 3.0.1  Mar 2001
Short Identifier=Imported Pla
Geom File=g01
Flow File=f01
Subcritical Flow
K Sum by GR= 0
Std Step Tol= 0.003
Critical Tol= 0.003
Num of Std Step Trials= 20
Max Error Tol= 0.1
Flow Tol Ratio= 0.001
Split Flow NTrial= 30
Split Flow Tol= 0.02
Split Flow Ratio= 0.02
Log Output Level= 0
Friction Slope Method= 1
Unsteady Friction Slope Method= 2
Parabolic Critical Depth
Global Vel Dist= 0 , 0 , 0
Global Log Level= 0
CheckData=True
Encroach Param=-1 ,0,0, 0
Computation Interval=1HOUR
Output Interval=1HOUR
Run HTab= 0
Run UNet= 0
Run PostProcess= 0
UNET Theta= 1
UNET ZTol= 0.02
UNET ZSATol= 0.1
UNET MxIter= 20
UNET MaxInSteps= 20
UNET DtIC= 0
UNET DtMin= 0
UNET MaxCRTS= 20
UNET WFStab= 2
UNET SFStab= 1
UNET WFX= 1
UNET SFX= 1
UNET Convert EG Bridges=-1
UNET Use Existing IB Tables=-1
Instantaneous Interval=1HOUR
Write IC File= 0
Write Velocity= 0
Write Detailed= 0

--- ECC.f01 (steady flow) ---

Flow Title=Imported Flow 01
Version=Version 3.0.1  Mar 2001
Number of Profiles= 5
Profile Names=10YR,20YR,30YR,50YR,80YR
River Rch & RM=RIVER-1,Reach-1         ,16.018
    7.39    8.14    8.58    9.13    9.64
River Rch & RM=EOCHO,EOCHO           ,16.018
    7.39    8.14    8.58    9.13    9.64
Boundary for River Rch & Prof#=EOCHO,EOCHO           , 1
Up Type= 0
Dn Type= 3
Dn Slope=.041
Boundary for River Rch & Prof#=EOCHO,EOCHO           , 2
Up Type= 0
Dn Type= 3
Dn Slope=.041
Boundary for River Rch & Prof#=EOCHO,EOCHO           , 3
Up Type= 0
Dn Type= 3
Dn Slope=.041
Boundary for River Rch & Prof#=EOCHO,EOCHO           , 4
Up Type= 0
Dn Type= 3
Dn Slope=.041
Boundary for River Rch & Prof#=EOCHO,EOCHO           , 5
Up Type= 0
Dn Type= 3
Dn Slope=.041
DSS Import GetInterval= 0
DSS Import GetPeak= 0
DSS Import FillOption= 0

--- ECC.g01 (geometry) ---

Geom Title=Imported Geom 01
Version=Version 3.0.1  Mar 2001

River Reach=EOCHO           ,EOCHO
Reach XY= 2
              .5             .95              .5             .05

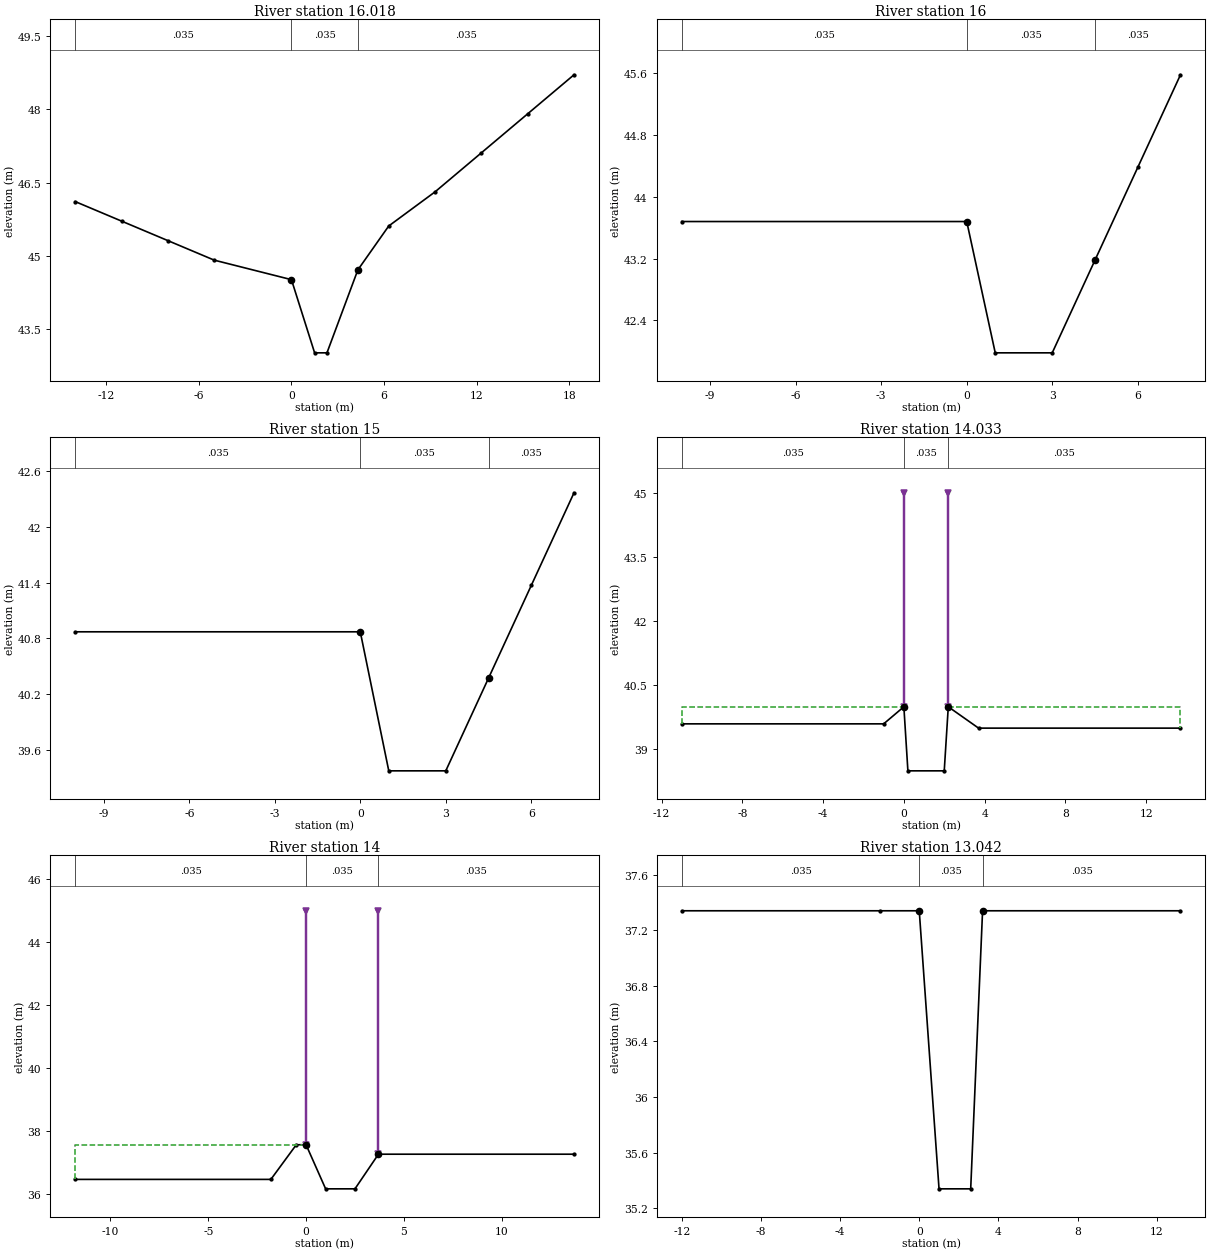
Type RM Length L Ch R = 1 ,16.018  ,18,18,18
#Sta/Elev= 13
     -14   46.11     -11   45.71      -8   45.31      -5   44.91       0   44.51
     1.5   43.01     2.3   43.01     4.3   44.71     6.3   45.61     9.3   46.31
    12.3   47.11    15.3   47.91    18.3   48.71
#Mann= 3 , 0 , 0
     -14    .035       0       0    .035       0     4.3    .035       0
#XS Ineff= 2 , 0
               0   44.51     4.3           44.71
Permanent Ineff=
       F       F
Bank Sta=0,4.3
XS Rating Curve= 0
Exp/Cntr=.3,.1

Type RM Length L Ch R = 1 ,16      ,50,50,50
#Sta/Elev= 7
     -10   43.68       0   43.68       1   41.98       3   41.98     4.5   43.18
       6   44.38     7.5   45.58
#Mann= 3 , 0 , 0
     -10    .035       0       0    .035       0     4.5    .035       0
#XS Ineff= 2 , 0
               0   43.68     4.5           43.18
Permanent Ineff=
       F       F
Bank Sta=0,4.5
XS Rating Curve= 0
Exp/Cntr=.3,.1

Type RM Length L Ch R = 1 ,15      ,17,17,17
#Sta/Elev= 7
     -10   40.87       0   40.87       1   39.37       3   39.37     4.5   40.37
       6   41.37     7.5   42.37
#Mann= 3 , 0 , 0
     -10    .035       0       0    .035       0     4.5    .035       0
#XS Ineff= 2 , 0
               0   40.87     4.5           40.37
Permanent Ineff=
       F       F
Bank Sta=0,4.5
XS Rating Curve= 0
Exp/Cntr=.3,.1

Type RM Length L Ch R = 1 ,14.033  ,33,33,33
#Sta/Elev= 8
     -11   39.59      -1   39.59       0   39.99      .2   38.49       2   38.49
     2.2   39.99     3.7   39.49    13.7   39.49
#Mann= 3 , 0 , 0
     -11    .035       0       0    .035       0     2.2    .035       0
Levee=-1,0,45,-1,2.2,45,,
#XS Ineff= 2 , 0
               0   39.99     2.2           39.99
Permanent Ineff=
       F       F
Bank Sta=0,2.2
XS Rating Curve= 0
Exp/Cntr=.3,.1

Type RM Length L Ch R = 1 ,14      ,50,50,50
#Sta/Elev= 8
   -11.8   36.47    -1.8   36.47     -.5   37.57       0   37.57       1   36.17
     2.5   36.17     3.7   37.27    13.7   37.27
#Mann= 3 , 0 , 0
   -11.8    .035       0       0    .035       0     3.7    .035       0
Levee=-1,0,45,-1,3.7,45,,
#XS Ineff= 2 , 0
               0   37.57     3.7           37.27
Permanent Ineff=
       F       F
Bank Sta=0,3.7
XS Rating Curve= 0
Exp/Cntr=.3,.1

Type RM Length L Ch R = 1 ,13.042  ,42,42,42
#Sta/Elev= 7
     -12   37.34      -2   37.34       0   37.34       1   35.34     2.6   35.34
     3.2   37.34    13.2   37.34
#Mann= 3 , 0 , 0
     -12    .035       0       0    .035       0     3.2    .035       0
#XS Ineff= 2 , 0
               0   37.34     3.2           37.34
Permanent Ineff=
       F       F
Bank Sta=0,3.2
XS Rating Curve= 0
Exp/Cntr=.3,.1

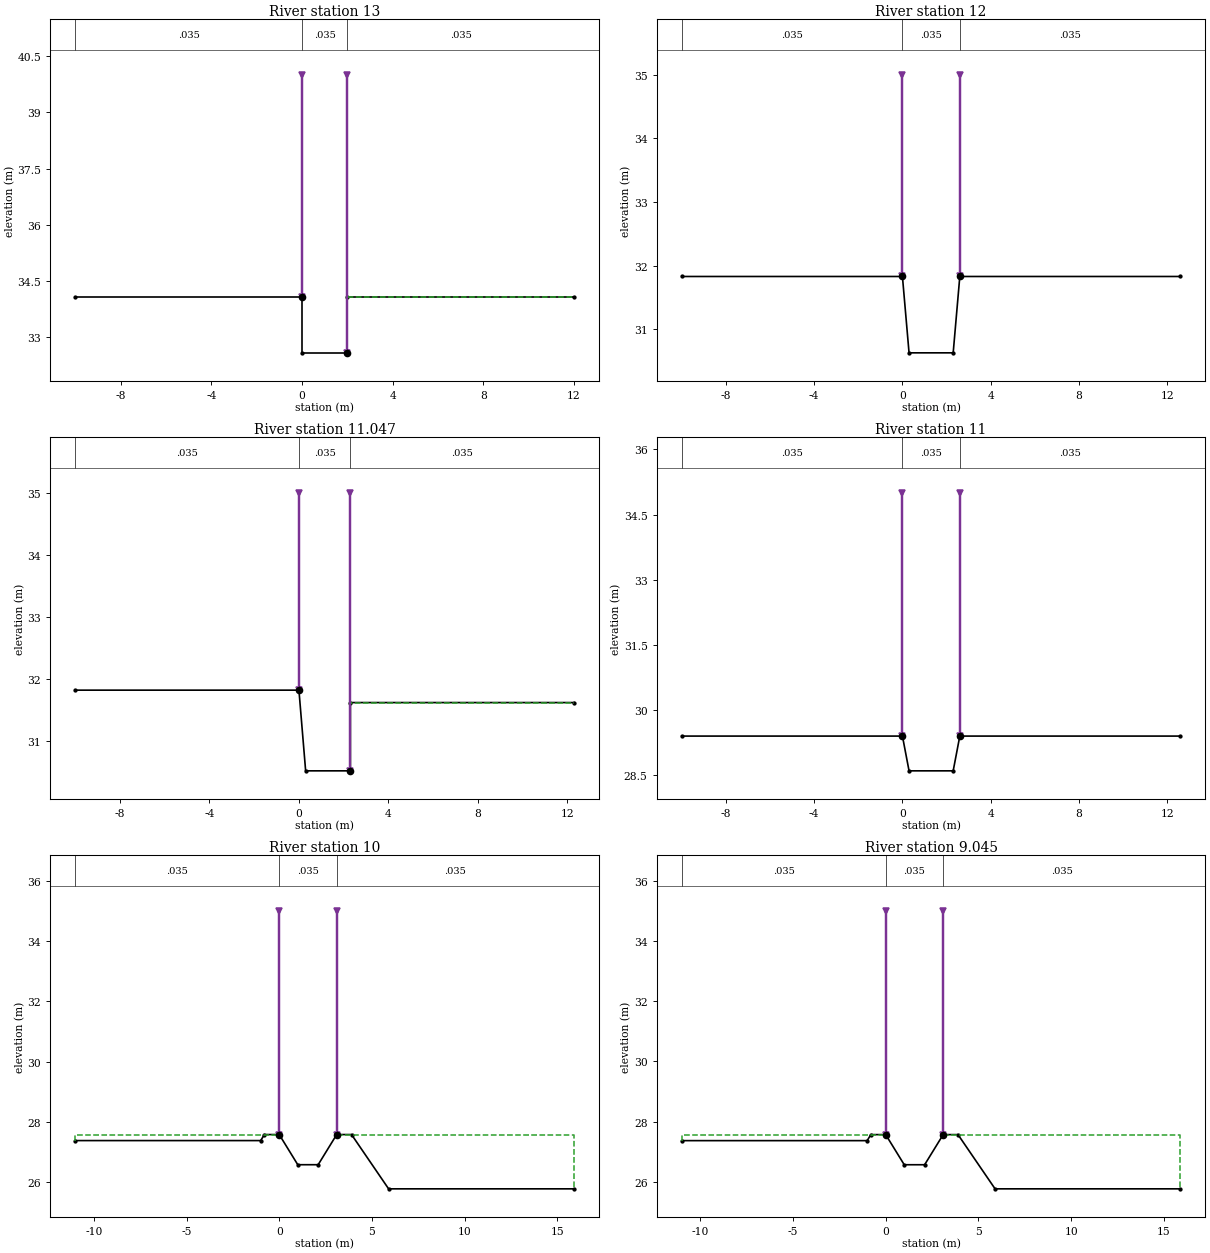
Type RM Length L Ch R = 1 ,13      ,50,50,50
#Sta/Elev= 6
     -10   34.09       0   34.09       0   32.59       2   32.59       2   34.09
      12   34.09
#Mann= 3 , 0 , 0
     -10    .035       0       0    .035       0       2    .035       0
Levee=-1,0,40,-1,2,40,,
#XS Ineff= 2 , 0
               0   34.09       2           34.09
Permanent Ineff=
       F       F
Bank Sta=0,2
XS Rating Curve= 0
Exp/Cntr=.3,.1

Type RM Length L Ch R = 1 ,12      ,50,50,50
#Sta/Elev= 6
     -10   31.83       0   31.83      .3   30.63     2.3   30.63     2.6   31.83
    12.6   31.83
#Mann= 3 , 0 , 0
     -10    .035       0       0    .035       0     2.6    .035       0
Levee=-1,0,35,-1,2.6,35,,
#XS Ineff= 2 , 0
               0   31.83     2.6           31.83
Permanent Ineff=
       F       F
Bank Sta=0,2.6
XS Rating Curve= 0
Exp/Cntr=.3,.1

Type RM Length L Ch R = 1 ,11.047  ,50,50,50
#Sta/Elev= 6
     -10   31.82       0   31.82      .3   30.52     2.3   30.52     2.3   31.62
    12.3   31.62
#Mann= 3 , 0 , 0
     -10    .035       0       0    .035       0     2.3    .035       0
Levee=-1,0,35,-1,2.3,35,,
#XS Ineff= 2 , 0
               0   31.82     2.3           31.62
Permanent Ineff=
       F       F
Bank Sta=0,2.3
XS Rating Curve= 0
Exp/Cntr=.3,.1

Type RM Length L Ch R = 1 ,11      ,50,50,50
#Sta/Elev= 6
     -10    29.4       0    29.4      .3    28.6     2.3    28.6     2.6    29.4
    12.6    29.4
#Mann= 3 , 0 , 0
     -10    .035       0       0    .035       0     2.6    .035       0
Levee=-1,0,35,-1,2.6,35,,
#XS Ineff= 2 , 0
               0    29.4     2.6            29.4
Permanent Ineff=
       F       F
Bank Sta=0,2.6
XS Rating Curve= 0
Exp/Cntr=.3,.1

Type RM Length L Ch R = 1 ,10      ,5,5,5
#Sta/Elev= 10
     -11   27.38      -1   27.38     -.8   27.58       0   27.58       1   26.58
     2.1   26.58     3.1   27.58     3.9   27.58     5.9   25.78    15.9   25.78
#Mann= 3 , 0 , 0
     -11    .035       0       0    .035       0     3.1    .035       0
Levee=-1,0,35,-1,3.1,35,,
#XS Ineff= 2 , 0
               0   27.58     3.1           27.58
Permanent Ineff=
       F       F
Bank Sta=0,3.1
XS Rating Curve= 0
Exp/Cntr=.3,.1

Type RM Length L Ch R = 1 ,9.045   ,45,45,45
#Sta/Elev= 10
     -11   27.37      -1   27.37     -.8   27.57       0   27.57       1   26.57
     2.1   26.57     3.1   27.57     3.9   27.57     5.9   25.77    15.9   25.77
#Mann= 3 , 0 , 0
     -11    .035       0       0    .035       0     3.1    .035       0
Levee=-1,0,35,-1,3.1,35,,
#XS Ineff= 2 , 0
               0   27.57     3.1           27.57
Permanent Ineff=
       F       F
Bank Sta=0,3.1
XS Rating Curve= 0
Exp/Cntr=.3,.1

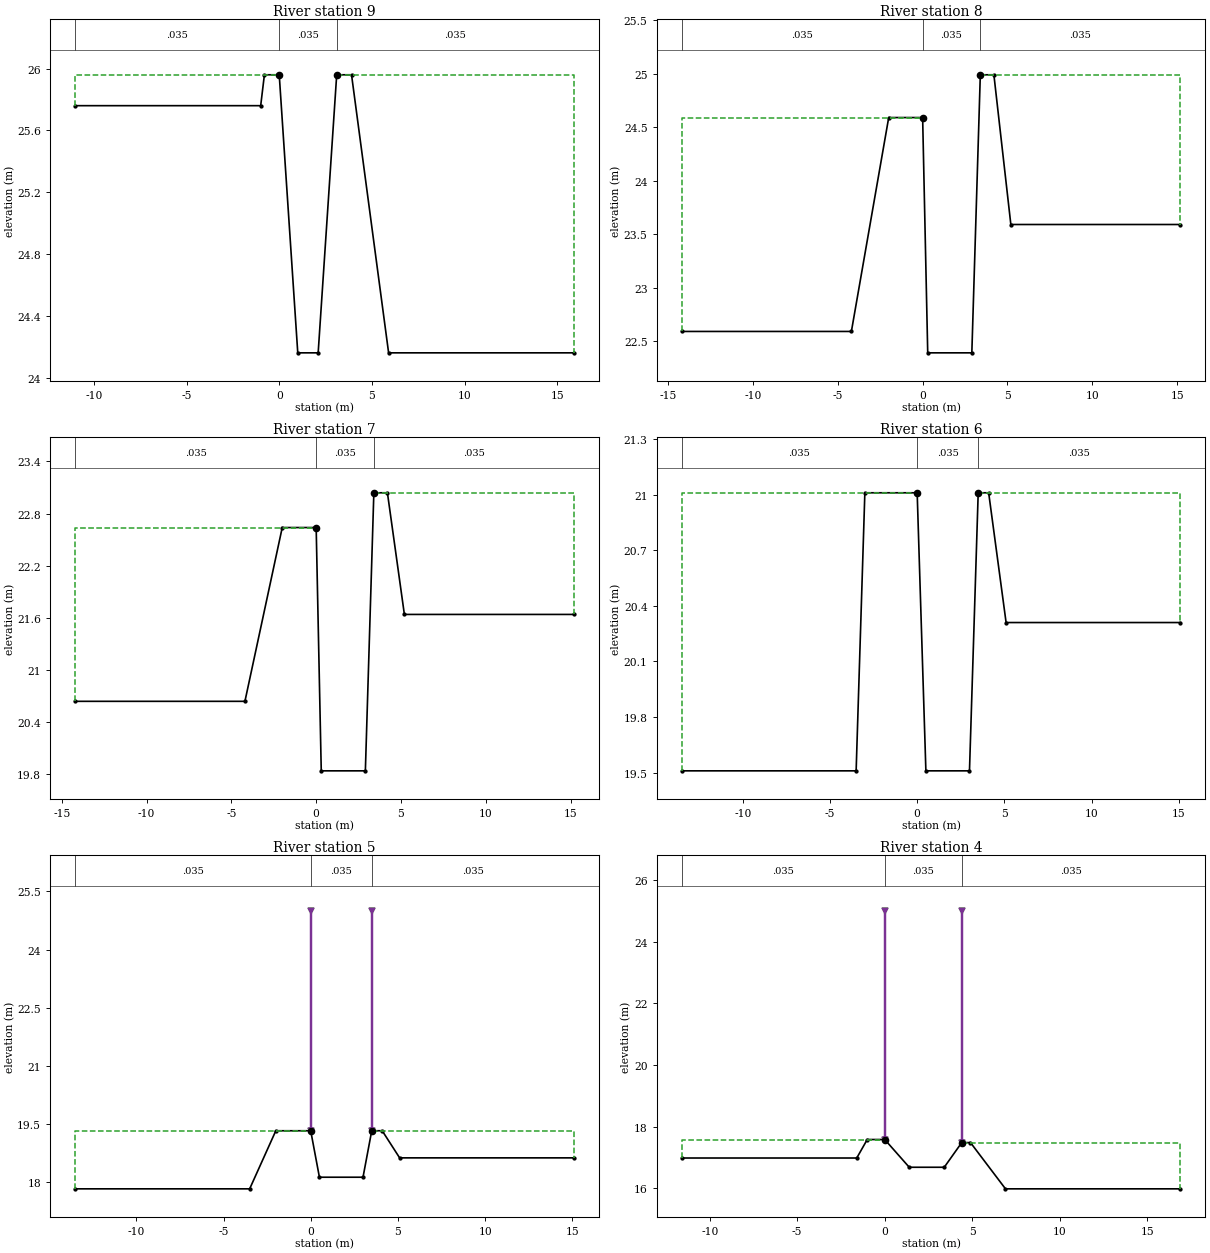
Type RM Length L Ch R = 1 ,9       ,50,50,50
#Sta/Elev= 10
     -11   25.76      -1   25.76     -.8   25.96       0   25.96       1   24.16
     2.1   24.16     3.1   25.96     3.9   25.96     5.9   24.16    15.9   24.16
#Mann= 3 , 0 , 0
     -11    .035       0       0    .035       0     3.1    .035       0
#XS Ineff= 2 , 0
               0   25.96     3.1           25.96
Permanent Ineff=
       F       F
Bank Sta=0,3.1
XS Rating Curve= 0
Exp/Cntr=.3,.1

Type RM Length L Ch R = 1 ,8       ,50,50,50
#Sta/Elev= 10
   -14.2   22.59    -4.2   22.59      -2   24.59       0   24.59      .3   22.39
     2.9   22.39     3.4   24.99     4.2   24.99     5.2   23.59    15.2   23.59
#Mann= 3 , 0 , 0
   -14.2    .035       0       0    .035       0     3.4    .035       0
#XS Ineff= 2 , 0
               0   24.59     3.4           24.99
Permanent Ineff=
       F       F
Bank Sta=0,3.4
XS Rating Curve= 0
Exp/Cntr=.3,.1

Type RM Length L Ch R = 1 ,7       ,50,50,50
#Sta/Elev= 10
   -14.2   20.64    -4.2   20.64      -2   22.64       0   22.64      .3   19.84
     2.9   19.84     3.4   23.04     4.2   23.04     5.2   21.64    15.2   21.64
#Mann= 3 , 0 , 0
   -14.2    .035       0       0    .035       0     3.4    .035       0
#XS Ineff= 2 , 0
               0   22.64     3.4           23.04
Permanent Ineff=
       F       F
Bank Sta=0,3.4
XS Rating Curve= 0
Exp/Cntr=.3,.1

Type RM Length L Ch R = 1 ,6       ,50,50,50
#Sta/Elev= 10
   -13.5   19.51    -3.5   19.51      -3   21.01       0   21.01      .5   19.51
       3   19.51     3.5   21.01     4.1   21.01     5.1   20.31    15.1   20.31
#Mann= 3 , 0 , 0
   -13.5    .035       0       0    .035       0     3.5    .035       0
#XS Ineff= 2 , 0
               0   21.01     3.5           21.01
Permanent Ineff=
       F       F
Bank Sta=0,3.5
XS Rating Curve= 0
Exp/Cntr=.3,.1

Type RM Length L Ch R = 1 ,5       ,50,50,50
#Sta/Elev= 10
   -13.5   17.82    -3.5   17.82      -2   19.32       0   19.32      .5   18.12
       3   18.12     3.5   19.32     4.1   19.32     5.1   18.62    15.1   18.62
#Mann= 3 , 0 , 0
   -13.5    .035       0       0    .035       0     3.5    .035       0
Levee=-1,0,25,-1,3.5,25,,
#XS Ineff= 2 , 0
               0   19.32     3.5           19.32
Permanent Ineff=
       F       F
Bank Sta=0,3.5
XS Rating Curve= 0
Exp/Cntr=.3,.1

Type RM Length L Ch R = 1 ,4       ,50,50,50
#Sta/Elev= 10
   -11.6   16.98    -1.6   16.98      -1   17.58       0   17.58     1.4   16.68
     3.4   16.68     4.4   17.48     4.9   17.48     6.9   15.98    16.9   15.98
#Mann= 3 , 0 , 0
   -11.6    .035       0       0    .035       0     4.4    .035       0
Levee=-1,0,25,-1,4.4,25,,
#XS Ineff= 2 , 0
               0   17.58     4.4           17.48
Permanent Ineff=
       F       F
Bank Sta=0,4.4
XS Rating Curve= 0
Exp/Cntr=.3,.1

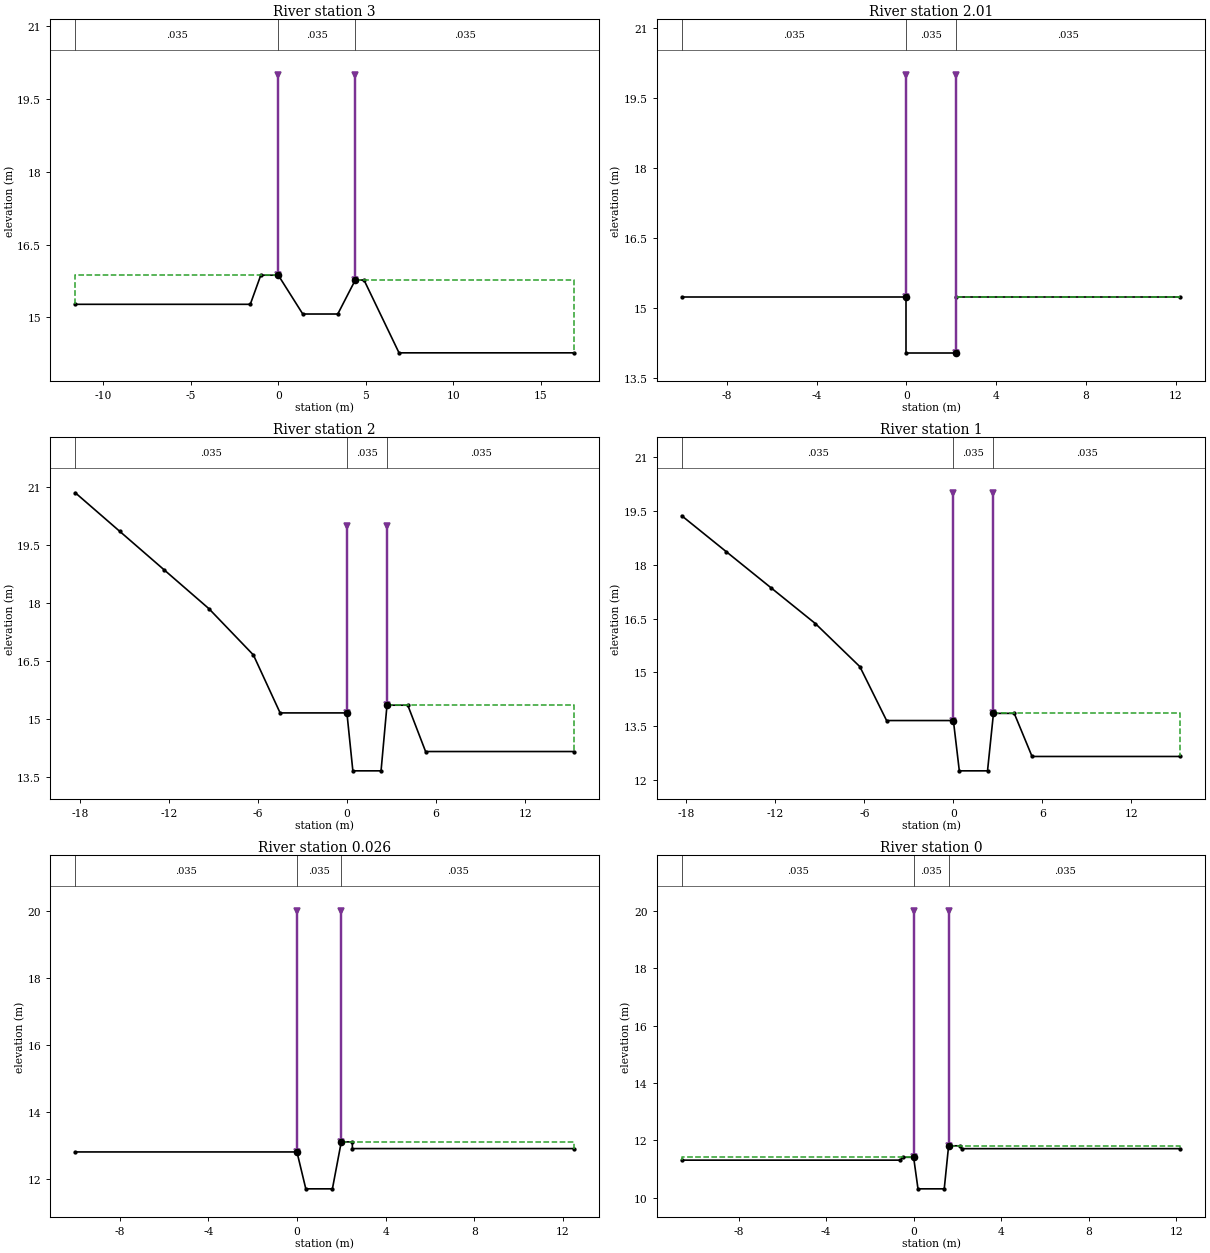
Type RM Length L Ch R = 1 ,3       ,40,40,40
#Sta/Elev= 10
   -11.6   15.27    -1.6   15.27      -1   15.87       0   15.87     1.4   15.07
     3.4   15.07     4.4   15.77     4.9   15.77     6.9   14.27    16.9   14.27
#Mann= 3 , 0 , 0
   -11.6    .035       0       0    .035       0     4.4    .035       0
Levee=-1,0,20,-1,4.4,20,,
#XS Ineff= 2 , 0
               0   15.87     4.4           15.77
Permanent Ineff=
       F       F
Bank Sta=0,4.4
XS Rating Curve= 0
Exp/Cntr=.3,.1

Type RM Length L Ch R = 1 ,2.01    ,10,10,10
#Sta/Elev= 6
     -10   15.24       0   15.24       0   14.04     2.2   14.04     2.2   15.24
    12.2   15.24
#Mann= 3 , 0 , 0
     -10    .035       0       0    .035       0     2.2    .035       0
Levee=-1,0,20,-1,2.2,20,,
#XS Ineff= 2 , 0
               0   15.24     2.2           15.24
Permanent Ineff=
       F       F
Bank Sta=0,2.2
XS Rating Curve= 0
Exp/Cntr=.3,.1

Type RM Length L Ch R = 1 ,2       ,50,50,50
#Sta/Elev= 13
   -18.3   20.86   -15.3   19.86   -12.3   18.86    -9.3   17.86    -6.3   16.66
    -4.5   15.16       0   15.16      .4   13.66     2.3   13.66     2.7   15.36
     4.1   15.36     5.3   14.16    15.3   14.16
#Mann= 3 , 0 , 0
   -18.3    .035       0       0    .035       0     2.7    .035       0
Levee=-1,0,20,-1,2.7,20,,
#XS Ineff= 2 , 0
               0   15.16     2.7           15.36
Permanent Ineff=
       F       F
Bank Sta=0,2.7
XS Rating Curve= 0
Exp/Cntr=.3,.1

Type RM Length L Ch R = 1 ,1       ,24,24,24
#Sta/Elev= 13
   -18.3   19.36   -15.3   18.36   -12.3   17.36    -9.3   16.36    -6.3   15.16
    -4.5   13.66       0   13.66      .4   12.26     2.3   12.26     2.7   13.86
     4.1   13.86     5.3   12.66    15.3   12.66
#Mann= 3 , 0 , 0
   -18.3    .035       0       0    .035       0     2.7    .035       0
Levee=-1,0,20,-1,2.7,20,,
#XS Ineff= 2 , 0
               0   13.66     2.7           13.86
Permanent Ineff=
       F       F
Bank Sta=0,2.7
XS Rating Curve= 0
Exp/Cntr=.3,.1

Type RM Length L Ch R = 1 ,0.026   ,26,26,26
#Sta/Elev= 8
     -10   12.81       0   12.81      .4   11.71     1.6   11.71       2   13.11
     2.5   13.11     2.5   12.91    12.5   12.91
#Mann= 3 , 0 , 0
     -10    .035       0       0    .035       0       2    .035       0
Levee=-1,0,20,-1,2,20,,
#XS Ineff= 2 , 0
               0   12.81       2           13.11
Permanent Ineff=
       F       F
Bank Sta=0,2
XS Rating Curve= 0
Exp/Cntr=.3,.1

Type RM Length L Ch R = 1 ,0       ,0,0,0
#Sta/Elev= 10
   -10.6   11.31     -.6   11.31     -.5   11.41       0   11.41      .2   10.31
     1.4   10.31     1.6   11.81     2.1   11.81     2.2   11.71    12.2   11.71
#Mann= 3 , 0 , 0
   -10.6    .035       0       0    .035       0     1.6    .035       0
Levee=-1,0,20,-1,1.6,20,,
#XS Ineff= 2 , 0
               0   11.41     1.6           11.81
Permanent Ineff=
       F       F
Bank Sta=0,1.6
XS Rating Curve= 0
Exp/Cntr=.3,.1

Chan Stop Cuts=-1