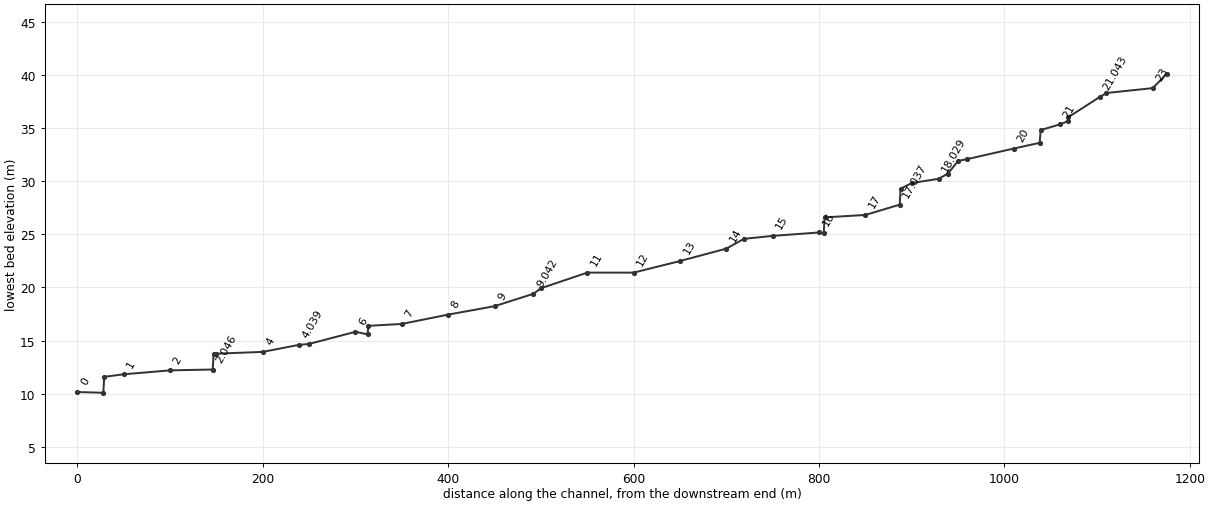
--- kdc.prj (project) ---

Proj Title=KYODONG
Current Plan=p01
Default Exp/Contr=.3,.1
SI Units
Geom File=g01
Flow File=f01
Plan File=p01
Y Axis Title=Elevation
X Axis Title(PF)=Main Channel Distance
X Axis Title(XS)=Station
BEGIN DESCRIPTION:
           BACK WATER COMPUTATION
      APPLICATION OF HEC-2 BY Samju Construction Engineering
      KYODONG-STREEM : 30 YR
END DESCRIPTION:
DSS Export Rating Curves= 0
DSS Export Rating Curve Sorted= 0
DSS Export Volume Flow Curves= 0
DXF OffsetX= 0
DXF OffsetY= 0
DXF ScaleX= 1
DXF ScaleY= 10

--- kdc.p01 (plan) ---

Plan Title=Imported Plan 01
Version=Version 3.0.1  Mar 2001
Short Identifier=Imported Pla
Geom File=g01
Flow File=f01
Subcritical Flow
K Sum by GR= 0
Std Step Tol= 0.003
Critical Tol= 0.003
Num of Std Step Trials= 20
Max Error Tol= 0.1
Flow Tol Ratio= 0.001
Split Flow NTrial= 30
Split Flow Tol= 0.02
Split Flow Ratio= 0.02
Log Output Level= 0
Friction Slope Method= 1
Unsteady Friction Slope Method= 2
Parabolic Critical Depth
Global Vel Dist= 0 , 0 , 0
Global Log Level= 0
CheckData=True
Encroach Param=-1 ,0,0, 0
Computation Interval=1HOUR
Output Interval=1HOUR
Run HTab= 0
Run UNet= 0
Run PostProcess= 0
UNET Theta= 1
UNET ZTol= 0.02
UNET ZSATol= 0.1
UNET MxIter= 20
UNET MaxInSteps= 20
UNET DtIC= 0
UNET DtMin= 0
UNET MaxCRTS= 20
UNET WFStab= 2
UNET SFStab= 1
UNET WFX= 1
UNET SFX= 1
UNET Convert EG Bridges=-1
UNET Use Existing IB Tables=-1
Instantaneous Interval=1HOUR
Write IC File= 0
Write Velocity= 0
Write Detailed= 0

--- kdc.f01 (steady flow) ---

Flow Title=Imported Flow 01
Version=Version 3.0.1  Mar 2001
Number of Profiles= 5
Profile Names=10YR,20YR,30YR,50YR,80YR
River Rch & RM=RIVER-1,Reach-1         ,23.015
   17.07   18.81   19.82   21.11   22.28
River Rch & RM=KYODONG,KYODONG         ,23.015
   17.07   18.81   19.82   21.11   22.28
Boundary for River Rch & Prof#=KYODONG,KYODONG         , 1
Up Type= 0
Dn Type= 3
Dn Slope=.026
Boundary for River Rch & Prof#=KYODONG,KYODONG         , 2
Up Type= 0
Dn Type= 3
Dn Slope=.026
Boundary for River Rch & Prof#=KYODONG,KYODONG         , 3
Up Type= 0
Dn Type= 3
Dn Slope=.026
Boundary for River Rch & Prof#=KYODONG,KYODONG         , 4
Up Type= 0
Dn Type= 3
Dn Slope=.026
Boundary for River Rch & Prof#=KYODONG,KYODONG         , 5
Up Type= 0
Dn Type= 3
Dn Slope=.026
DSS Import GetInterval= 0
DSS Import GetPeak= 0
DSS Import FillOption= 0

--- kdc.g01 (geometry) ---

Geom Title=Imported Geom 01
Version=Version 3.0.1  Mar 2001

River Reach=KYODONG         ,KYODONG
Reach XY= 2
              .5             .95              .5             .05

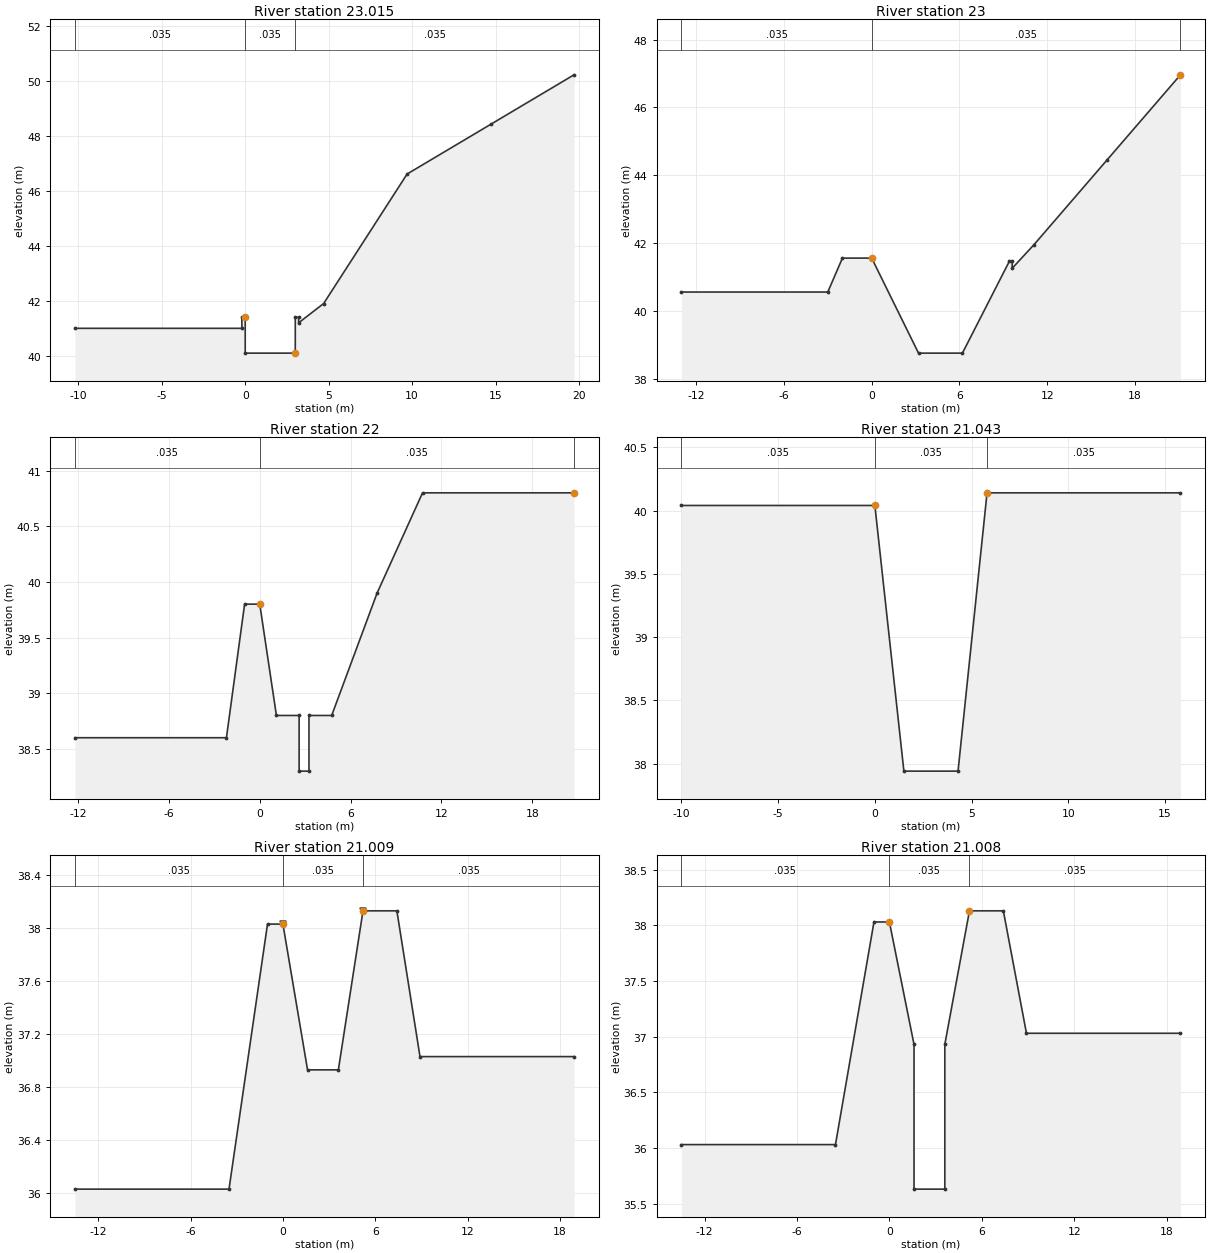
Type RM Length L Ch R = 1 ,23.015  ,15,15,15
#Sta/Elev= 13
   -10.2   41.01     -.2   41.01     -.2   41.41       0   41.41       0   40.11
       3   40.11       3   41.41     3.2   41.41     3.2   41.21     4.7   41.91
     9.7   46.61    14.7   48.41    19.7   50.21
#Mann= 3 , 0 , 0
   -10.2    .035       0       0    .035       0       3    .035       0
Bank Sta=0,3
XS Rating Curve= 0
Exp/Cntr=.3,.1

Type RM Length L Ch R = 1 ,23      ,50,50,50
#Sta/Elev= 12
     -13   40.56      -3   40.56      -2   41.56       0   41.56     3.2   38.76
     6.2   38.76     9.4   41.46     9.6   41.46     9.6   41.26    11.1   41.96
    16.1   44.46    21.1   46.96
#Mann= 3 , 0 , 0
     -13    .035       0       0    .035       0    21.1    .035       0
Bank Sta=0,21.1
XS Rating Curve= 0
Exp/Cntr=.3,.1

Type RM Length L Ch R = 1 ,22      ,7,7,7
#Sta/Elev= 13
   -12.2    38.6    -2.2    38.6      -1    39.8       0    39.8     1.1    38.8
     2.6    38.8     2.6    38.3    3.25    38.3    3.25    38.8    4.75    38.8
    7.75    39.9   10.75    40.8   20.75    40.8
#Mann= 3 , 0 , 0
   -12.2    .035       0       0    .035       0   20.75    .035       0
Bank Sta=0,20.75
XS Rating Curve= 0
Exp/Cntr=.3,.1

Type RM Length L Ch R = 1 ,21.043  ,34,34,34
#Sta/Elev= 6
     -10   40.04       0   40.04     1.5   37.94     4.3   37.94     5.8   40.14
    15.8   40.14
#Mann= 3 , 0 , 0
     -10    .035       0       0    .035       0     5.8    .035       0
Bank Sta=0,5.8
XS Rating Curve= 0
Exp/Cntr=.3,.1

Type RM Length L Ch R = 1 ,21.009  ,1,1,1
#Sta/Elev= 10
   -13.5   36.03    -3.5   36.03      -1   38.03       0   38.03     1.6   36.93
     3.6   36.93     5.2   38.13     7.4   38.13     8.9   37.03    18.9   37.03
#Mann= 3 , 0 , 0
   -13.5    .035       0       0    .035       0     5.2    .035       0
Levee=-1,0,38.03,-1,5.2,38.13,,
Bank Sta=0,5.2
XS Rating Curve= 0
Exp/Cntr=.3,.1

Type RM Length L Ch R = 1 ,21.008  ,8,8,8
#Sta/Elev= 12
   -13.5   36.03    -3.5   36.03      -1   38.03       0   38.03     1.6   36.93
     1.6   35.63     3.6   35.63     3.6   36.93     5.2   38.13     7.4   38.13
     8.9   37.03    18.9   37.03
#Mann= 3 , 0 , 0
   -13.5    .035       0       0    .035       0     5.2    .035       0
Bank Sta=0,5.2
XS Rating Curve= 0
Exp/Cntr=.3,.1

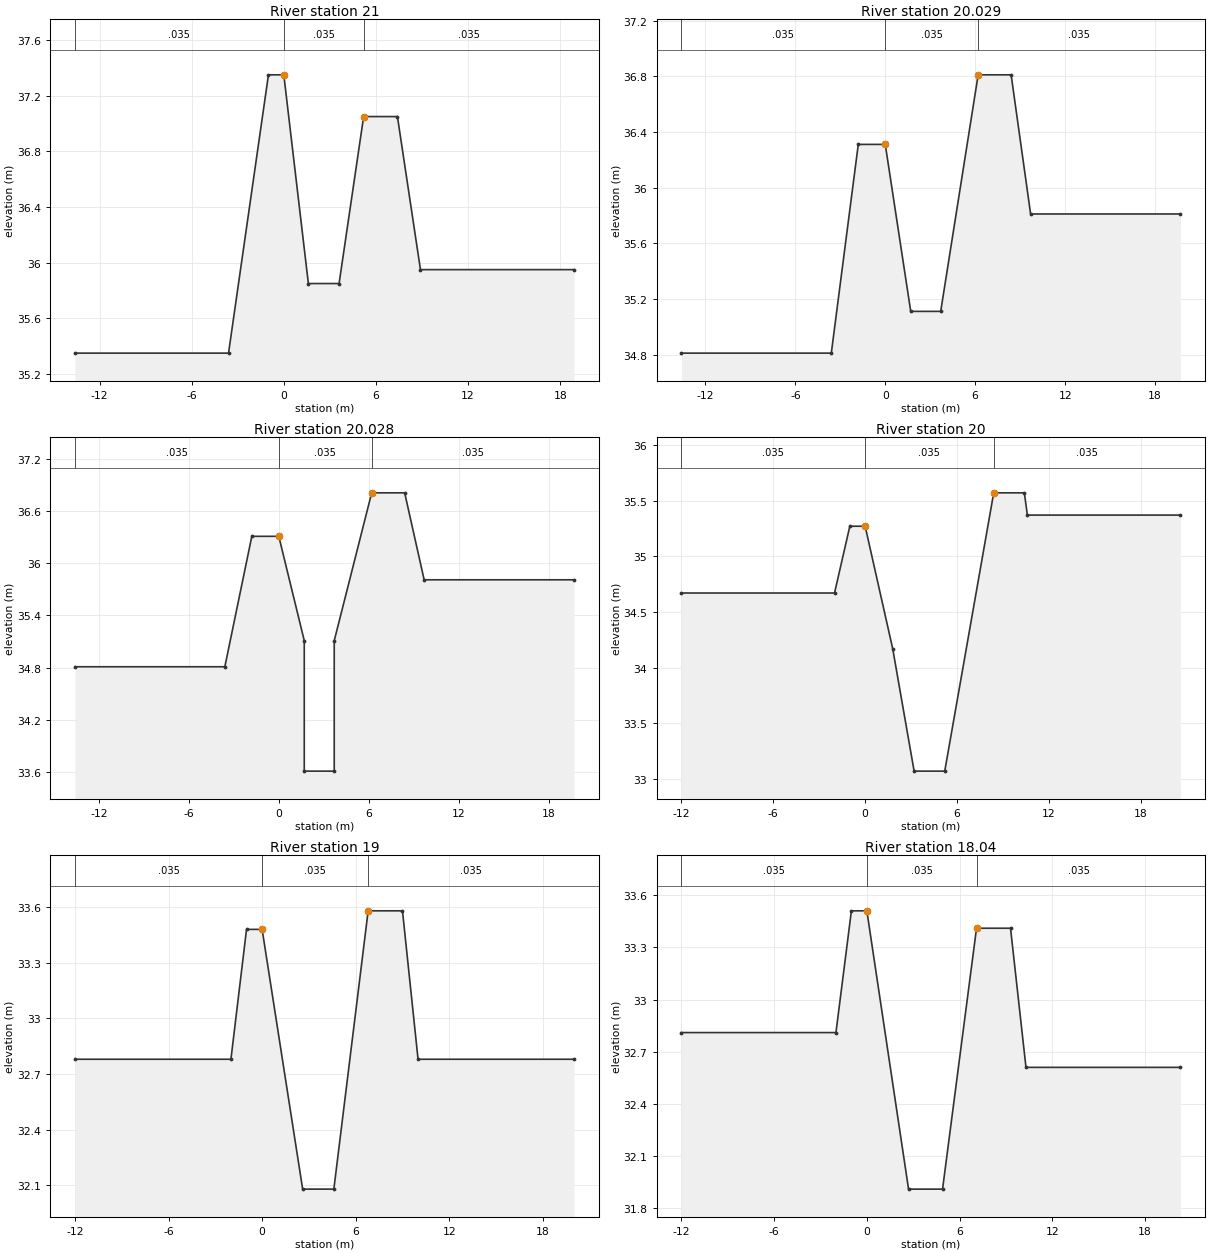
Type RM Length L Ch R = 1 ,21      ,21,21,21
#Sta/Elev= 10
   -13.6   35.35    -3.6   35.35      -1   37.35       0   37.35     1.6   35.85
     3.6   35.85     5.2   37.05     7.4   37.05     8.9   35.95    18.9   35.95
#Mann= 3 , 0 , 0
   -13.6    .035       0       0    .035       0     5.2    .035       0
Bank Sta=0,5.2
XS Rating Curve= 0
Exp/Cntr=.3,.1

Type RM Length L Ch R = 1 ,20.029  ,1,1,1
#Sta/Elev= 10
   -13.6   34.81    -3.6   34.81    -1.8   36.31       0   36.31     1.7   35.11
     3.7   35.11     6.2   36.81     8.4   36.81     9.7   35.81    19.7   35.81
#Mann= 3 , 0 , 0
   -13.6    .035       0       0    .035       0     6.2    .035       0
Bank Sta=0,6.2
XS Rating Curve= 0
Exp/Cntr=.3,.1

Type RM Length L Ch R = 1 ,20.028  ,28,28,28
#Sta/Elev= 12
   -13.6   34.81    -3.6   34.81    -1.8   36.31       0   36.31     1.7   35.11
     1.7   33.61     3.7   33.61     3.7   35.11     6.2   36.81     8.4   36.81
     9.7   35.81    19.7   35.81
#Mann= 3 , 0 , 0
   -13.6    .035       0       0    .035       0     6.2    .035       0
Bank Sta=0,6.2
XS Rating Curve= 0
Exp/Cntr=.3,.1

Type RM Length L Ch R = 1 ,20      ,50,50,50
#Sta/Elev= 11
     -12   34.67      -2   34.67      -1   35.27       0   35.27     1.8   34.17
     3.2   33.07     5.2   33.07     8.4   35.57    10.4   35.57    10.6   35.37
    20.6   35.37
#Mann= 3 , 0 , 0
     -12    .035       0       0    .035       0     8.4    .035       0
Bank Sta=0,8.4
XS Rating Curve= 0
Exp/Cntr=.3,.1

Type RM Length L Ch R = 1 ,19      ,10,10,10
#Sta/Elev= 10
     -12   32.78      -2   32.78      -1   33.48       0   33.48     2.6   32.08
     4.6   32.08     6.8   33.58       9   33.58      10   32.78      20   32.78
#Mann= 3 , 0 , 0
     -12    .035       0       0    .035       0     6.8    .035       0
Bank Sta=0,6.8
XS Rating Curve= 0
Exp/Cntr=.3,.1

Type RM Length L Ch R = 1 ,18.04   ,11,11,11
#Sta/Elev= 10
     -12   32.81      -2   32.81      -1   33.51       0   33.51     2.7   31.91
     4.9   31.91     7.1   33.41     9.3   33.41    10.3   32.61    20.3   32.61
#Mann= 3 , 0 , 0
     -12    .035       0       0    .035       0     7.1    .035       0
Bank Sta=0,7.1
XS Rating Curve= 0
Exp/Cntr=.3,.1

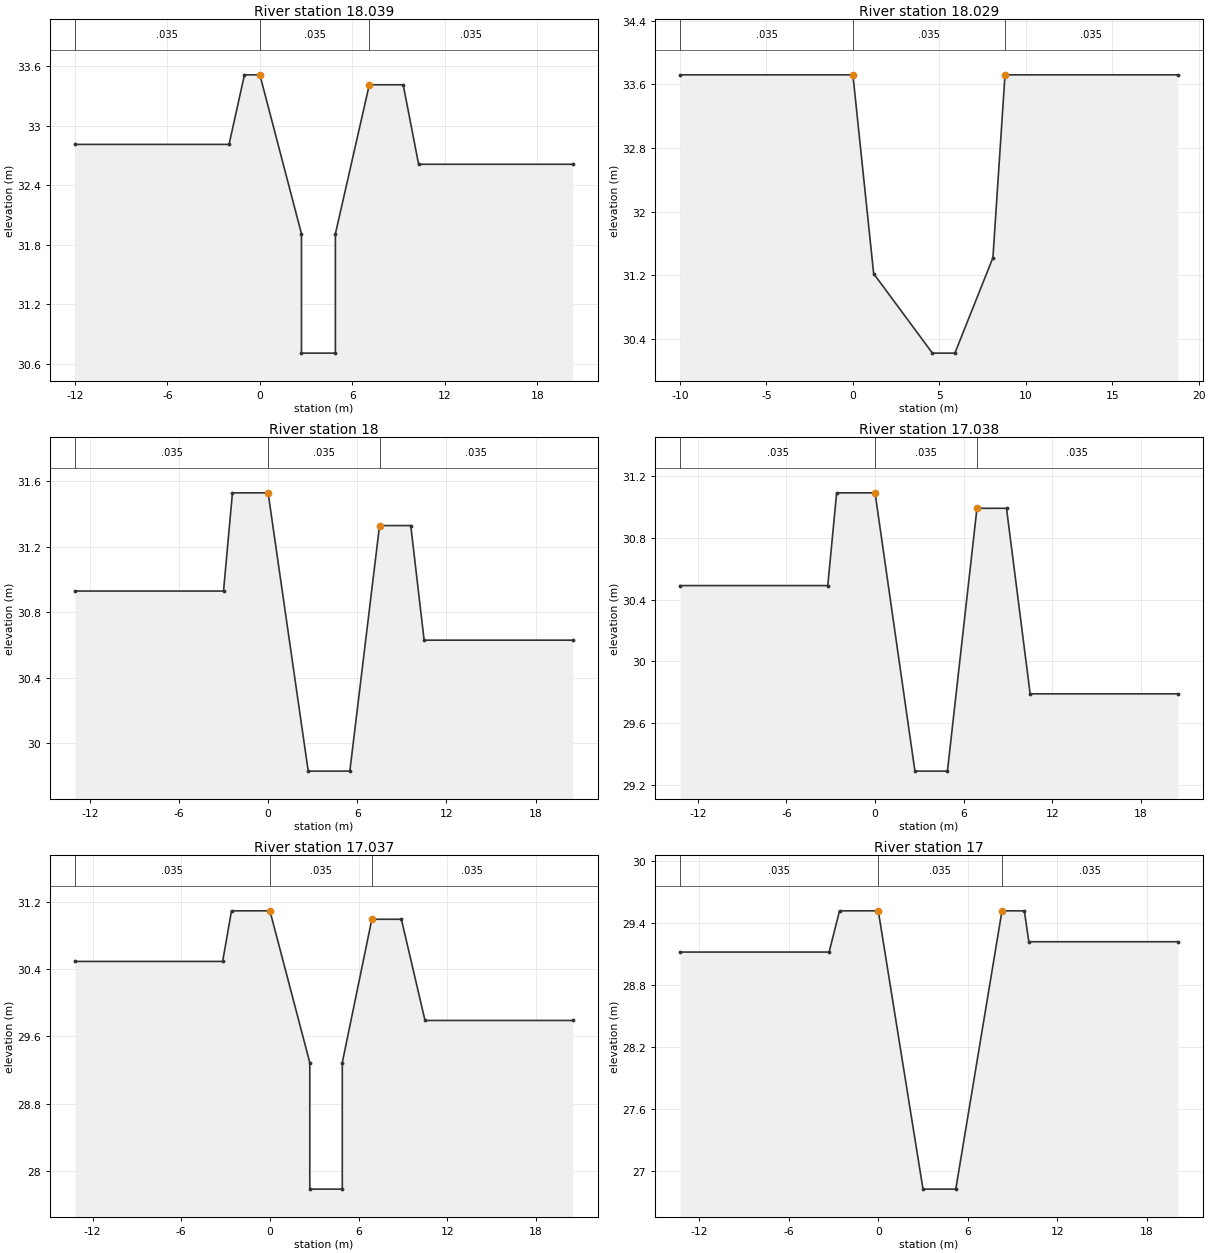
Type RM Length L Ch R = 1 ,18.039  ,10,10,10
#Sta/Elev= 12
     -12   32.81      -2   32.81      -1   33.51       0   33.51     2.7   31.91
     2.7   30.71     4.9   30.71     4.9   31.91     7.1   33.41     9.3   33.41
    10.3   32.61    20.3   32.61
#Mann= 3 , 0 , 0
     -12    .035       0       0    .035       0     7.1    .035       0
Bank Sta=0,7.1
XS Rating Curve= 0
Exp/Cntr=.3,.1

Type RM Length L Ch R = 1 ,18.029  ,29,29,29
#Sta/Elev= 8
     -10   33.72       0   33.72     1.2   31.22     4.6   30.22     5.9   30.22
     8.1   31.42     8.8   33.72    18.8   33.72
#Mann= 3 , 0 , 0
     -10    .035       0       0    .035       0     8.8    .035       0
Bank Sta=0,8.8
XS Rating Curve= 0
Exp/Cntr=.3,.1

Type RM Length L Ch R = 1 ,18      ,12,12,12
#Sta/Elev= 10
     -13   30.93      -3   30.93    -2.4   31.53       0   31.53     2.7   29.83
     5.5   29.83     7.5   31.33     9.6   31.33    10.5   30.63    20.5   30.63
#Mann= 3 , 0 , 0
     -13    .035       0       0    .035       0     7.5    .035       0
Bank Sta=0,7.5
XS Rating Curve= 0
Exp/Cntr=.3,.1

Type RM Length L Ch R = 1 ,17.038  ,1,1,1
#Sta/Elev= 10
   -13.2   30.49    -3.2   30.49    -2.6   31.09       0   31.09     2.7   29.29
     4.9   29.29     6.9   30.99     8.9   30.99    10.5   29.79    20.5   29.79
#Mann= 3 , 0 , 0
   -13.2    .035       0       0    .035       0     6.9    .035       0
Bank Sta=0,6.9
XS Rating Curve= 0
Exp/Cntr=.3,.1

Type RM Length L Ch R = 1 ,17.037  ,37,37,37
#Sta/Elev= 12
   -13.2   30.49    -3.2   30.49    -2.6   31.09       0   31.09     2.7   29.29
     2.7   27.79     4.9   27.79     4.9   29.29     6.9   30.99     8.9   30.99
    10.5   29.79    20.5   29.79
#Mann= 3 , 0 , 0
   -13.2    .035       0       0    .035       0     6.9    .035       0
Bank Sta=0,6.9
XS Rating Curve= 0
Exp/Cntr=.3,.1

Type RM Length L Ch R = 1 ,17      ,44,44,44
#Sta/Elev= 10
   -13.3   29.12    -3.3   29.12    -2.6   29.52       0   29.52       3   26.82
     5.2   26.82     8.3   29.52     9.8   29.52    10.1   29.22    20.1   29.22
#Mann= 3 , 0 , 0
   -13.3    .035       0       0    .035       0     8.3    .035       0
Bank Sta=0,8.3
XS Rating Curve= 0
Exp/Cntr=.3,.1

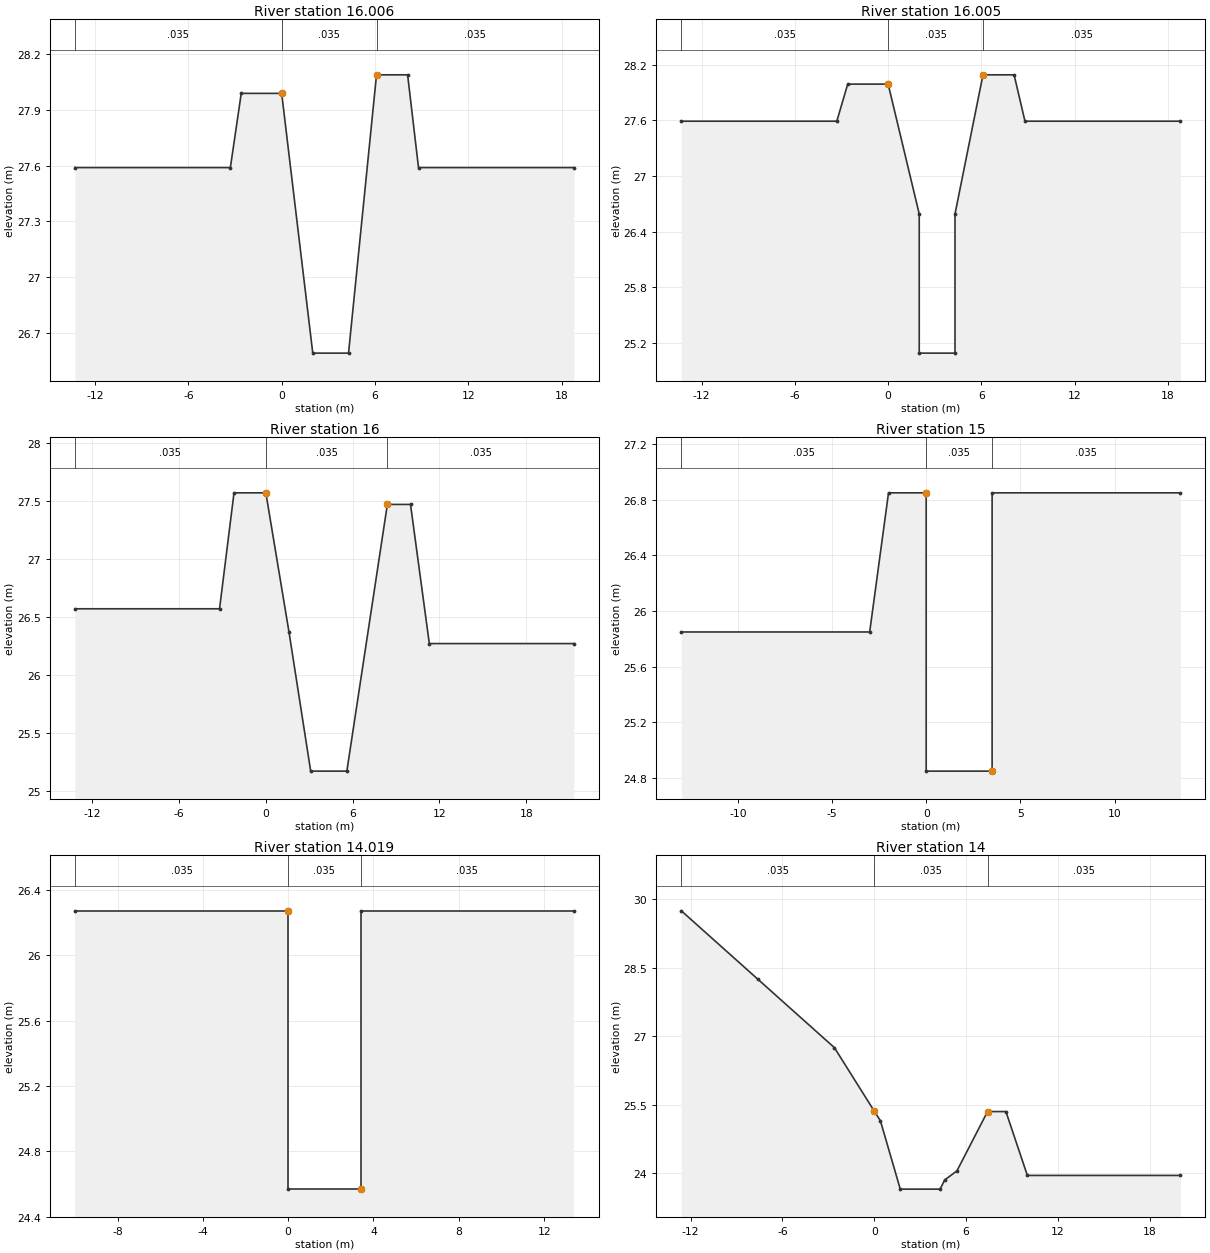
Type RM Length L Ch R = 1 ,16.006  ,1,1,1
#Sta/Elev= 10
   -13.3   27.59    -3.3   27.59    -2.6   27.99       0   27.99       2   26.59
     4.3   26.59     6.1   28.09     8.1   28.09     8.8   27.59    18.8   27.59
#Mann= 3 , 0 , 0
   -13.3    .035       0       0    .035       0     6.1    .035       0
Bank Sta=0,6.1
XS Rating Curve= 0
Exp/Cntr=.3,.1

Type RM Length L Ch R = 1 ,16.005  ,5,5,5
#Sta/Elev= 12
   -13.3   27.59    -3.3   27.59    -2.6   27.99       0   27.99       2   26.59
       2   25.09     4.3   25.09     4.3   26.59     6.1   28.09     8.1   28.09
     8.8   27.59    18.8   27.59
#Mann= 3 , 0 , 0
   -13.3    .035       0       0    .035       0     6.1    .035       0
Bank Sta=0,6.1
XS Rating Curve= 0
Exp/Cntr=.3,.1

Type RM Length L Ch R = 1 ,16      ,50,50,50
#Sta/Elev= 11
   -13.2   26.57    -3.2   26.57    -2.2   27.57       0   27.57     1.6   26.37
     3.1   25.17     5.6   25.17     8.4   27.47      10   27.47    11.3   26.27
    21.3   26.27
#Mann= 3 , 0 , 0
   -13.2    .035       0       0    .035       0     8.4    .035       0
Bank Sta=0,8.4
XS Rating Curve= 0
Exp/Cntr=.3,.1

Type RM Length L Ch R = 1 ,15      ,31,31,31
#Sta/Elev= 8
     -13   25.85      -3   25.85      -2   26.85       0   26.85       0   24.85
     3.5   24.85     3.5   26.85    13.5   26.85
#Mann= 3 , 0 , 0
     -13    .035       0       0    .035       0     3.5    .035       0
Bank Sta=0,3.5
XS Rating Curve= 0
Exp/Cntr=.3,.1

Type RM Length L Ch R = 1 ,14.019  ,19,19,19
#Sta/Elev= 6
     -10   26.27       0   26.27       0   24.57     3.4   24.57     3.4   26.27
    13.4   26.27
#Mann= 3 , 0 , 0
     -10    .035       0       0    .035       0     3.4    .035       0
Bank Sta=0,3.4
XS Rating Curve= 0
Exp/Cntr=.3,.1

Type RM Length L Ch R = 1 ,14      ,50,50,50
#Sta/Elev= 13
   -12.6   29.75    -7.6   28.25    -2.6   26.75       0   25.36      .4   25.15
     1.7   23.65     4.3   23.65     4.6   23.85     5.4   24.05     7.4   25.35
     8.6   25.35      10   23.95      20   23.95
#Mann= 3 , 0 , 0
   -12.6    .035       0       0    .035       0     7.4    .035       0
Bank Sta=0,7.4
XS Rating Curve= 0
Exp/Cntr=.3,.1

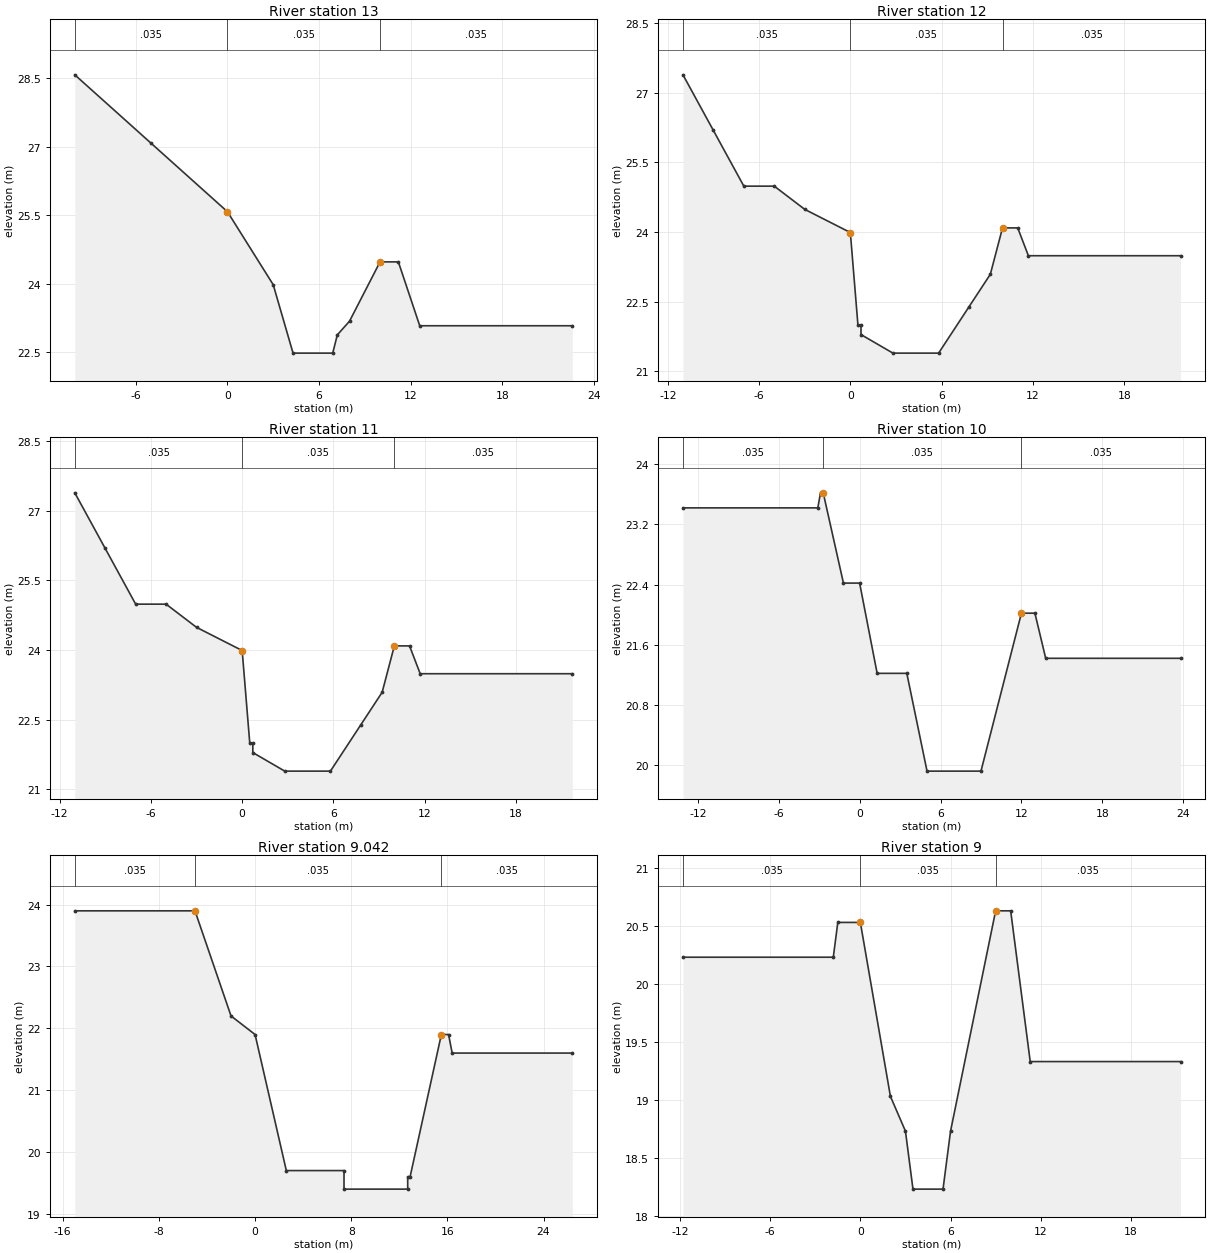
Type RM Length L Ch R = 1 ,13      ,50,50,50
#Sta/Elev= 12
     -10   28.58      -5   27.08       0   25.58       3   23.98     4.3   22.48
     6.9   22.48     7.2   22.88       8   23.18      10   24.48    11.2   24.48
    12.6   23.08    22.6   23.08
#Mann= 3 , 0 , 0
     -10    .035       0       0    .035       0      10    .035       0
Bank Sta=0,10
XS Rating Curve= 0
Exp/Cntr=.3,.1

Type RM Length L Ch R = 1 ,12      ,50,50,50
#Sta/Elev= 17
     -11   27.39      -9   26.19      -7   24.99      -5   24.99      -3   24.49
       0   23.99      .5   21.99      .7   21.99      .7   21.79     2.8   21.39
     5.8   21.39     7.8   22.39     9.2   23.09      10   24.09      11   24.09
    11.7   23.49    21.7   23.49
#Mann= 3 , 0 , 0
     -11    .035       0       0    .035       0      10    .035       0
Bank Sta=0,10
XS Rating Curve= 0
Exp/Cntr=.3,.1

Type RM Length L Ch R = 1 ,11      ,50,50,50
#Sta/Elev= 17
     -11   27.39      -9   26.19      -7   24.99      -5   24.99      -3   24.49
       0   23.99      .5   21.99      .7   21.99      .7   21.79     2.8   21.39
     5.8   21.39     7.8   22.39     9.2   23.09      10   24.09      11   24.09
    11.7   23.49    21.7   23.49
#Mann= 3 , 0 , 0
     -11    .035       0       0    .035       0      10    .035       0
Bank Sta=0,10
XS Rating Curve= 0
Exp/Cntr=.3,.1

Type RM Length L Ch R = 1 ,10      ,8,8,8
#Sta/Elev= 14
   -13.1   23.42    -3.1   23.42    -2.9   23.62    -2.7   23.62    -1.2   22.42
       0   22.42     1.3   21.22     3.5   21.22       5   19.92       9   19.92
      12   22.02      13   22.02    13.8   21.42    23.8   21.42
#Mann= 3 , 0 , 0
   -13.1    .035       0    -2.7    .035       0      12    .035       0
Bank Sta=-2.7,12
XS Rating Curve= 0
Exp/Cntr=.3,.1

Type RM Length L Ch R = 1 ,9.042   ,42,42,42
#Sta/Elev= 14
     -15    23.9      -5    23.9      -2    22.2       0    21.9     2.6    19.7
     7.4    19.7     7.4    19.4    12.7    19.4    12.7    19.6    12.9    19.6
    15.5    21.9    16.1    21.9    16.4    21.6    26.4    21.6
#Mann= 3 , 0 , 0
     -15    .035       0      -5    .035       0    15.5    .035       0
Bank Sta=-5,15.5
XS Rating Curve= 0
Exp/Cntr=.3,.1

Type RM Length L Ch R = 1 ,9       ,50,50,50
#Sta/Elev= 13
   -11.8   20.23    -1.8   20.23    -1.5   20.53       0   20.53       2   19.03
       3   18.73     3.5   18.23     5.5   18.23       6   18.73       9   20.63
      10   20.63    11.3   19.33    21.3   19.33
#Mann= 3 , 0 , 0
   -11.8    .035       0       0    .035       0       9    .035       0
Bank Sta=0,9
XS Rating Curve= 0
Exp/Cntr=.3,.1

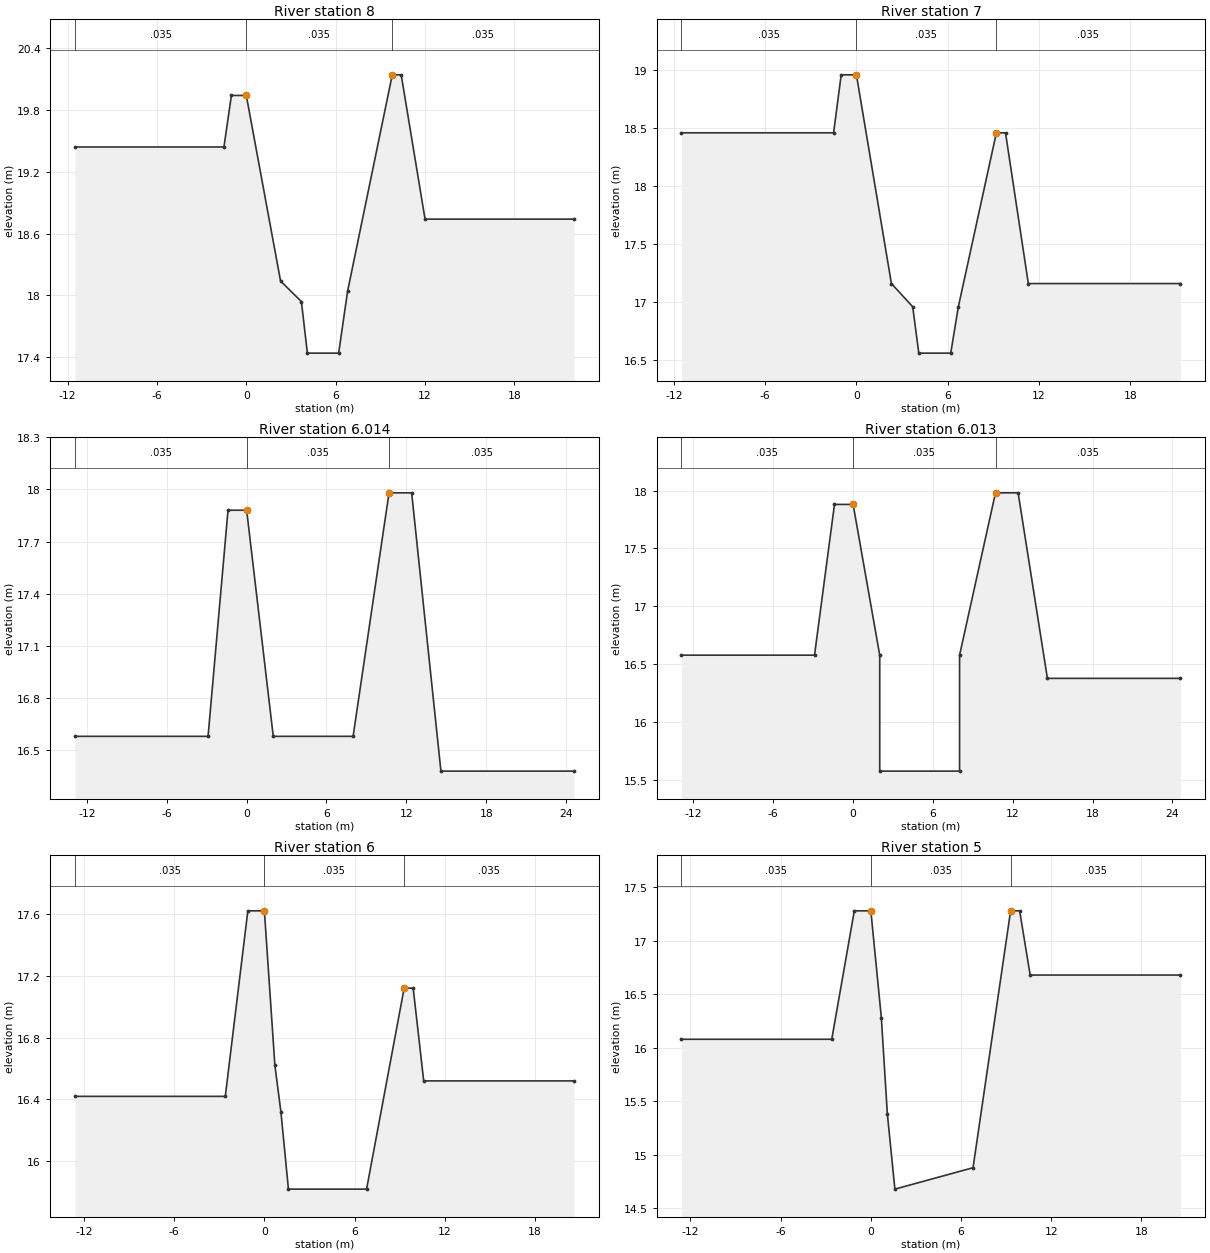
Type RM Length L Ch R = 1 ,8       ,50,50,50
#Sta/Elev= 13
   -11.5   19.44    -1.5   19.44      -1   19.94       0   19.94     2.3   18.14
     3.7   17.94     4.1   17.44     6.2   17.44     6.8   18.04     9.8   20.14
    10.4   20.14      12   18.74      22   18.74
#Mann= 3 , 0 , 0
   -11.5    .035       0       0    .035       0     9.8    .035       0
Bank Sta=0,9.8
XS Rating Curve= 0
Exp/Cntr=.3,.1

Type RM Length L Ch R = 1 ,7       ,36,36,36
#Sta/Elev= 13
   -11.5   18.46    -1.5   18.46      -1   18.96       0   18.96     2.3   17.16
     3.7   16.96     4.1   16.56     6.2   16.56     6.7   16.96     9.2   18.46
     9.8   18.46    11.3   17.16    21.3   17.16
#Mann= 3 , 0 , 0
   -11.5    .035       0       0    .035       0     9.2    .035       0
Bank Sta=0,9.2
XS Rating Curve= 0
Exp/Cntr=.3,.1

Type RM Length L Ch R = 1 ,6.014   ,1,1,1
#Sta/Elev= 10
   -12.9   16.58    -2.9   16.58    -1.4   17.88       0   17.88       2   16.58
       8   16.58    10.7   17.98    12.4   17.98    14.6   16.38    24.6   16.38
#Mann= 3 , 0 , 0
   -12.9    .035       0       0    .035       0    10.7    .035       0
Bank Sta=0,10.7
XS Rating Curve= 0
Exp/Cntr=.3,.1

Type RM Length L Ch R = 1 ,6.013   ,13,13,13
#Sta/Elev= 12
   -12.9   16.58    -2.9   16.58    -1.4   17.88       0   17.88       2   16.58
       2   15.58       8   15.58       8   16.58    10.7   17.98    12.4   17.98
    14.6   16.38    24.6   16.38
#Mann= 3 , 0 , 0
   -12.9    .035       0       0    .035       0    10.7    .035       0
Bank Sta=0,10.7
XS Rating Curve= 0
Exp/Cntr=.3,.1

Type RM Length L Ch R = 1 ,6       ,50,50,50
#Sta/Elev= 12
   -12.6   16.42    -2.6   16.42    -1.1   17.62       0   17.62      .7   16.62
     1.1   16.32     1.6   15.82     6.8   15.82     9.3   17.12     9.9   17.12
    10.6   16.52    20.6   16.52
#Mann= 3 , 0 , 0
   -12.6    .035       0       0    .035       0     9.3    .035       0
Bank Sta=0,9.3
XS Rating Curve= 0
Exp/Cntr=.3,.1

Type RM Length L Ch R = 1 ,5       ,11,11,11
#Sta/Elev= 12
   -12.6   16.08    -2.6   16.08    -1.1   17.28       0   17.28      .7   16.28
     1.1   15.38     1.6   14.68     6.8   14.88     9.3   17.28     9.9   17.28
    10.6   16.68    20.6   16.68
#Mann= 3 , 0 , 0
   -12.6    .035       0       0    .035       0     9.3    .035       0
Bank Sta=0,9.3
XS Rating Curve= 0
Exp/Cntr=.3,.1

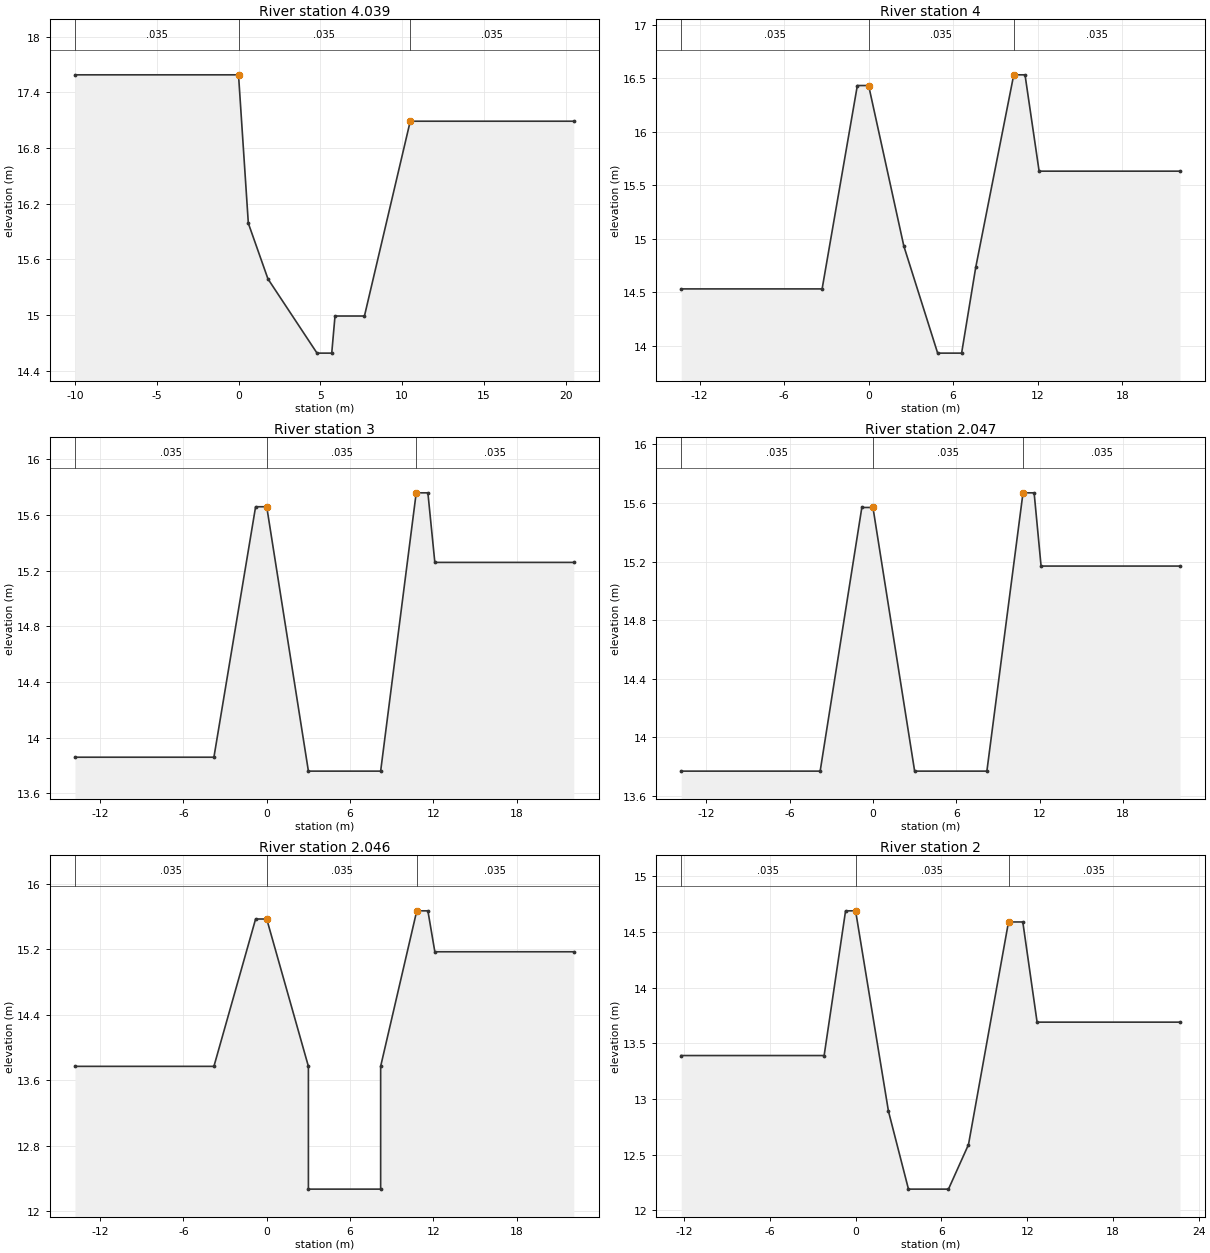
Type RM Length L Ch R = 1 ,4.039   ,39,39,39
#Sta/Elev= 10
     -10   17.59       0   17.59      .6   15.99     1.8   15.39     4.8   14.59
     5.7   14.59     5.9   14.99     7.7   14.99    10.5   17.09    20.5   17.09
#Mann= 3 , 0 , 0
     -10    .035       0       0    .035       0    10.5    .035       0
Bank Sta=0,10.5
XS Rating Curve= 0
Exp/Cntr=.3,.1

Type RM Length L Ch R = 1 ,4       ,50,50,50
#Sta/Elev= 12
   -13.3   14.53    -3.3   14.53     -.8   16.43       0   16.43     2.5   14.93
     4.9   13.93     6.6   13.93     7.6   14.73    10.3   16.53    11.1   16.53
    12.1   15.63    22.1   15.63
#Mann= 3 , 0 , 0
   -13.3    .035       0       0    .035       0    10.3    .035       0
Bank Sta=0,10.3
XS Rating Curve= 0
Exp/Cntr=.3,.1

Type RM Length L Ch R = 1 ,3       ,3,3,3
#Sta/Elev= 10
   -13.8   13.86    -3.8   13.86     -.8   15.66       0   15.66       3   13.76
     8.2   13.76   10.76   15.76    11.6   15.76    12.1   15.26    22.1   15.26
#Mann= 3 , 0 , 0
   -13.8    .035       0       0    .035       0   10.76    .035       0
Bank Sta=0,10.76
XS Rating Curve= 0
Exp/Cntr=.3,.1

Type RM Length L Ch R = 1 ,2.047   ,1,1,1
#Sta/Elev= 10
   -13.8   13.77    -3.8   13.77     -.8   15.57       0   15.57       3   13.77
     8.2   13.77    10.8   15.67    11.6   15.67    12.1   15.17    22.1   15.17
#Mann= 3 , 0 , 0
   -13.8    .035       0       0    .035       0    10.8    .035       0
Bank Sta=0,10.8
XS Rating Curve= 0
Exp/Cntr=.3,.1

Type RM Length L Ch R = 1 ,2.046   ,46,46,46
#Sta/Elev= 12
   -13.8   13.77    -3.8   13.77     -.8   15.57       0   15.57       3   13.77
       3   12.27     8.2   12.27     8.2   13.77    10.8   15.67    11.6   15.67
    12.1   15.17    22.1   15.17
#Mann= 3 , 0 , 0
   -13.8    .035       0       0    .035       0    10.8    .035       0
Bank Sta=0,10.8
XS Rating Curve= 0
Exp/Cntr=.3,.1

Type RM Length L Ch R = 1 ,2       ,50,50,50
#Sta/Elev= 12
   -12.2   13.39    -2.2   13.39     -.7   14.69       0   14.69     2.3   12.89
     3.7   12.19     6.5   12.19     7.9   12.59    10.7   14.59    11.7   14.59
    12.7   13.69    22.7   13.69
#Mann= 3 , 0 , 0
   -12.2    .035       0       0    .035       0    10.7    .035       0
Bank Sta=0,10.7
XS Rating Curve= 0
Exp/Cntr=.3,.1

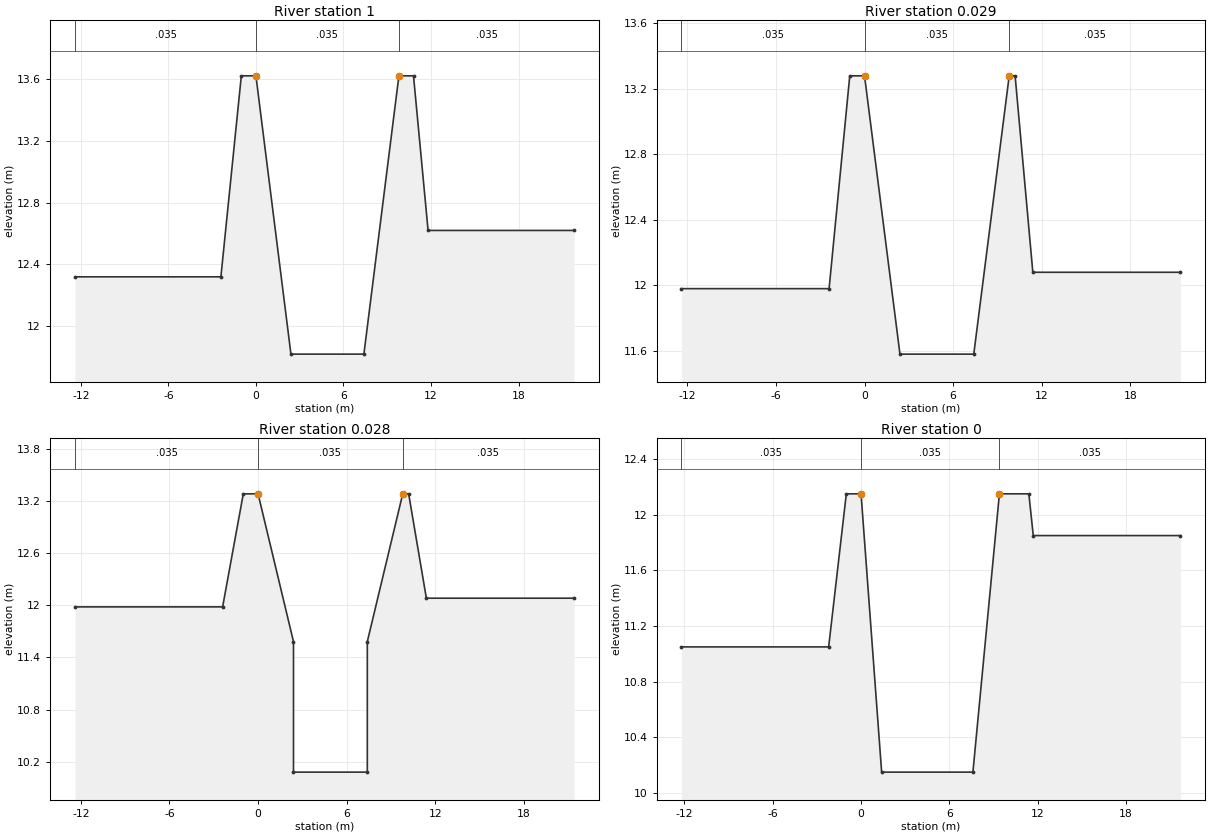
Type RM Length L Ch R = 1 ,1       ,21,21,21
#Sta/Elev= 10
   -12.4   12.32    -2.4   12.32      -1   13.62       0   13.62     2.4   11.82
     7.4   11.82     9.8   13.62    10.8   13.62    11.8   12.62    21.8   12.62
#Mann= 3 , 0 , 0
   -12.4    .035       0       0    .035       0     9.8    .035       0
Bank Sta=0,9.8
XS Rating Curve= 0
Exp/Cntr=.3,.1

Type RM Length L Ch R = 1 ,0.029   ,1,1,1
#Sta/Elev= 10
   -12.4   11.98    -2.4   11.98      -1   13.28       0   13.28     2.4   11.58
     7.4   11.58     9.8   13.28    10.2   13.28    11.4   12.08    21.4   12.08
#Mann= 3 , 0 , 0
   -12.4    .035       0       0    .035       0     9.8    .035       0
Bank Sta=0,9.8
XS Rating Curve= 0
Exp/Cntr=.3,.1

Type RM Length L Ch R = 1 ,0.028   ,28,28,28
#Sta/Elev= 12
   -12.4   11.98    -2.4   11.98      -1   13.28       0   13.28     2.4   11.58
     2.4   10.08     7.4   10.08     7.4   11.58     9.8   13.28    10.2   13.28
    11.4   12.08    21.4   12.08
#Mann= 3 , 0 , 0
   -12.4    .035       0       0    .035       0     9.8    .035       0
Bank Sta=0,9.8
XS Rating Curve= 0
Exp/Cntr=.3,.1

Type RM Length L Ch R = 1 ,0       ,0,0,0
#Sta/Elev= 10
   -12.2   11.05    -2.2   11.05      -1   12.15       0   12.15     1.4   10.15
     7.6   10.15     9.4   12.15    11.4   12.15    11.7   11.85    21.7   11.85
#Mann= 3 , 0 , 0
   -12.2    .035       0       0    .035       0     9.4    .035       0
Bank Sta=0,9.4
XS Rating Curve= 0
Exp/Cntr=.3,.1

Chan Stop Cuts=-1