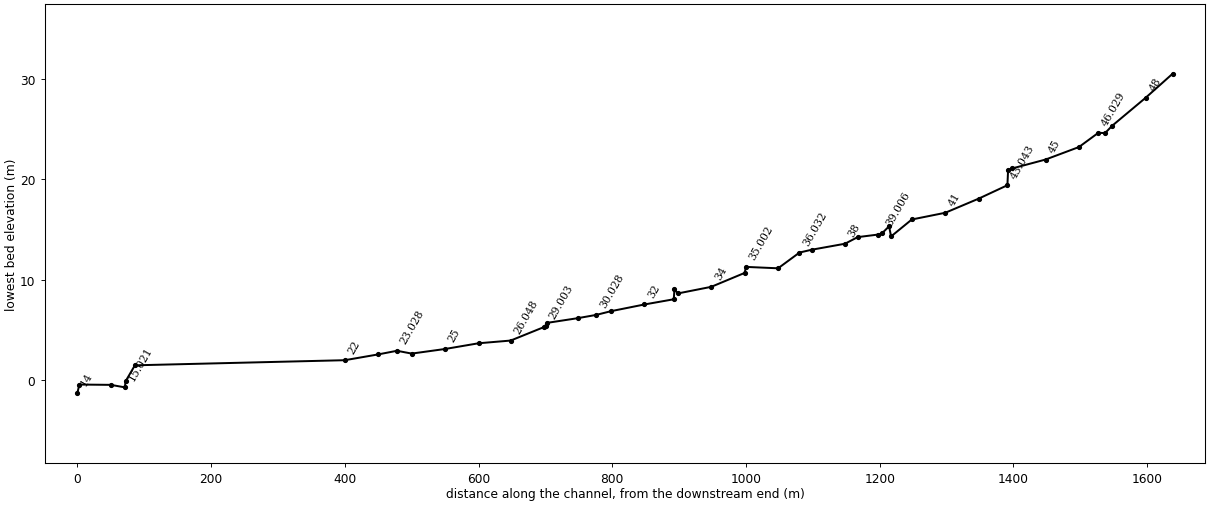
--- JBC.prj (project) ---

Proj Title=JUNGBU
Current Plan=p01
Default Exp/Contr=.3,.1
SI Units
Geom File=g01
Flow File=f01
Plan File=p01
Y Axis Title=Elevation
X Axis Title(PF)=Main Channel Distance
X Axis Title(XS)=Station
BEGIN DESCRIPTION:
           BACK WATER COMPUTATION
      APPLICATION OF HEC-2 BY Samju Construction Engineering
      JOONGBU-STREEM : 30 YR
END DESCRIPTION:
DSS Export Rating Curves= 0
DSS Export Rating Curve Sorted= 0
DSS Export Volume Flow Curves= 0
DXF OffsetX= 0
DXF OffsetY= 0
DXF ScaleX= 1
DXF ScaleY= 10

--- JBC.p01 (plan) ---

Plan Title=Imported Plan 01
Version=Version 3.0.1  Mar 2001
Short Identifier=Imported Pla
Geom File=g01
Flow File=f01
Subcritical Flow
K Sum by GR= 0
Std Step Tol= 0.003
Critical Tol= 0.003
Num of Std Step Trials= 20
Max Error Tol= 0.1
Flow Tol Ratio= 0.001
Split Flow NTrial= 30
Split Flow Tol= 0.02
Split Flow Ratio= 0.02
Log Output Level= 0
Friction Slope Method= 1
Unsteady Friction Slope Method= 2
Parabolic Critical Depth
Global Vel Dist= 0 , 0 , 0
Global Log Level= 0
CheckData=True
Encroach Param=-1 ,0,0, 0
Computation Interval=1HOUR
Output Interval=1HOUR
Run HTab= 0
Run UNet= 0
Run PostProcess= 0
UNET Theta= 1
UNET ZTol= 0.02
UNET ZSATol= 0.1
UNET MxIter= 20
UNET MaxInSteps= 20
UNET DtIC= 0
UNET DtMin= 0
UNET MaxCRTS= 20
UNET WFStab= 2
UNET SFStab= 1
UNET WFX= 1
UNET SFX= 1
UNET Convert EG Bridges=-1
UNET Use Existing IB Tables=-1
Instantaneous Interval=1HOUR
Write IC File= 0
Write Velocity= 0
Write Detailed= 0

--- JBC.f01 (steady flow) ---

Flow Title=Imported Flow 01
Version=Version 3.0.1  Mar 2001
Number of Profiles= 5
Profile Names=10YR,20YR,30YR,50YR,80YR
River Rch & RM=RIVER-1,Reach-1         ,48.04
   26.94   29.68   31.29   33.31   35.17
River Rch & RM=RIVER-1,Reach-1         ,15.036
   32.28   35.58   37.52   39.95    42.2
River Rch & RM=JUNGBU,JUNGBU          ,48.04
   26.94   29.68   31.29   33.31   35.17
River Rch & RM=JUNGBU,JUNGBU          ,15.036
   32.28   35.58   37.52   39.95    42.2
Boundary for River Rch & Prof#=JUNGBU,JUNGBU          , 1
Up Type= 0
Dn Type= 3
Dn Slope=.013
Boundary for River Rch & Prof#=JUNGBU,JUNGBU          , 2
Up Type= 0
Dn Type= 3
Dn Slope=.013
Boundary for River Rch & Prof#=JUNGBU,JUNGBU          , 3
Up Type= 0
Dn Type= 3
Dn Slope=.013
Boundary for River Rch & Prof#=JUNGBU,JUNGBU          , 4
Up Type= 0
Dn Type= 3
Dn Slope=.013
Boundary for River Rch & Prof#=JUNGBU,JUNGBU          , 5
Up Type= 0
Dn Type= 3
Dn Slope=.013
DSS Import GetInterval= 0
DSS Import GetPeak= 0
DSS Import FillOption= 0

--- JBC.g01 (geometry) ---

Geom Title=Imported Geom 01
Version=Version 3.0.1  Mar 2001

River Reach=JUNGBU          ,JUNGBU
Reach XY= 2
              .5             .95              .5             .05

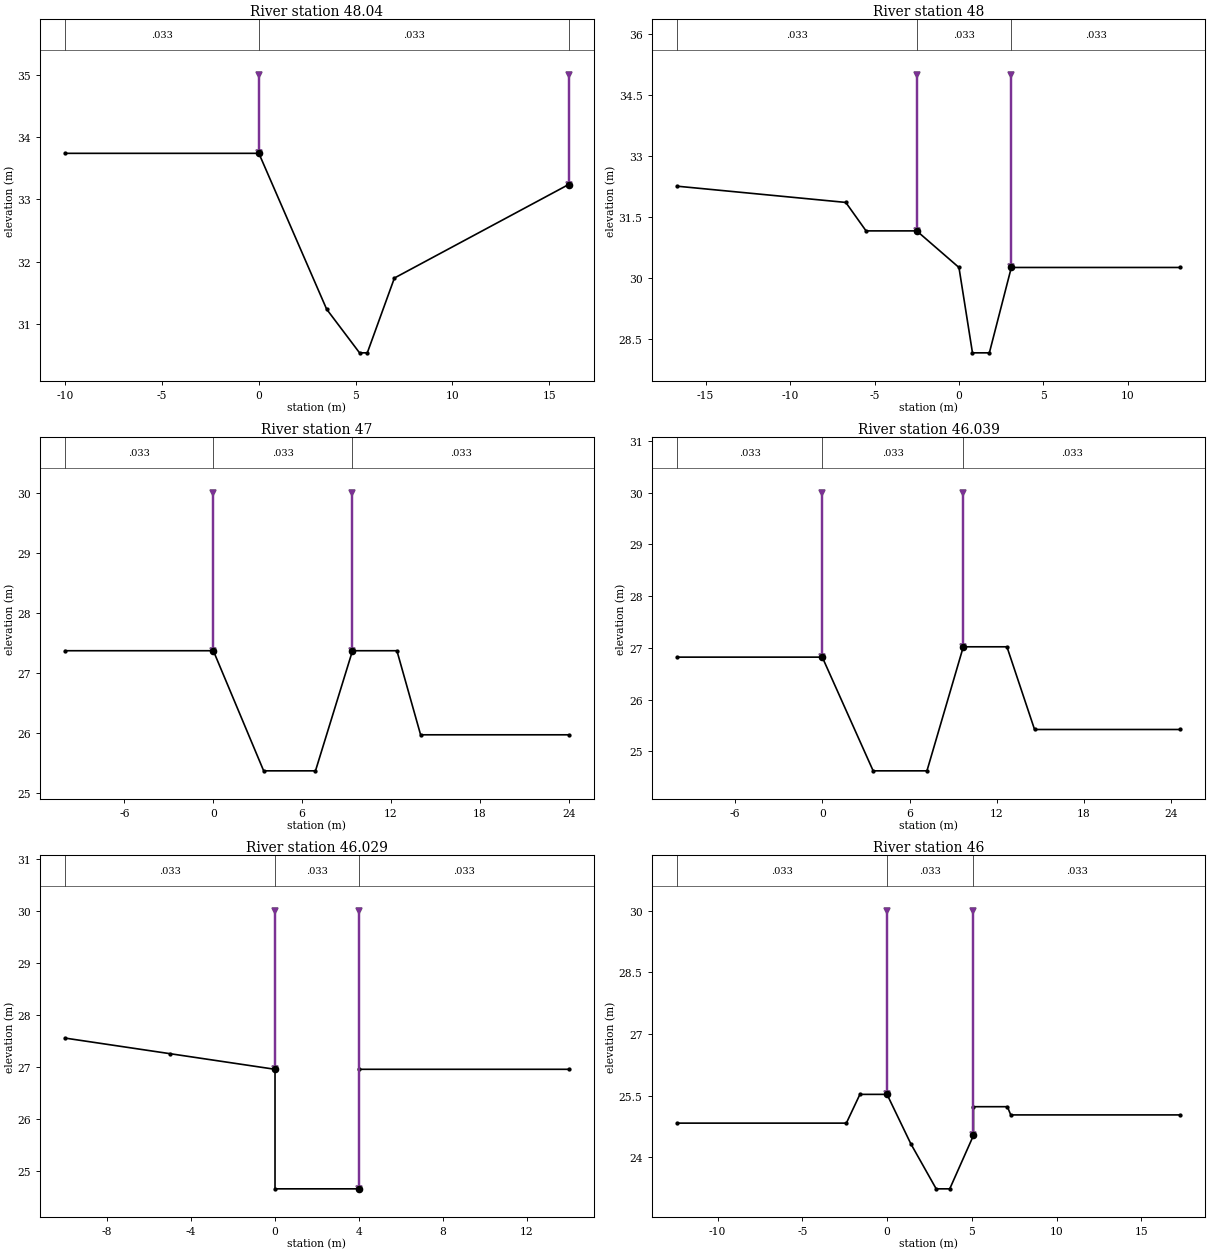
Type RM Length L Ch R = 1 ,48.04   ,40,40,40
#Sta/Elev= 7
     -10   33.74       0   33.74     3.5   31.24     5.2   30.54     5.6   30.54
       7   31.74      16   33.24
#Mann= 3 , 0 , 0
     -10    .033       0       0    .033       0      16    .033       0
Levee=-1,0,35,-1,16,35,,
Bank Sta=0,16
XS Rating Curve= 0
Exp/Cntr=.3,.1

Type RM Length L Ch R = 1 ,48      ,50,50,50
#Sta/Elev= 9
   -16.7   32.26    -6.7   31.86    -5.5   31.16    -2.5   31.16       0   30.26
      .8   28.16     1.8   28.16     3.1   30.26    13.1   30.26
#Mann= 3 , 0 , 0
   -16.7    .033       0    -2.5    .033       0     3.1    .033       0
Levee=-1,-2.5,35,-1,3.1,35,,
Bank Sta=-2.5,3.1
XS Rating Curve= 0
Exp/Cntr=.3,.1

Type RM Length L Ch R = 1 ,47      ,11,11,11
#Sta/Elev= 8
     -10   27.37       0   27.37     3.4   25.37     6.9   25.37     9.4   27.37
    12.4   27.37      14   25.97      24   25.97
#Mann= 3 , 0 , 0
     -10    .033       0       0    .033       0     9.4    .033       0
Levee=-1,0,30,-1,9.4,30,,
Bank Sta=0,9.4
XS Rating Curve= 0
Exp/Cntr=.3,.1

Type RM Length L Ch R = 1 ,46.039  ,10,10,10
#Sta/Elev= 8
     -10   26.82       0   26.82     3.5   24.62     7.2   24.62     9.7   27.02
    12.7   27.02    14.6   25.42   24.62   25.42
#Mann= 3 , 0 , 0
     -10    .033       0       0    .033       0     9.7    .033       0
Levee=-1,0,30,-1,9.7,30,,
Bank Sta=0,9.7
XS Rating Curve= 0
Exp/Cntr=.3,.1

Type RM Length L Ch R = 1 ,46.029  ,29,29,29
#Sta/Elev= 7
     -10   27.55      -5   27.25       0   26.95       0   24.65       4   24.65
       4   26.95      14   26.95
#Mann= 3 , 0 , 0
     -10    .033       0       0    .033       0       4    .033       0
Levee=-1,0,30,-1,4,30,,
Bank Sta=0,4
XS Rating Curve= 0
Exp/Cntr=.3,.1

Type RM Length L Ch R = 1 ,46      ,50,50,50
#Sta/Elev= 12
   -12.4   24.83    -2.4   24.83    -1.6   25.53       0   25.53     1.4   24.33
     2.9   23.23     3.7   23.23     5.1   24.53     5.1   25.23     7.1   25.23
     7.3   25.03    17.3   25.03
#Mann= 3 , 0 , 0
   -12.4    .033       0       0    .033       0     5.1    .033       0
Levee=-1,0,30,-1,5.1,30,,
Bank Sta=0,5.1
XS Rating Curve= 0
Exp/Cntr=.3,.1

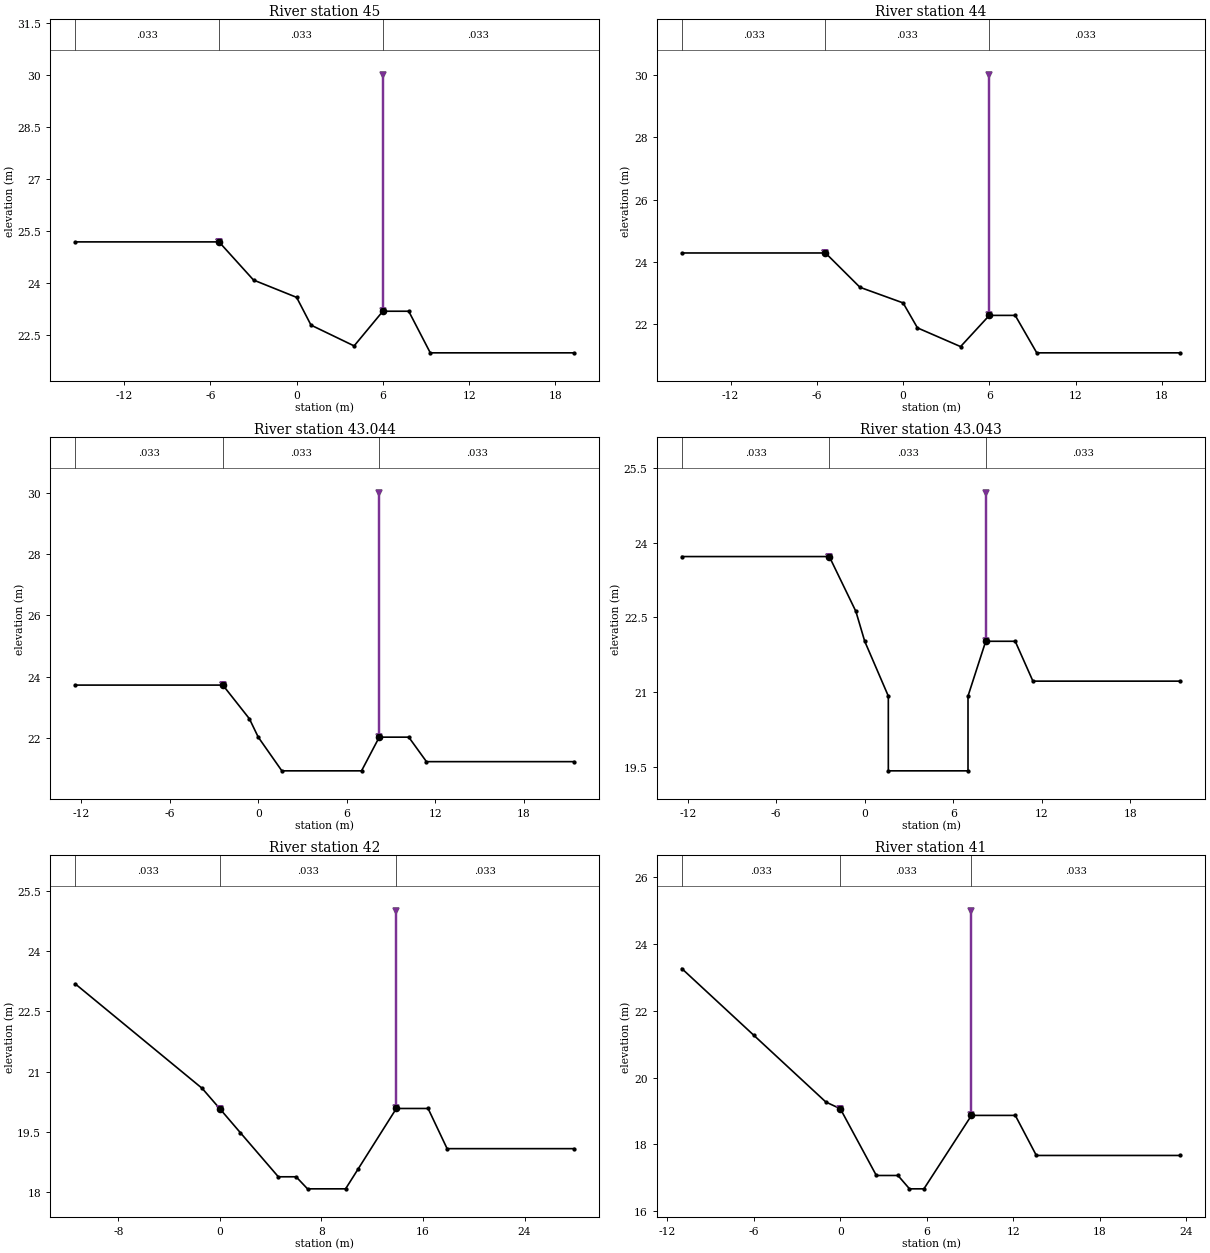
Type RM Length L Ch R = 1 ,45      ,50,50,50
#Sta/Elev= 10
   -15.4   25.18    -5.4   25.18      -3   24.08       0   23.58       1   22.78
       4   22.18       6   23.18     7.8   23.18     9.3   21.98    19.3   21.98
#Mann= 3 , 0 , 0
   -15.4    .033       0    -5.4    .033       0       6    .033       0
Levee=-1,-5.4,25.18,-1,6,30,,
Bank Sta=-5.4,6
XS Rating Curve= 0
Exp/Cntr=.3,.1

Type RM Length L Ch R = 1 ,44      ,6,6,6
#Sta/Elev= 10
   -15.4   24.29    -5.4   24.29      -3   23.19       0   22.69       1   21.89
       4   21.29       6   22.29     7.8   22.29     9.3   21.09    19.3   21.09
#Mann= 3 , 0 , 0
   -15.4    .033       0    -5.4    .033       0       6    .033       0
Levee=-1,-5.4,24.29,-1,6,30,,
Bank Sta=-5.4,6
XS Rating Curve= 0
Exp/Cntr=.3,.1

Type RM Length L Ch R = 1 ,43.044  ,1,1,1
#Sta/Elev= 10
   -12.4   23.72    -2.4   23.72     -.6   22.62       0   22.02     1.6   20.92
       7   20.92     8.2   22.02    10.2   22.02    11.4   21.22    21.4   21.22
#Mann= 3 , 0 , 0
   -12.4    .033       0    -2.4    .033       0     8.2    .033       0
Levee=-1,-2.4,23.72,-1,8.2,30,,
Bank Sta=-2.4,8.2
XS Rating Curve= 0
Exp/Cntr=.3,.1

Type RM Length L Ch R = 1 ,43.043  ,43,43,43
#Sta/Elev= 12
   -12.4   23.72    -2.4   23.72     -.6   22.62       0   22.02     1.6   20.92
     1.6   19.42       7   19.42       7   20.92     8.2   22.02    10.2   22.02
    11.4   21.22    21.4   21.22
#Mann= 3 , 0 , 0
   -12.4    .033       0    -2.4    .033       0     8.2    .033       0
Levee=-1,-2.4,23.72,-1,8.2,25,,
Bank Sta=-2.4,8.2
XS Rating Curve= 0
Exp/Cntr=.3,.1

Type RM Length L Ch R = 1 ,42      ,50,50,50
#Sta/Elev= 13
   -11.4   23.18    -1.4   20.58       0   20.07     1.6   19.48     4.6   18.38
       6   18.38     6.9   18.08     9.9   18.08    10.9   18.58    13.9   20.08
    16.4   20.08    17.9   19.08    27.9   19.08
#Mann= 3 , 0 , 0
   -11.4    .033       0       0    .033       0    13.9    .033       0
Levee=-1,0,20.07,-1,13.9,25,,
Bank Sta=0,13.9
XS Rating Curve= 0
Exp/Cntr=.3,.1

Type RM Length L Ch R = 1 ,41      ,50,50,50
#Sta/Elev= 12
     -11   23.27      -6   21.27      -1   19.27       0   19.07     2.5   17.07
       4   17.07     4.8   16.67     5.8   16.67     9.1   18.87   12.14   18.87
    13.6   17.67    23.6   17.67
#Mann= 3 , 0 , 0
     -11    .033       0       0    .033       0     9.1    .033       0
Levee=-1,0,19.07,-1,9.1,25,,
Bank Sta=0,9.1
XS Rating Curve= 0
Exp/Cntr=.3,.1

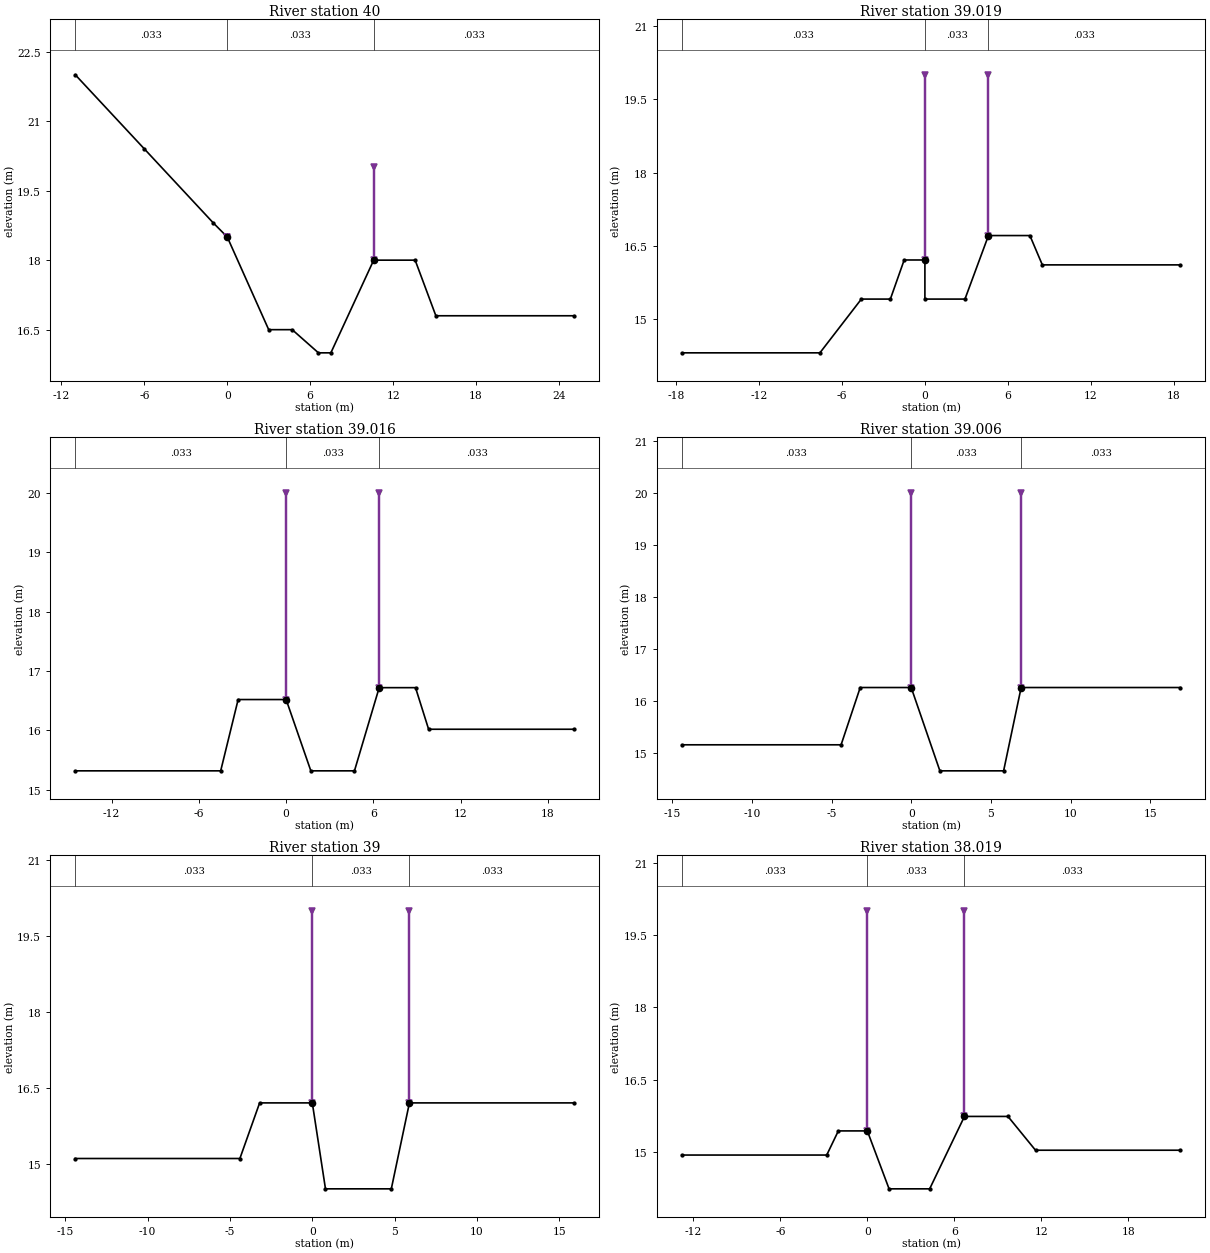
Type RM Length L Ch R = 1 ,40      ,31,31,31
#Sta/Elev= 12
     -11      22      -6    20.4      -1    18.8       0    18.5       3    16.5
     4.7    16.5     6.6      16     7.5      16    10.6      18    13.6      18
    15.1    16.8    25.1    16.8
#Mann= 3 , 0 , 0
     -11    .033       0       0    .033       0    10.6    .033       0
Levee=-1,0,18.5,-1,10.6,20,,
Bank Sta=0,10.6
XS Rating Curve= 0
Exp/Cntr=.3,.1

Type RM Length L Ch R = 1 ,39.019  ,3,3,3
#Sta/Elev= 12
   -17.6   14.31    -7.6   14.31    -4.6   15.41    -2.5   15.41    -1.5   16.21
       0   16.21       0   15.41     2.9   15.41     4.6   16.71     7.6   16.71
     8.5   16.11    18.5   16.11
#Mann= 3 , 0 , 0
   -17.6    .033       0       0    .033       0     4.6    .033       0
Levee=-1,0,20,-1,4.6,20,,
Bank Sta=0,4.6
XS Rating Curve= 0
Exp/Cntr=.3,.1

Type RM Length L Ch R = 1 ,39.016  ,10,10,10
#Sta/Elev= 10
   -14.5   15.32    -4.5   15.32    -3.3   16.52       0   16.52     1.7   15.32
     4.7   15.32     6.4   16.72     8.9   16.72     9.8   16.02    19.8   16.02
#Mann= 3 , 0 , 0
   -14.5    .033       0       0    .033       0     6.4    .033       0
Levee=-1,0,20,-1,6.4,20,,
Bank Sta=0,6.4
XS Rating Curve= 0
Exp/Cntr=.3,.1

Type RM Length L Ch R = 1 ,39.006  ,6,6,6
#Sta/Elev= 8
   -14.4   15.16    -4.4   15.16    -3.2   16.26       0   16.26     1.8   14.66
     5.8   14.66     6.9   16.26    16.9   16.26
#Mann= 3 , 0 , 0
   -14.4    .033       0       0    .033       0     6.9    .033       0
Levee=-1,0,20,-1,6.9,20,,
Bank Sta=0,6.9
XS Rating Curve= 0
Exp/Cntr=.3,.1

Type RM Length L Ch R = 1 ,39      ,31,31,31
#Sta/Elev= 8
   -14.4    15.1    -4.4    15.1    -3.2    16.2       0    16.2      .8    14.5
     4.8    14.5     5.9    16.2    15.9    16.2
#Mann= 3 , 0 , 0
   -14.4    .033       0       0    .033       0     5.9    .033       0
Levee=-1,0,20,-1,5.9,20,,
Bank Sta=0,5.9
XS Rating Curve= 0
Exp/Cntr=.3,.1

Type RM Length L Ch R = 1 ,38.019  ,19,19,19
#Sta/Elev= 10
   -12.8   14.94    -2.8   14.94      -2   15.44       0   15.44     1.5   14.24
     4.3   14.24     6.7   15.74     9.7   15.74    11.6   15.04    21.6   15.04
#Mann= 3 , 0 , 0
   -12.8    .033       0       0    .033       0     6.7    .033       0
Levee=-1,0,20,-1,6.7,20,,
Bank Sta=0,6.7
XS Rating Curve= 0
Exp/Cntr=.3,.1

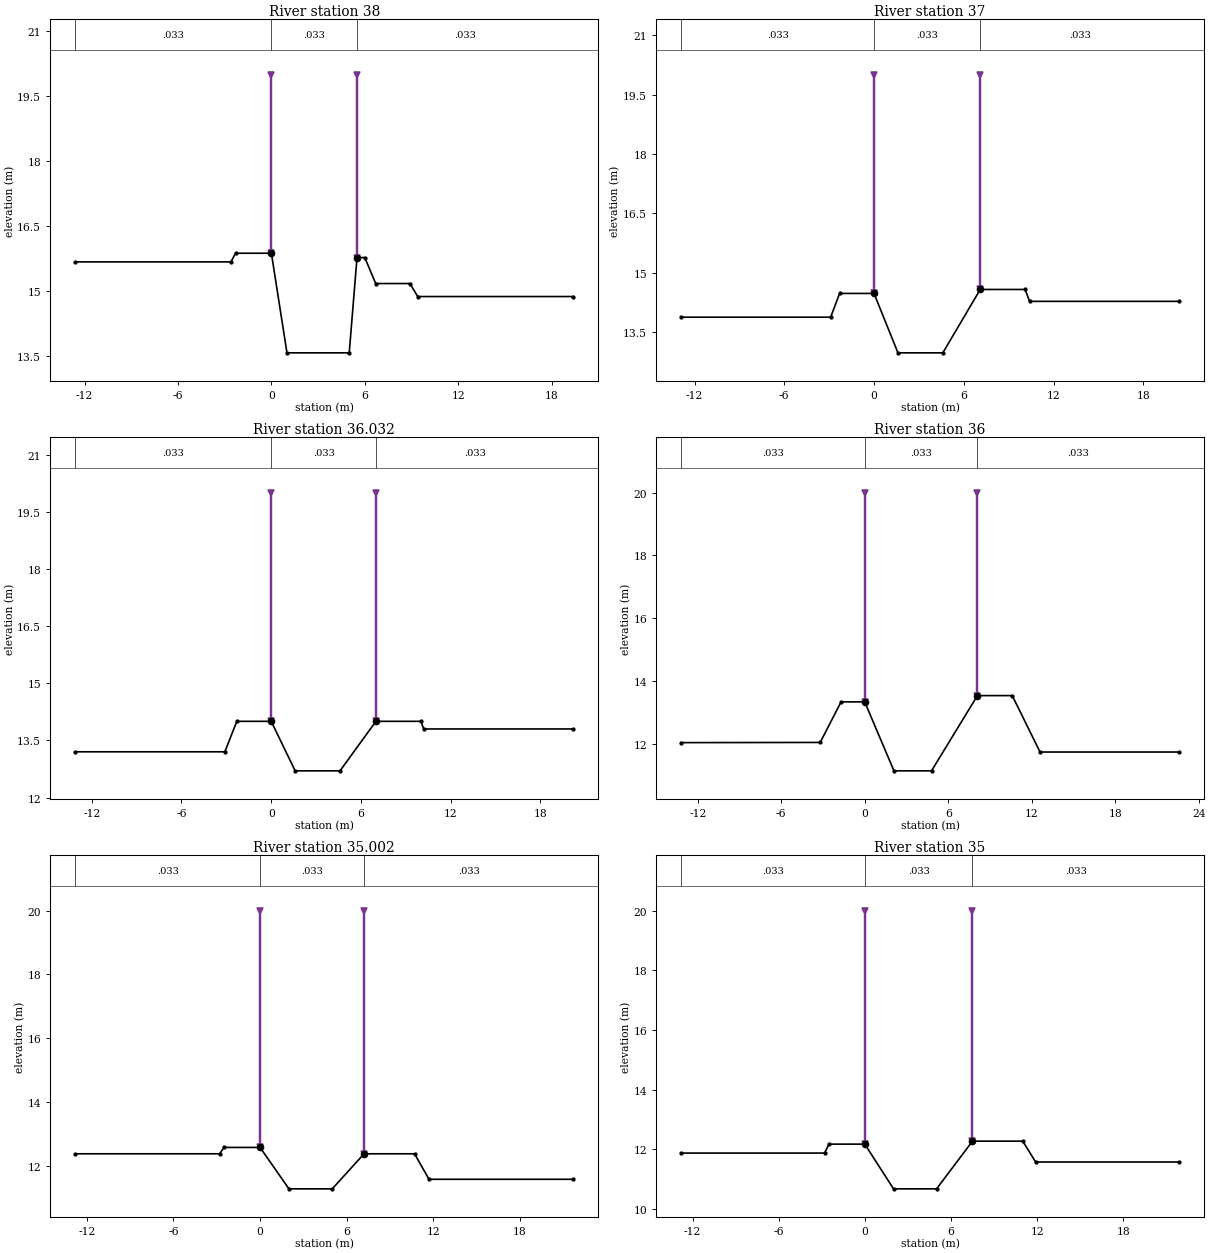
Type RM Length L Ch R = 1 ,38      ,50,50,50
#Sta/Elev= 12
   -12.6   15.68    -2.6   15.68    -2.3   15.88       0   15.88       1   13.58
       5   13.58     5.5   15.78       6   15.78     6.7   15.18     8.9   15.18
     9.4   14.88    19.4   14.88
#Mann= 3 , 0 , 0
   -12.6    .033       0       0    .033       0     5.5    .033       0
Levee=-1,0,20,-1,5.5,20,,
Bank Sta=0,5.5
XS Rating Curve= 0
Exp/Cntr=.3,.1

Type RM Length L Ch R = 1 ,37      ,18,18,18
#Sta/Elev= 10
   -12.9   13.88    -2.9   13.88    -2.3   14.48       0   14.48     1.6   12.98
     4.6   12.98     7.1   14.58    10.1   14.58    10.4   14.28    20.4   14.28
#Mann= 3 , 0 , 0
   -12.9    .033       0       0    .033       0     7.1    .033       0
Levee=-1,0,20,-1,7.1,20,,
Bank Sta=0,7.1
XS Rating Curve= 0
Exp/Cntr=.3,.1

Type RM Length L Ch R = 1 ,36.032  ,32,32,32
#Sta/Elev= 10
   -13.1    13.2    -3.1    13.2    -2.3      14       0      14     1.6    12.7
     4.6    12.7       7      14      10      14    10.2    13.8    20.2    13.8
#Mann= 3 , 0 , 0
   -13.1    .033       0       0    .033       0       7    .033       0
Levee=-1,0,20,-1,7,20,,
Bank Sta=0,7
XS Rating Curve= 0
Exp/Cntr=.3,.1

Type RM Length L Ch R = 1 ,36      ,48,48,48
#Sta/Elev= 10
   -13.2   12.03    -3.2  12.036    -1.7   13.33       0   13.33     2.1   11.13
     4.8   11.13     8.1   13.53    10.6   13.53    12.6   11.73    22.6   11.73
#Mann= 3 , 0 , 0
   -13.2    .033       0       0    .033       0     8.1    .033       0
Levee=-1,0,20,-1,8.1,20,,
Bank Sta=0,8.1
XS Rating Curve= 0
Exp/Cntr=.3,.1

Type RM Length L Ch R = 1 ,35.002  ,2,2,2
#Sta/Elev= 10
   -12.8   12.37    -2.8   12.37    -2.5   12.57       0   12.57       2   11.27
       5   11.27     7.2   12.37    10.7   12.37    11.7   11.57    21.7   11.57
#Mann= 3 , 0 , 0
   -12.8    .033       0       0    .033       0     7.2    .033       0
Levee=-1,0,20,-1,7.2,20,,
Bank Sta=0,7.2
XS Rating Curve= 0
Exp/Cntr=.3,.1

Type RM Length L Ch R = 1 ,35      ,50,50,50
#Sta/Elev= 10
   -12.8   11.87    -2.8   11.87    -2.5   12.17       0   12.17       2   10.67
       5   10.67     7.5   12.27      11   12.27    11.9   11.57    21.9   11.57
#Mann= 3 , 0 , 0
   -12.8    .033       0       0    .033       0     7.5    .033       0
Levee=-1,0,20,-1,7.5,20,,
Bank Sta=0,7.5
XS Rating Curve= 0
Exp/Cntr=.3,.1

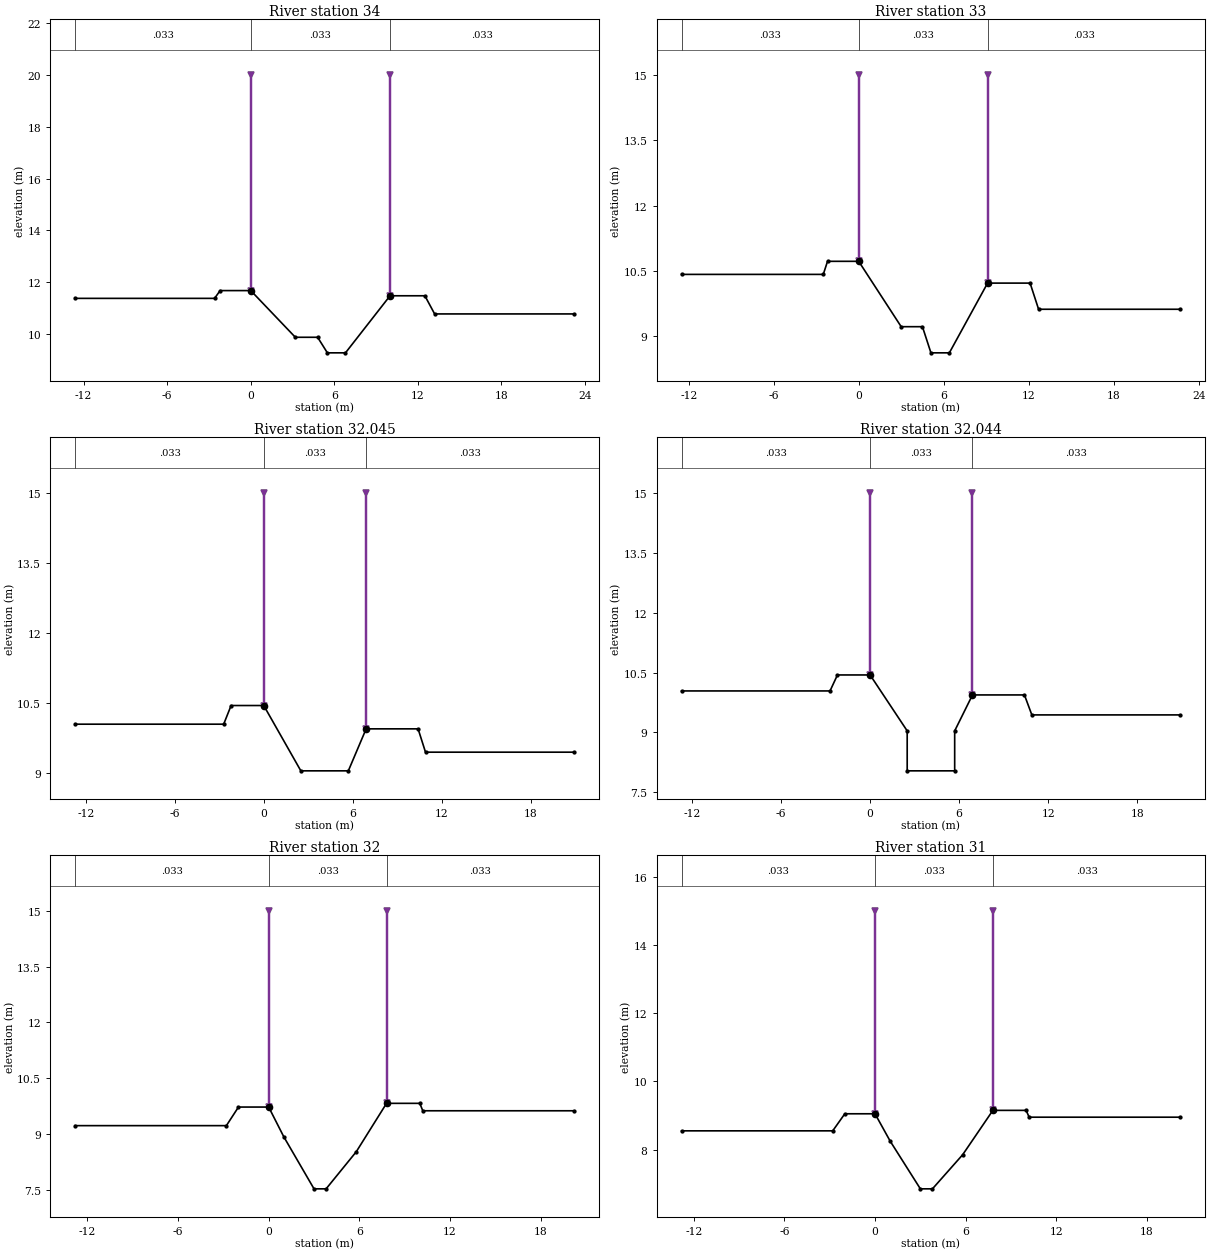
Type RM Length L Ch R = 1 ,34      ,50,50,50
#Sta/Elev= 12
   -12.6   11.38    -2.6   11.38    -2.2   11.68       0   11.68     3.2    9.88
     4.8    9.88     5.5    9.28     6.8    9.28      10   11.48    12.5   11.48
    13.2   10.78    23.2   10.78
#Mann= 3 , 0 , 0
   -12.6    .033       0       0    .033       0      10    .033       0
Levee=-1,0,20,-1,10,20,,
Bank Sta=0,10
XS Rating Curve= 0
Exp/Cntr=.3,.1

Type RM Length L Ch R = 1 ,33      ,5,5,5
#Sta/Elev= 12
   -12.5   10.42    -2.5   10.42    -2.2   10.72       0   10.72       3    9.22
     4.5    9.22     5.1    8.62     6.4    8.62     9.1   10.22    12.1   10.22
    12.7    9.62    22.7    9.62
#Mann= 3 , 0 , 0
   -12.5    .033       0       0    .033       0     9.1    .033       0
Levee=-1,0,15,-1,9.1,15,,
Bank Sta=0,9.1
XS Rating Curve= 0
Exp/Cntr=.3,.1

Type RM Length L Ch R = 1 ,32.045  ,1,1,1
#Sta/Elev= 10
   -12.7   10.04    -2.7   10.04    -2.2   10.44       0   10.44     2.5    9.04
     5.7    9.04     6.9    9.94    10.4    9.94    10.9    9.44    20.9    9.44
#Mann= 3 , 0 , 0
   -12.7    .033       0       0    .033       0     6.9    .033       0
Levee=-1,0,15,-1,6.9,15,,
Bank Sta=0,6.9
XS Rating Curve= 0
Exp/Cntr=.3,.1

Type RM Length L Ch R = 1 ,32.044  ,44,44,44
#Sta/Elev= 12
   -12.7   10.04    -2.7   10.04    -2.2   10.44       0   10.44     2.5    9.04
     2.5    8.04     5.7    8.04     5.7    9.04     6.9    9.94    10.4    9.94
    10.9    9.44    20.9    9.44
#Mann= 3 , 0 , 0
   -12.7    .033       0       0    .033       0     6.9    .033       0
Levee=-1,0,15,-1,6.9,15,,
Bank Sta=0,6.9
XS Rating Curve= 0
Exp/Cntr=.3,.1

Type RM Length L Ch R = 1 ,32      ,50,50,50
#Sta/Elev= 12
   -12.8    9.22    -2.8    9.22      -2    9.72       0    9.72       1    8.92
       3    7.52     3.8    7.52     5.8    8.52     7.8    9.82      10    9.82
    10.2    9.62    20.2    9.62
#Mann= 3 , 0 , 0
   -12.8    .033       0       0    .033       0     7.8    .033       0
Levee=-1,0,15,-1,7.8,15,,
Bank Sta=0,7.8
XS Rating Curve= 0
Exp/Cntr=.3,.1

Type RM Length L Ch R = 1 ,31      ,22,22,22
#Sta/Elev= 12
   -12.8    8.55    -2.8    8.55      -2    9.05       0    9.05       1    8.25
       3    6.85     3.8    6.85     5.8    7.85     7.8    9.15      10    9.15
    10.2    8.95    20.2    8.95
#Mann= 3 , 0 , 0
   -12.8    .033       0       0    .033       0     7.8    .033       0
Levee=-1,0,15,-1,7.8,15,,
Bank Sta=0,7.8
XS Rating Curve= 0
Exp/Cntr=.3,.1

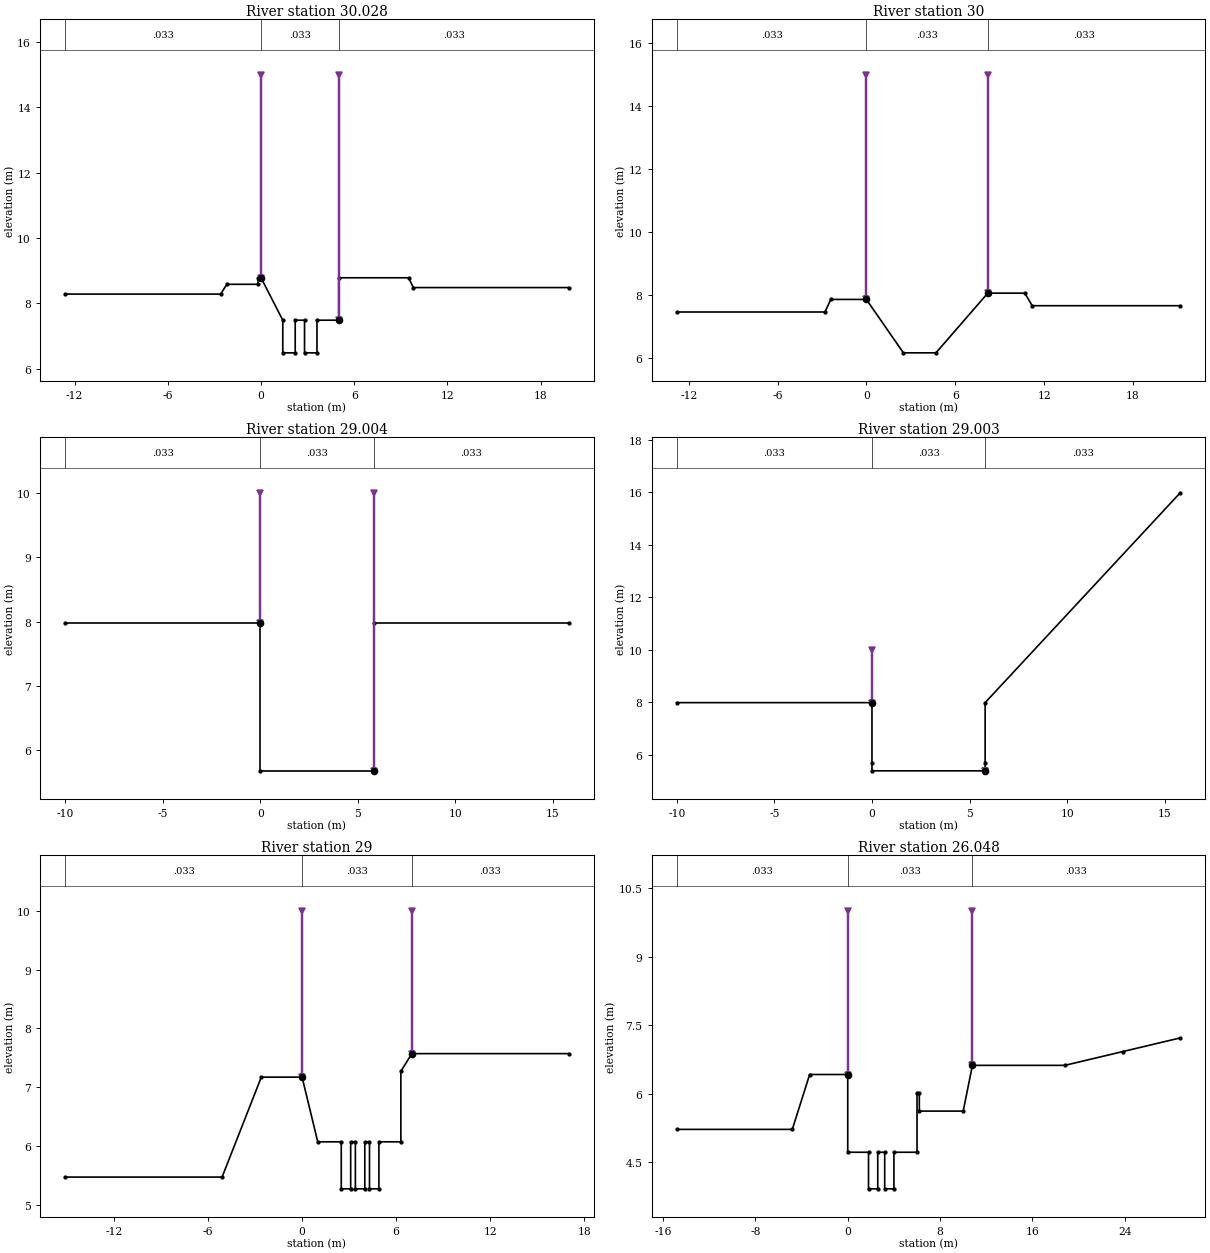
Type RM Length L Ch R = 1 ,30.028  ,28,28,28
#Sta/Elev= 19
   -12.6    8.28    -2.6    8.28    -2.2    8.58     -.2    8.58     -.2    8.78
       0    8.78     1.4    7.48     1.4    6.48     2.2    6.48     2.2    7.48
     2.8    7.48     2.8    6.48     3.6    6.48     3.6    7.48       5    7.48
       5    8.78     9.5    8.78     9.8    8.48    19.8    8.48
#Mann= 3 , 0 , 0
   -12.6    .033       0       0    .033       0       5    .033       0
Levee=-1,0,15,-1,5,15,,
Bank Sta=0,5
XS Rating Curve= 0
Exp/Cntr=.3,.1

Type RM Length L Ch R = 1 ,30      ,46,46,46
#Sta/Elev= 10
   -12.8    7.45    -2.8    7.45    -2.4    7.85       0    7.85     2.5    6.15
     4.7    6.15     8.2    8.05    10.7    8.05    11.2    7.65    21.2    7.65
#Mann= 3 , 0 , 0
   -12.8    .033       0       0    .033       0     8.2    .033       0
Levee=-1,0,15,-1,8.2,15,,
Bank Sta=0,8.2
XS Rating Curve= 0
Exp/Cntr=.3,.1

Type RM Length L Ch R = 1 ,29.004  ,1,1,1
#Sta/Elev= 6
     -10    7.98       0    7.98       0    5.68     5.8    5.68     5.8    7.98
    15.8    7.98
#Mann= 3 , 0 , 0
     -10    .033       0       0    .033       0     5.8    .033       0
Levee=-1,0,10,-1,5.8,10,,
Bank Sta=0,5.8
XS Rating Curve= 0
Exp/Cntr=.3,.1

Type RM Length L Ch R = 1 ,29.003  ,3,3,3
#Sta/Elev= 8
     -10    7.98       0    7.98       0    5.68       0    5.38     5.8    5.38
     5.8    5.68     5.8    7.98    15.8   15.98
#Mann= 3 , 0 , 0
     -10    .033       0       0    .033       0     5.8    .033       0
Levee=-1,0,10,-1,5.8,5.38,,
Bank Sta=0,5.8
XS Rating Curve= 0
Exp/Cntr=.3,.1

Type RM Length L Ch R = 1 ,29      ,50,50,50
#Sta/Elev= 21
   -15.1    5.47    -5.1    5.47    -2.6    7.17       0    7.17       1    6.07
     2.5    6.07     2.5    5.27     3.1    5.27     3.1    6.07     3.4    6.07
     3.4    5.27       4    5.27       4    6.07     4.3    6.07     4.3    5.27
     4.9    5.27     4.9    6.07     6.3    6.07     6.3    7.27       7    7.57
      17    7.57
#Mann= 3 , 0 , 0
   -15.1    .033       0       0    .033       0       7    .033       0
Levee=-1,0,10,-1,7,10,,
Bank Sta=0,7
XS Rating Curve= 0
Exp/Cntr=.3,.1

Type RM Length L Ch R = 1 ,26.048  ,48,48,48
#Sta/Elev= 22
   -14.8    5.22    -4.8    5.22    -3.3    6.42       0    6.42       0    4.72
     1.8    4.72     1.8    3.92     2.6    3.92     2.6    4.72     3.2    4.72
     3.2    3.92       4    3.92       4    4.72       6    4.72       6    6.02
     6.2    6.02     6.2    5.62      10    5.62    10.8    6.62    18.8    6.62
    23.8    6.92    28.8    7.22
#Mann= 3 , 0 , 0
   -14.8    .033       0       0    .033       0    10.8    .033       0
Levee=-1,0,10,-1,10.8,10,,
Bank Sta=0,10.8
XS Rating Curve= 0
Exp/Cntr=.3,.1

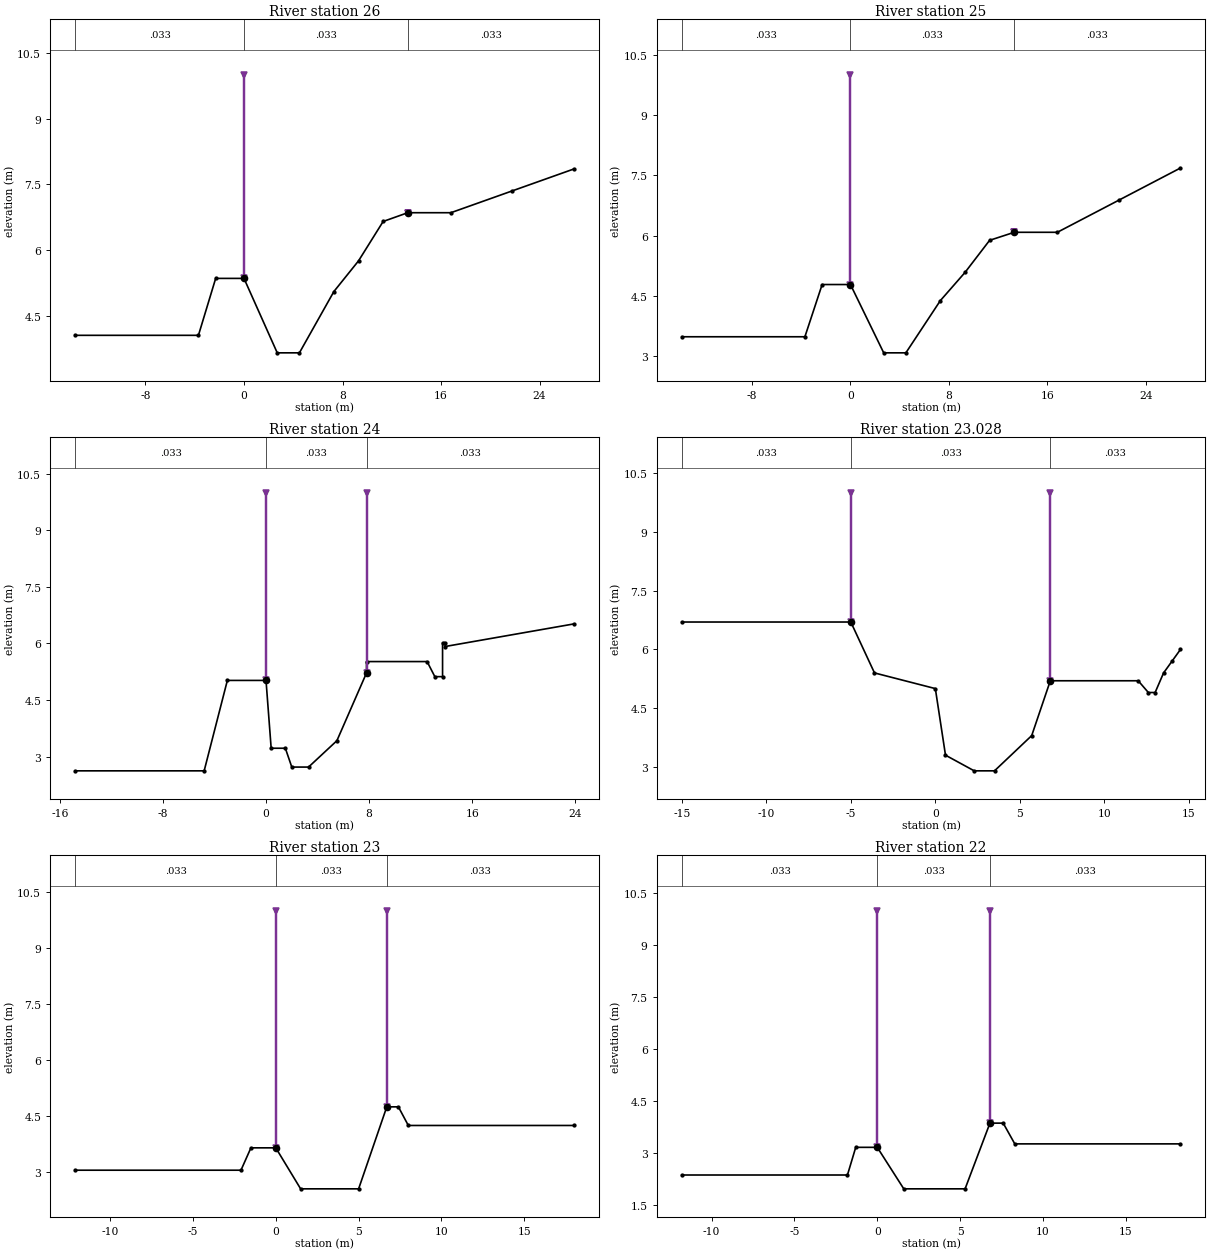
Type RM Length L Ch R = 1 ,26      ,50,50,50
#Sta/Elev= 13
   -13.7    4.05    -3.7    4.05    -2.3    5.35       0    5.35     2.7    3.65
     4.5    3.65     7.3    5.05     9.3    5.75    11.3    6.65    13.3    6.85
    16.8    6.85    21.8    7.35    26.8    7.85
#Mann= 3 , 0 , 0
   -13.7    .033       0       0    .033       0    13.3    .033       0
Levee=-1,0,10,-1,13.3,6.85,,
Bank Sta=0,13.3
XS Rating Curve= 0
Exp/Cntr=.3,.1

Type RM Length L Ch R = 1 ,25      ,50,50,50
#Sta/Elev= 13
   -13.7    3.48    -3.7    3.48    -2.3    4.78       0    4.78     2.7    3.08
     4.5    3.08     7.3    4.38     9.3    5.08    11.3    5.88    13.3    6.08
    16.8    6.08    21.8    6.88    26.8    7.68
#Mann= 3 , 0 , 0
   -13.7    .033       0       0    .033       0    13.3    .033       0
Levee=-1,0,10,-1,13.3,6.08,,
Bank Sta=0,13.3
XS Rating Curve= 0
Exp/Cntr=.3,.1

Type RM Length L Ch R = 1 ,24      ,22,22,22
#Sta/Elev= 18
   -14.8    2.62    -4.8    2.62      -3    5.02       0    5.02      .4    3.22
     1.5    3.22       2    2.72     3.3    2.72     5.5    3.42     7.8    5.22
     7.8    5.52    12.5    5.52    13.1    5.12    13.7    5.12    13.7    6.02
    13.9    6.02    13.9    5.92    23.9    6.52
#Mann= 3 , 0 , 0
   -14.8    .033       0       0    .033       0     7.8    .033       0
Levee=-1,0,10,-1,7.8,10,,
Bank Sta=0,7.8
XS Rating Curve= 0
Exp/Cntr=.3,.1

Type RM Length L Ch R = 1 ,23.028  ,28,28,28
#Sta/Elev= 15
     -15     6.7      -5     6.7    -3.6     5.4       0       5      .6     3.3
     2.3     2.9     3.5     2.9     5.7     3.8     6.8     5.2      12     5.2
    12.6     4.9      13     4.9    13.5     5.4      14     5.7    14.5       6
#Mann= 3 , 0 , 0
     -15    .033       0      -5    .033       0     6.8    .033       0
Levee=-1,-5,10,-1,6.8,10,,
Bank Sta=-5,6.8
XS Rating Curve= 0
Exp/Cntr=.3,.1

Type RM Length L Ch R = 1 ,23      ,50,50,50
#Sta/Elev= 10
   -12.1    3.04    -2.1    3.04    -1.5    3.64       0    3.64     1.5    2.54
       5    2.54     6.7    4.74     7.4    4.74       8    4.24      18    4.24
#Mann= 3 , 0 , 0
   -12.1    .033       0       0    .033       0     6.7    .033       0
Levee=-1,0,10,-1,6.7,10,,
Bank Sta=0,6.7
XS Rating Curve= 0
Exp/Cntr=.3,.1

Type RM Length L Ch R = 1 ,22      ,314,314,314
#Sta/Elev= 10
   -11.8    2.36    -1.8    2.36    -1.3    3.16       0    3.16     1.6    1.96
     5.3    1.96     6.8    3.86     7.6    3.86     8.3    3.26    18.3    3.26
#Mann= 3 , 0 , 0
   -11.8    .033       0       0    .033       0     6.8    .033       0
Levee=-1,0,10,-1,6.8,10,,
Bank Sta=0,6.8
XS Rating Curve= 0
Exp/Cntr=.3,.1

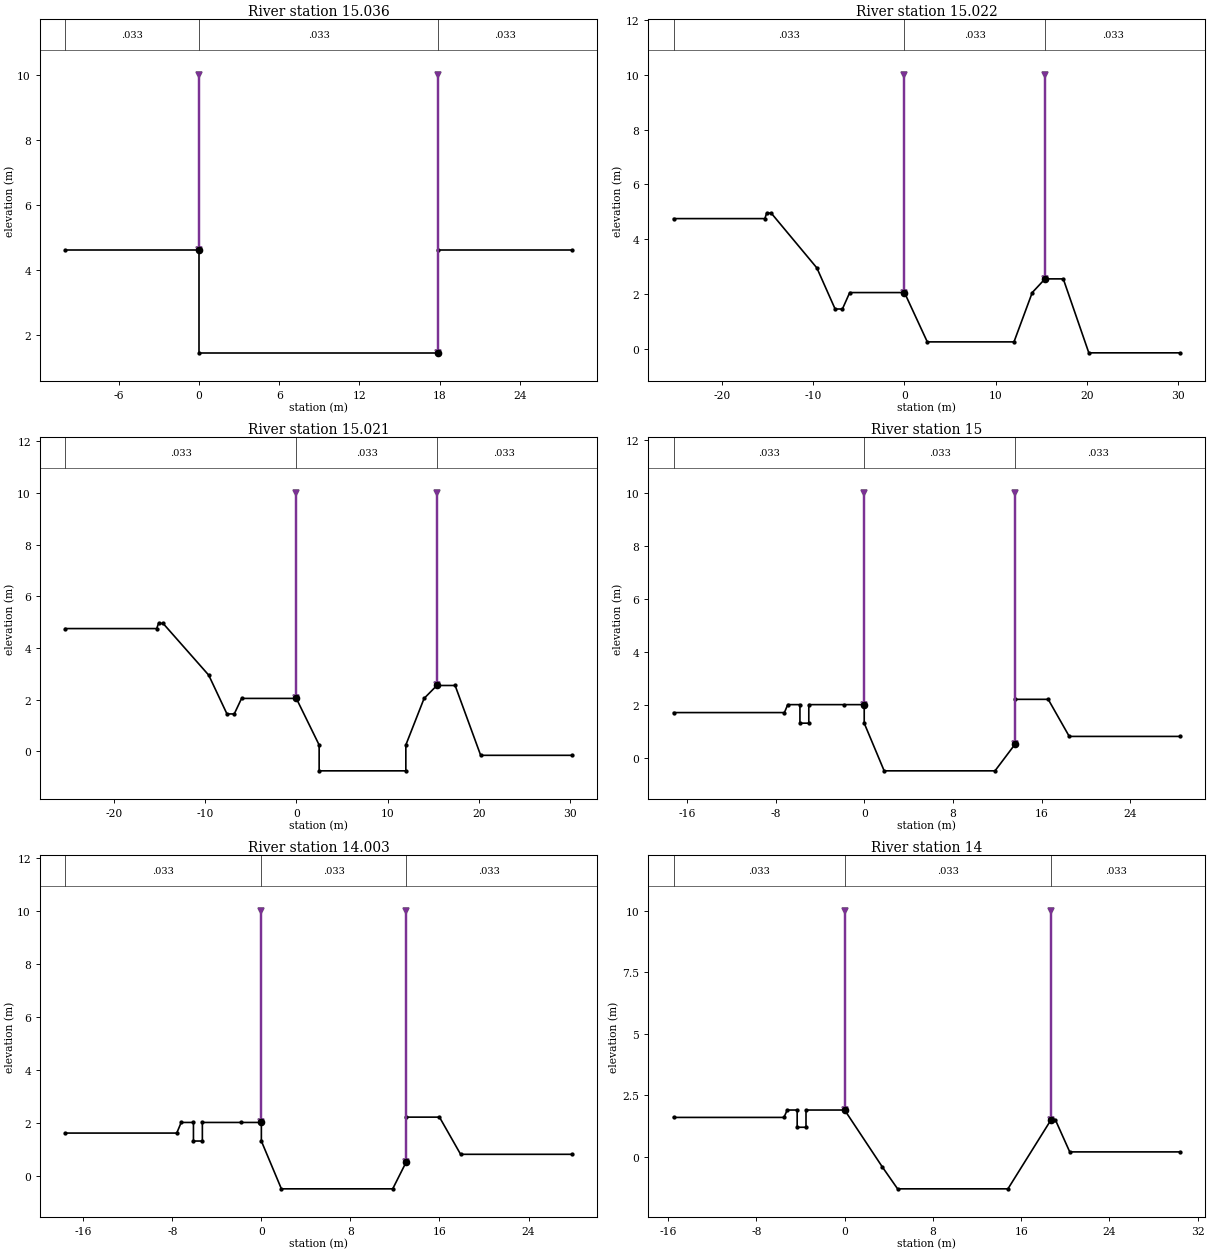
Type RM Length L Ch R = 1 ,15.036  ,14,14,14
#Sta/Elev= 6
     -10    4.61       0    4.61       0    1.45    17.9    1.45    17.9    4.61
    27.9    4.61
#Mann= 3 , 0 , 0
     -10    .033       0       0    .033       0    17.9    .033       0
Levee=-1,0,10,-1,17.9,10,,
Bank Sta=0,17.9
XS Rating Curve= 0
Exp/Cntr=.3,.1

Type RM Length L Ch R = 1 ,15.022  ,1,1,1
#Sta/Elev= 16
   -25.3    4.75   -15.3    4.75   -15.1    4.95   -14.6    4.95    -9.6    2.95
    -7.6    1.45    -6.8    1.45      -6    2.05       0    2.05     2.5     .25
      12     .25      14    2.05    15.4    2.55    17.4    2.55    20.2    -.15
    30.2    -.15
#Mann= 3 , 0 , 0
   -25.3    .033       0       0    .033       0    15.4    .033       0
Levee=-1,0,10,-1,15.4,10,,
Bank Sta=0,15.4
XS Rating Curve= 0
Exp/Cntr=.3,.1

Type RM Length L Ch R = 1 ,15.021  ,21,21,21
#Sta/Elev= 18
   -25.3    4.75   -15.3    4.75   -15.1    4.95   -14.6    4.95    -9.6    2.95
    -7.6    1.45    -6.8    1.45      -6    2.05       0    2.05     2.5     .25
     2.5    -.75      12    -.75      12     .25      14    2.05    15.4    2.55
    17.4    2.55    20.2    -.15    30.2    -.15
#Mann= 3 , 0 , 0
   -25.3    .033       0       0    .033       0    15.4    .033       0
Levee=-1,0,10,-1,15.4,10,,
Bank Sta=0,15.4
XS Rating Curve= 0
Exp/Cntr=.3,.1

Type RM Length L Ch R = 1 ,15      ,47,47,47
#Sta/Elev= 17
   -17.2     1.7    -7.2     1.7    -6.9       2    -5.8       2    -5.8     1.3
      -5     1.3      -5       2    -1.8       2       0       2       0     1.3
     1.8     -.5    11.8     -.5    13.6      .5    13.6     2.2    16.6     2.2
    18.5      .8    28.5      .8
#Mann= 3 , 0 , 0
   -17.2    .033       0       0    .033       0    13.6    .033       0
Levee=-1,0,10,-1,13.6,10,,
Bank Sta=0,13.6
XS Rating Curve= 0
Exp/Cntr=.3,.1

Type RM Length L Ch R = 1 ,14.003  ,3,3,3
#Sta/Elev= 17
   -17.6    1.63    -7.6    1.63    -7.2    2.03    -6.1    2.03    -6.1    1.33
    -5.3    1.33    -5.3    2.03    -1.8    2.03       0    2.03       0    1.33
     1.8    -.47    11.8    -.47      13     .53      13    2.23      16    2.23
    17.9     .83    27.9     .83
#Mann= 3 , 0 , 0
   -17.6    .033       0       0    .033       0      13    .033       0
Levee=-1,0,10,-1,13,10,,
Bank Sta=0,13
XS Rating Curve= 0
Exp/Cntr=.3,.1

Type RM Length L Ch R = 1 ,14      ,50,50,50
#Sta/Elev= 15
   -15.5    1.61    -5.5    1.61    -5.2    1.91    -4.3    1.91    -4.3    1.21
    -3.5    1.21    -3.5    1.91       0    1.91     3.4    -.39     4.8   -1.29
    14.8   -1.29    18.7    1.51    19.1    1.51    20.4     .21    30.4     .21
#Mann= 3 , 0 , 0
   -15.5    .033       0       0    .033       0    18.7    .033       0
Levee=-1,0,10,-1,18.7,10,,
Bank Sta=0,18.7
XS Rating Curve= 0
Exp/Cntr=.3,.1