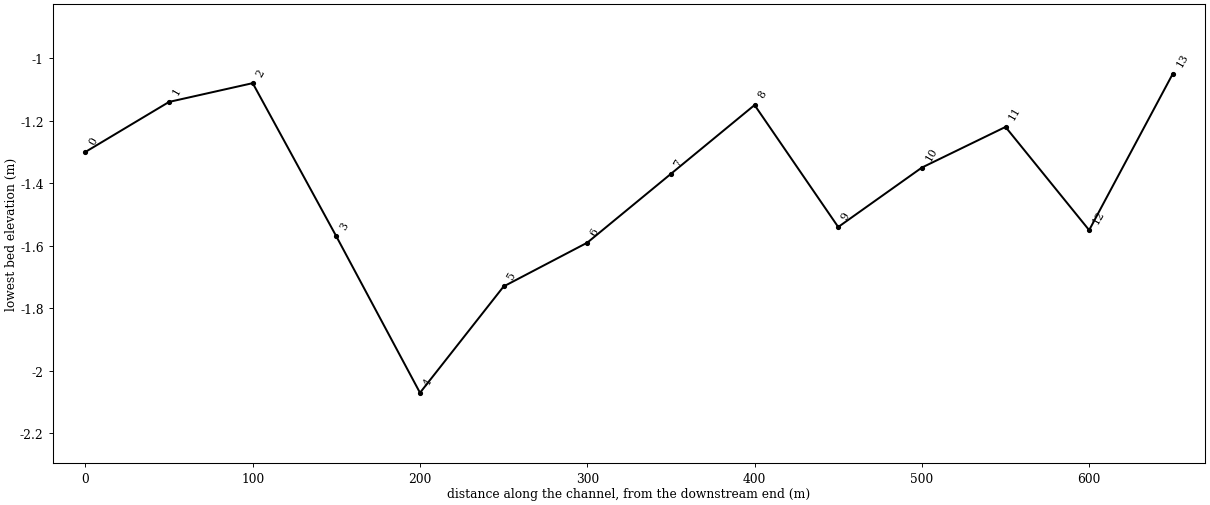
HEC-RAS study JBC.prj: JUNGBU

--- JBC.g01 (geometry) --- (continued)

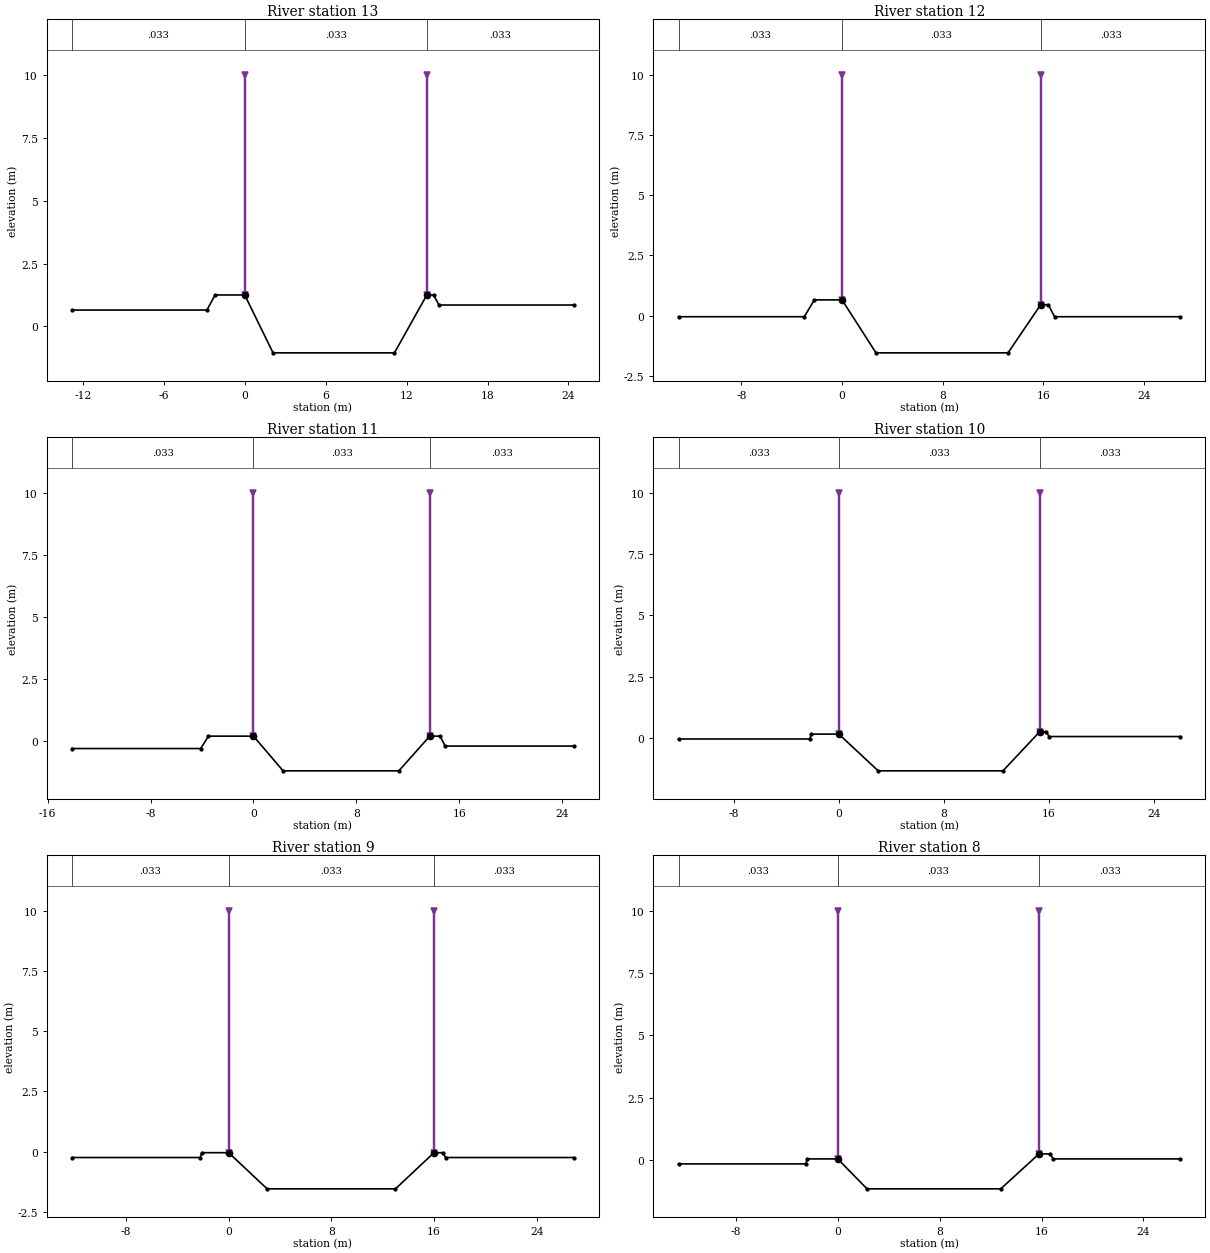
Type RM Length L Ch R = 1 ,13      ,50,50,50
#Sta/Elev= 10
   -12.8     .65    -2.8     .65    -2.2    1.25       0    1.25     2.1   -1.05
    11.1   -1.05    13.5    1.25      14    1.25    14.4     .85    24.4     .85
#Mann= 3 , 0 , 0
   -12.8    .033       0       0    .033       0    13.5    .033       0
Levee=-1,0,10,-1,13.5,10,,
Bank Sta=0,13.5
XS Rating Curve= 0
Exp/Cntr=.3,.1

Type RM Length L Ch R = 1 ,12      ,50,50,50
#Sta/Elev= 10
     -13    -.05      -3    -.05    -2.2     .65       0     .65     2.7   -1.55
    13.2   -1.55    15.8     .45    16.4     .45    16.9    -.05    26.9    -.05
#Mann= 3 , 0 , 0
     -13    .033       0       0    .033       0    15.8    .033       0
Levee=-1,0,10,-1,15.8,10,,
Bank Sta=0,15.8
XS Rating Curve= 0
Exp/Cntr=.3,.1

Type RM Length L Ch R = 1 ,11      ,50,50,50
#Sta/Elev= 10
   -14.1    -.32    -4.1    -.32    -3.5     .18       0     .18     2.3   -1.22
    11.3   -1.22    13.7     .18    14.5     .18    14.9    -.22    24.9    -.22
#Mann= 3 , 0 , 0
   -14.1    .033       0       0    .033       0    13.7    .033       0
Levee=-1,0,10,-1,13.7,10,,
Bank Sta=0,13.7
XS Rating Curve= 0
Exp/Cntr=.3,.1

Type RM Length L Ch R = 1 ,10      ,50,50,50
#Sta/Elev= 10
   -12.2    -.05    -2.2    -.05    -2.1     .15       0     .15       3   -1.35
    12.5   -1.35    15.3     .25    15.8     .25      16     .05      26     .05
#Mann= 3 , 0 , 0
   -12.2    .033       0       0    .033       0    15.3    .033       0
Levee=-1,0,10,-1,15.3,10,,
Bank Sta=0,15.3
XS Rating Curve= 0
Exp/Cntr=.3,.1

Type RM Length L Ch R = 1 ,9       ,50,50,50
#Sta/Elev= 10
   -12.2    -.24    -2.2    -.24    -2.1    -.04       0    -.04       3   -1.54
      13   -1.54      16    -.04    16.7    -.04    16.9    -.24    26.9    -.24
#Mann= 3 , 0 , 0
   -12.2    .033       0       0    .033       0      16    .033       0
Levee=-1,0,10,-1,16,10,,
Bank Sta=0,16
XS Rating Curve= 0
Exp/Cntr=.3,.1

Type RM Length L Ch R = 1 ,8       ,50,50,50
#Sta/Elev= 10
   -12.5    -.15    -2.5    -.15    -2.4     .05       0     .05     2.3   -1.15
    12.8   -1.15    15.8     .25    16.7     .25    16.9     .05    26.9     .05
#Mann= 3 , 0 , 0
   -12.5    .033       0       0    .033       0    15.8    .033       0
Levee=-1,0,10,-1,15.8,10,,
Bank Sta=0,15.8
XS Rating Curve= 0
Exp/Cntr=.3,.1

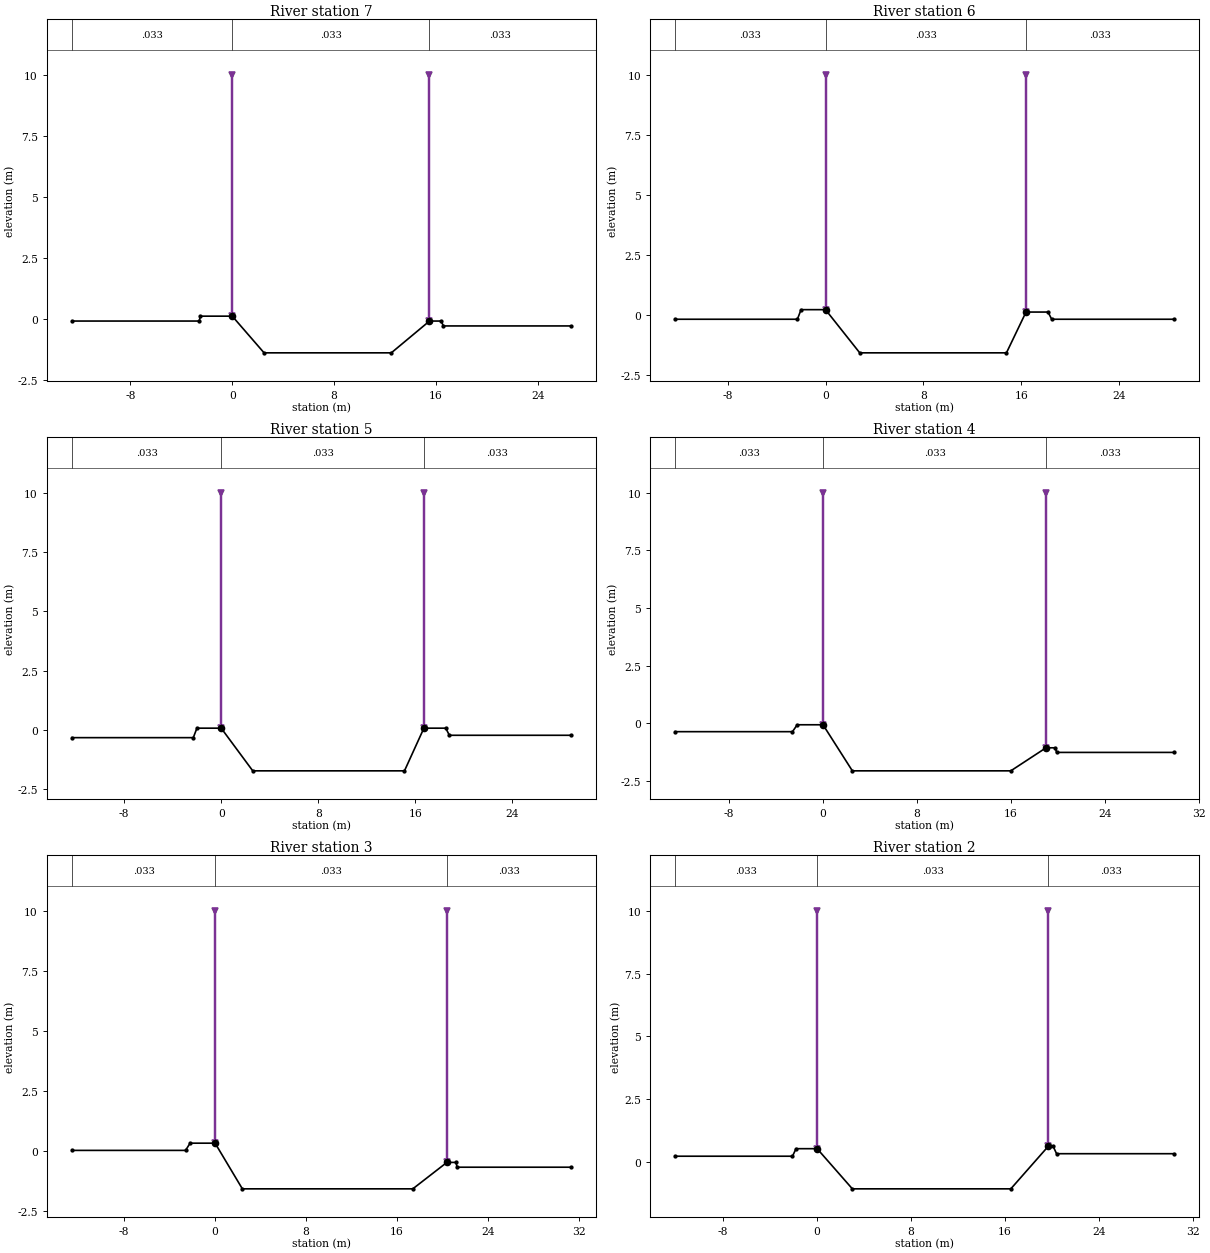
Type RM Length L Ch R = 1 ,7       ,50,50,50
#Sta/Elev= 10
   -12.6    -.07    -2.6    -.07    -2.5     .13       0     .13     2.5   -1.37
    12.5   -1.37    15.5    -.07    16.4    -.07    16.6    -.27    26.6    -.27
#Mann= 3 , 0 , 0
   -12.6    .033       0       0    .033       0    15.5    .033       0
Levee=-1,0,10,-1,15.5,10,,
Bank Sta=0,15.5
XS Rating Curve= 0
Exp/Cntr=.3,.1

Type RM Length L Ch R = 1 ,6       ,50,50,50
#Sta/Elev= 10
   -12.3    -.19    -2.3    -.19      -2     .21       0     .21     2.8   -1.59
    14.8   -1.59    16.4     .11    18.2     .11    18.5    -.19    28.5    -.19
#Mann= 3 , 0 , 0
   -12.3    .033       0       0    .033       0    16.4    .033       0
Levee=-1,0,10,-1,16.4,10,,
Bank Sta=0,16.4
XS Rating Curve= 0
Exp/Cntr=.3,.1

Type RM Length L Ch R = 1 ,5       ,50,50,50
#Sta/Elev= 10
   -12.3    -.33    -2.3    -.33      -2     .07       0     .07     2.6   -1.73
    15.1   -1.73    16.7     .07    18.5     .07    18.8    -.23    28.8    -.23
#Mann= 3 , 0 , 0
   -12.3    .033       0       0    .033       0    16.7    .033       0
Levee=-1,0,10,-1,16.7,10,,
Bank Sta=0,16.7
XS Rating Curve= 0
Exp/Cntr=.3,.1

Type RM Length L Ch R = 1 ,4       ,50,50,50
#Sta/Elev= 10
   -12.6    -.37    -2.6    -.37    -2.2    -.07       0    -.07     2.5   -2.07
      16   -2.07      19   -1.07    19.8   -1.07    19.9   -1.27    29.9   -1.27
#Mann= 3 , 0 , 0
   -12.6    .033       0       0    .033       0      19    .033       0
Levee=-1,0,10,-1,19,10,,
Bank Sta=0,19
XS Rating Curve= 0
Exp/Cntr=.3,.1

Type RM Length L Ch R = 1 ,3       ,50,50,50
#Sta/Elev= 10
   -12.6     .03    -2.6     .03    -2.2     .33       0     .33     2.4   -1.57
    17.4   -1.57    20.4    -.47    21.2    -.47    21.3    -.67    31.3    -.67
#Mann= 3 , 0 , 0
   -12.6    .033       0       0    .033       0    20.4    .033       0
Levee=-1,0,10,-1,20.4,10,,
Bank Sta=0,20.4
XS Rating Curve= 0
Exp/Cntr=.3,.1

Type RM Length L Ch R = 1 ,2       ,50,50,50
#Sta/Elev= 10
   -12.1     .22    -2.1     .22    -1.8     .52       0     .52       3   -1.08
    16.5   -1.08    19.7     .62    20.1     .62    20.4     .32    30.4     .32
#Mann= 3 , 0 , 0
   -12.1    .033       0       0    .033       0    19.7    .033       0
Levee=-1,0,10,-1,19.7,10,,
Bank Sta=0,19.7
XS Rating Curve= 0
Exp/Cntr=.3,.1

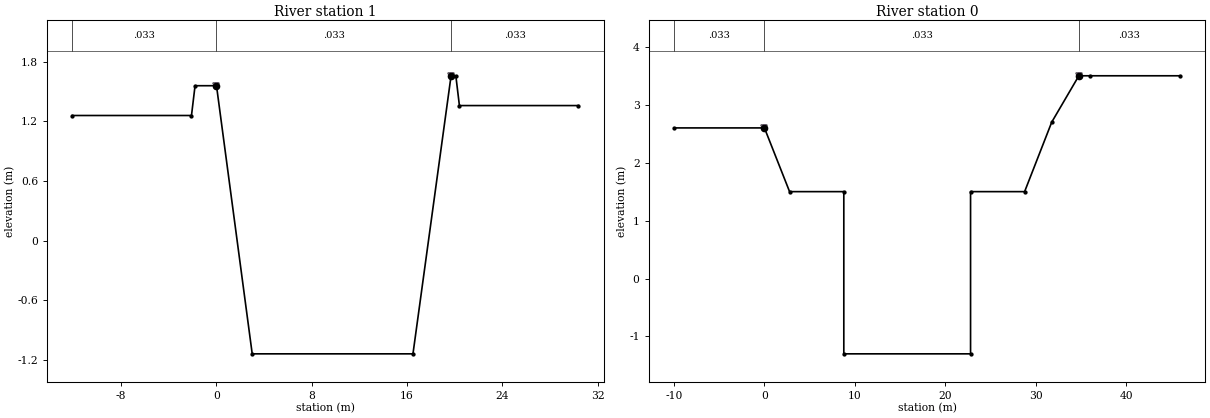
Type RM Length L Ch R = 1 ,1       ,50,50,50
#Sta/Elev= 10
   -12.1    1.26    -2.1    1.26    -1.8    1.56       0    1.56       3   -1.14
    16.5   -1.14    19.7    1.66    20.1    1.66    20.4    1.36    30.4    1.36
#Mann= 3 , 0 , 0
   -12.1    .033       0       0    .033       0    19.7    .033       0
Levee=-1,0,1.56,-1,19.7,1.66,,
Bank Sta=0,19.7
XS Rating Curve= 0
Exp/Cntr=.3,.1

Type RM Length L Ch R = 1 ,0       ,0,0,0
#Sta/Elev= 12
     -10     2.6       0     2.6    2.78     1.5    8.78     1.5    8.78    -1.3
    22.8    -1.3    22.8     1.5   28.78     1.5   31.78     2.7   34.78     3.5
   35.98     3.5   45.98     3.5
#Mann= 3 , 0 , 0
     -10    .033       0       0    .033       0   34.78    .033       0
Levee=-1,0,2.6,-1,34.78,3.5,,
#XS Ineff= 2 , 0
       0       0     2.6   34.78       0     3.5
Permanent Ineff=
       F       F
Bank Sta=0,34.78
XS Rating Curve= 0
Exp/Cntr=.3,.1

Chan Stop Cuts=-1