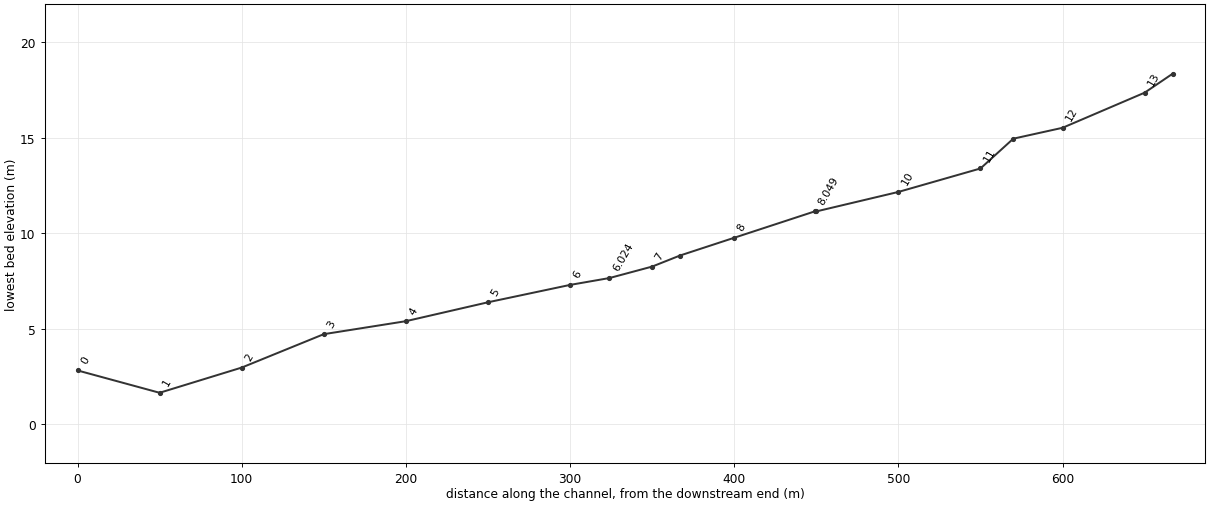
--- SSC.prj (project) ---

Proj Title=SUKSO
Current Plan=p01
Default Exp/Contr=.3,.1
SI Units
Geom File=g01
Flow File=f01
Plan File=p01
Y Axis Title=Elevation
X Axis Title(PF)=Main Channel Distance
X Axis Title(XS)=Station
BEGIN DESCRIPTION:
           BACK WATER COMPUTATION
      APPLICATION OF HEC-2 BY Samju Construction Engineering
      SUKSO-STREEM : 30 YR
END DESCRIPTION:
DSS Export Rating Curves= 0
DSS Export Rating Curve Sorted= 0
DSS Export Volume Flow Curves= 0
DXF OffsetX= 0
DXF OffsetY= 0
DXF ScaleX= 1
DXF ScaleY= 10

--- SSC.p01 (plan) ---

Plan Title=Imported Plan 01
Version=Version 3.0.1  Mar 2001
Short Identifier=Imported Pla
Geom File=g01
Flow File=f01
Subcritical Flow
K Sum by GR= 0
Std Step Tol= 0.003
Critical Tol= 0.003
Num of Std Step Trials= 20
Max Error Tol= 0.1
Flow Tol Ratio= 0.001
Split Flow NTrial= 30
Split Flow Tol= 0.02
Split Flow Ratio= 0.02
Log Output Level= 0
Friction Slope Method= 1
Unsteady Friction Slope Method= 2
Parabolic Critical Depth
Global Vel Dist= 0 , 0 , 0
Global Log Level= 0
CheckData=True
Encroach Param=-1 ,0,0, 0
Computation Interval=1HOUR
Output Interval=1HOUR
Run HTab= 0
Run UNet= 0
Run PostProcess= 0
UNET Theta= 1
UNET ZTol= 0.02
UNET ZSATol= 0.1
UNET MxIter= 20
UNET MaxInSteps= 20
UNET DtIC= 0
UNET DtMin= 0
UNET MaxCRTS= 20
UNET WFStab= 2
UNET SFStab= 1
UNET WFX= 1
UNET SFX= 1
UNET Convert EG Bridges=-1
UNET Use Existing IB Tables=-1
Instantaneous Interval=1HOUR
Write IC File= 0
Write Velocity= 0
Write Detailed= 0

--- SSC.f01 (steady flow) ---

Flow Title=Imported Flow 01
Version=Version 3.0.1  Mar 2001
Number of Profiles= 5
Profile Names=10YR,20YR,30YR,50YR,80YR
River Rch & RM=RIVER-1,Reach-1         ,13.017
    8.52    9.39     9.9   10.54   11.12
River Rch & RM=SUKSO,SUKSO           ,13.017
    8.52    9.39     9.9   10.54   11.12
Boundary for River Rch & Prof#=SUKSO,SUKSO           , 1
Up Type= 0
Dn Type= 3
Dn Slope=.024
Boundary for River Rch & Prof#=SUKSO,SUKSO           , 2
Up Type= 0
Dn Type= 3
Dn Slope=.024
Boundary for River Rch & Prof#=SUKSO,SUKSO           , 3
Up Type= 0
Dn Type= 3
Dn Slope=.024
Boundary for River Rch & Prof#=SUKSO,SUKSO           , 4
Up Type= 0
Dn Type= 3
Dn Slope=.024
Boundary for River Rch & Prof#=SUKSO,SUKSO           , 5
Up Type= 0
Dn Type= 3
Dn Slope=.024
DSS Import GetInterval= 0
DSS Import GetPeak= 0
DSS Import FillOption= 0

--- SSC.g01 (geometry) ---

Geom Title=Imported Geom 01
Version=Version 3.0.1  Mar 2001

River Reach=SUKSO           ,SUKSO
Reach XY= 2
              .5             .95              .5             .05

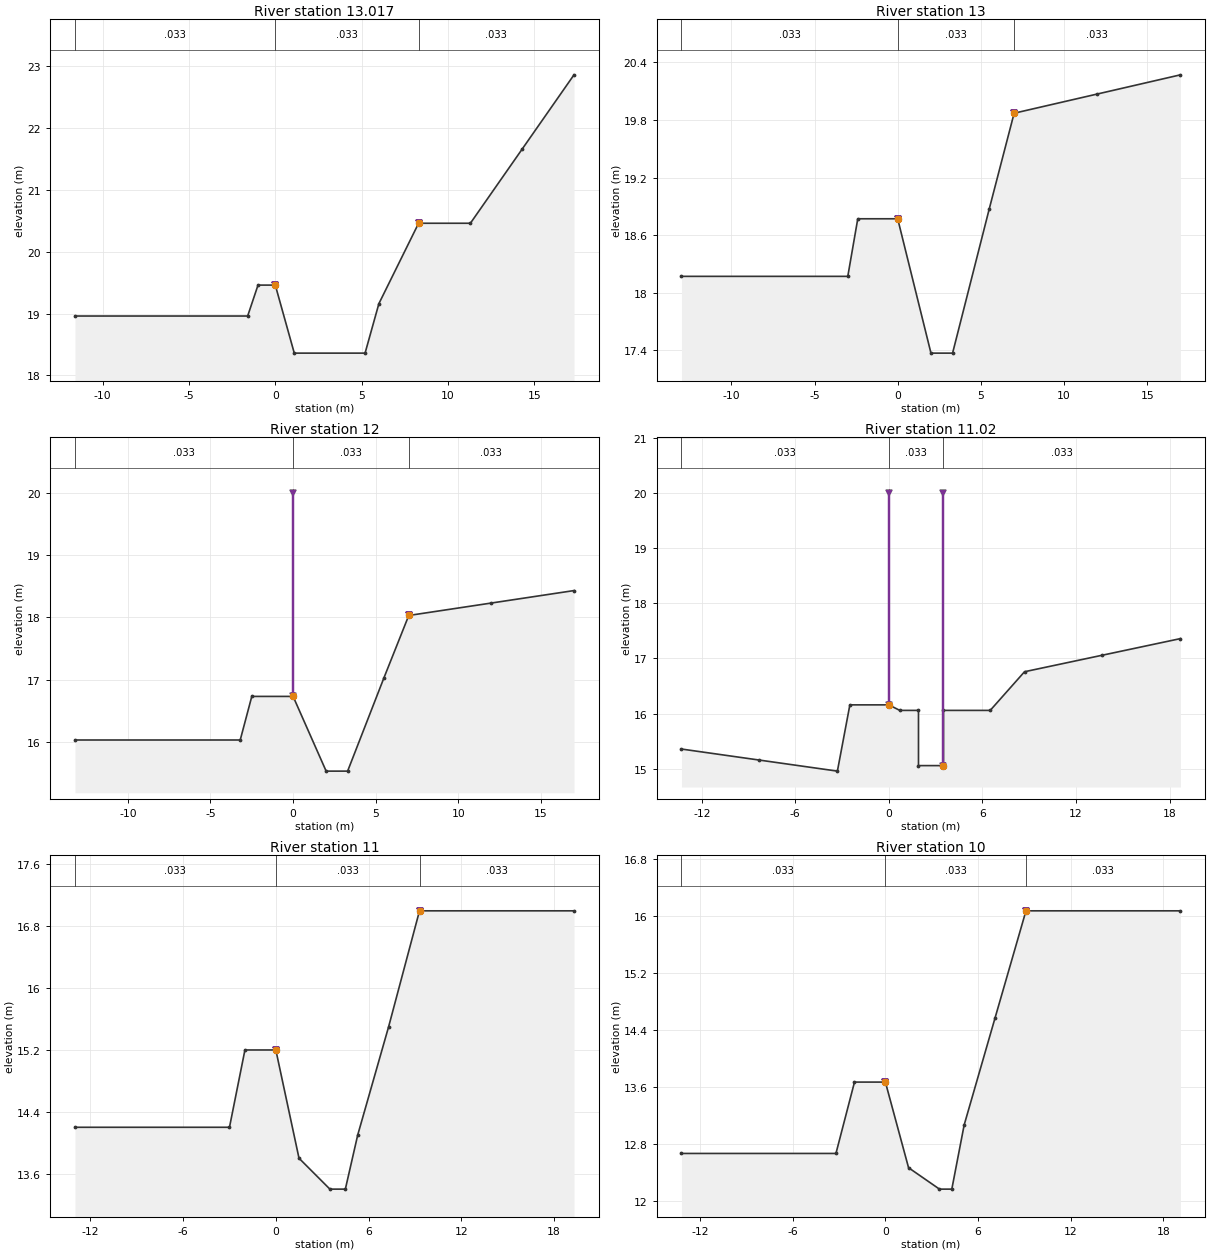
Type RM Length L Ch R = 1 ,13.017  ,17,17,17
#Sta/Elev= 11
   -11.6   18.96    -1.6   18.96      -1   19.46       0   19.46     1.1   18.36
     5.2   18.36       6   19.16     8.3   20.46    11.3   20.46    14.3   21.66
    17.3   22.86
#Mann= 3 , 0 , 0
   -11.6    .033       0       0    .033       0     8.3    .033       0
Levee=-1,0,19.46,-1,8.3,20.46,,
Bank Sta=0,8.3
XS Rating Curve= 0
Exp/Cntr=.3,.1

Type RM Length L Ch R = 1 ,13      ,50,50,50
#Sta/Elev= 10
     -13   18.17      -3   18.17    -2.4   18.77       0   18.77       2   17.37
     3.3   17.37     5.5   18.87       7   19.87      12   20.07      17   20.27
#Mann= 3 , 0 , 0
     -13    .033       0       0    .033       0       7    .033       0
Levee=-1,0,18.77,-1,7,19.87,,
Bank Sta=0,7
XS Rating Curve= 0
Exp/Cntr=.3,.1

Type RM Length L Ch R = 1 ,12      ,30,30,30
#Sta/Elev= 10
   -13.2   16.03    -3.2   16.03    -2.5   16.73       0   16.73       2   15.53
     3.3   15.53     5.5   17.03       7   18.03      12   18.23      17   18.43
#Mann= 3 , 0 , 0
   -13.2    .033       0       0    .033       0       7    .033       0
Levee=-1,0,20,-1,7,18.03,,
Bank Sta=0,7
XS Rating Curve= 0
Exp/Cntr=.3,.1

Type RM Length L Ch R = 1 ,11.02   ,20,20,20
#Sta/Elev= 14
   -13.3   15.36    -8.3   15.16    -3.3   14.96    -2.5   16.16       0   16.16
      .7   16.06     1.9   16.06     1.9   15.06     3.5   15.06     3.5   16.06
     6.5   16.06     8.7   16.76    13.7   17.06    18.7   17.36
#Mann= 3 , 0 , 0
   -13.3    .033       0       0    .033       0     3.5    .033       0
Levee=-1,0,20,-1,3.5,20,,
Bank Sta=0,3.5
XS Rating Curve= 0
Exp/Cntr=.3,.1

Type RM Length L Ch R = 1 ,11      ,50,50,50
#Sta/Elev= 11
     -13    14.2      -3    14.2      -2    15.2       0    15.2     1.5    13.8
     3.5    13.4     4.5    13.4     5.3    14.1     7.3    15.5     9.3      17
    19.3      17
#Mann= 3 , 0 , 0
     -13    .033       0       0    .033       0     9.3    .033       0
Levee=-1,0,15.2,-1,9.3,17,,
Bank Sta=0,9.3
XS Rating Curve= 0
Exp/Cntr=.3,.1

Type RM Length L Ch R = 1 ,10      ,50,50,50
#Sta/Elev= 11
   -13.2   12.67    -3.2   12.67      -2   13.67       0   13.67     1.5   12.47
     3.5   12.17     4.3   12.17     5.1   13.07     7.1   14.57     9.1   16.07
    19.1   16.07
#Mann= 3 , 0 , 0
   -13.2    .033       0       0    .033       0     9.1    .033       0
Levee=-1,0,13.67,-1,9.1,16.07,,
Bank Sta=0,9.1
XS Rating Curve= 0
Exp/Cntr=.3,.1

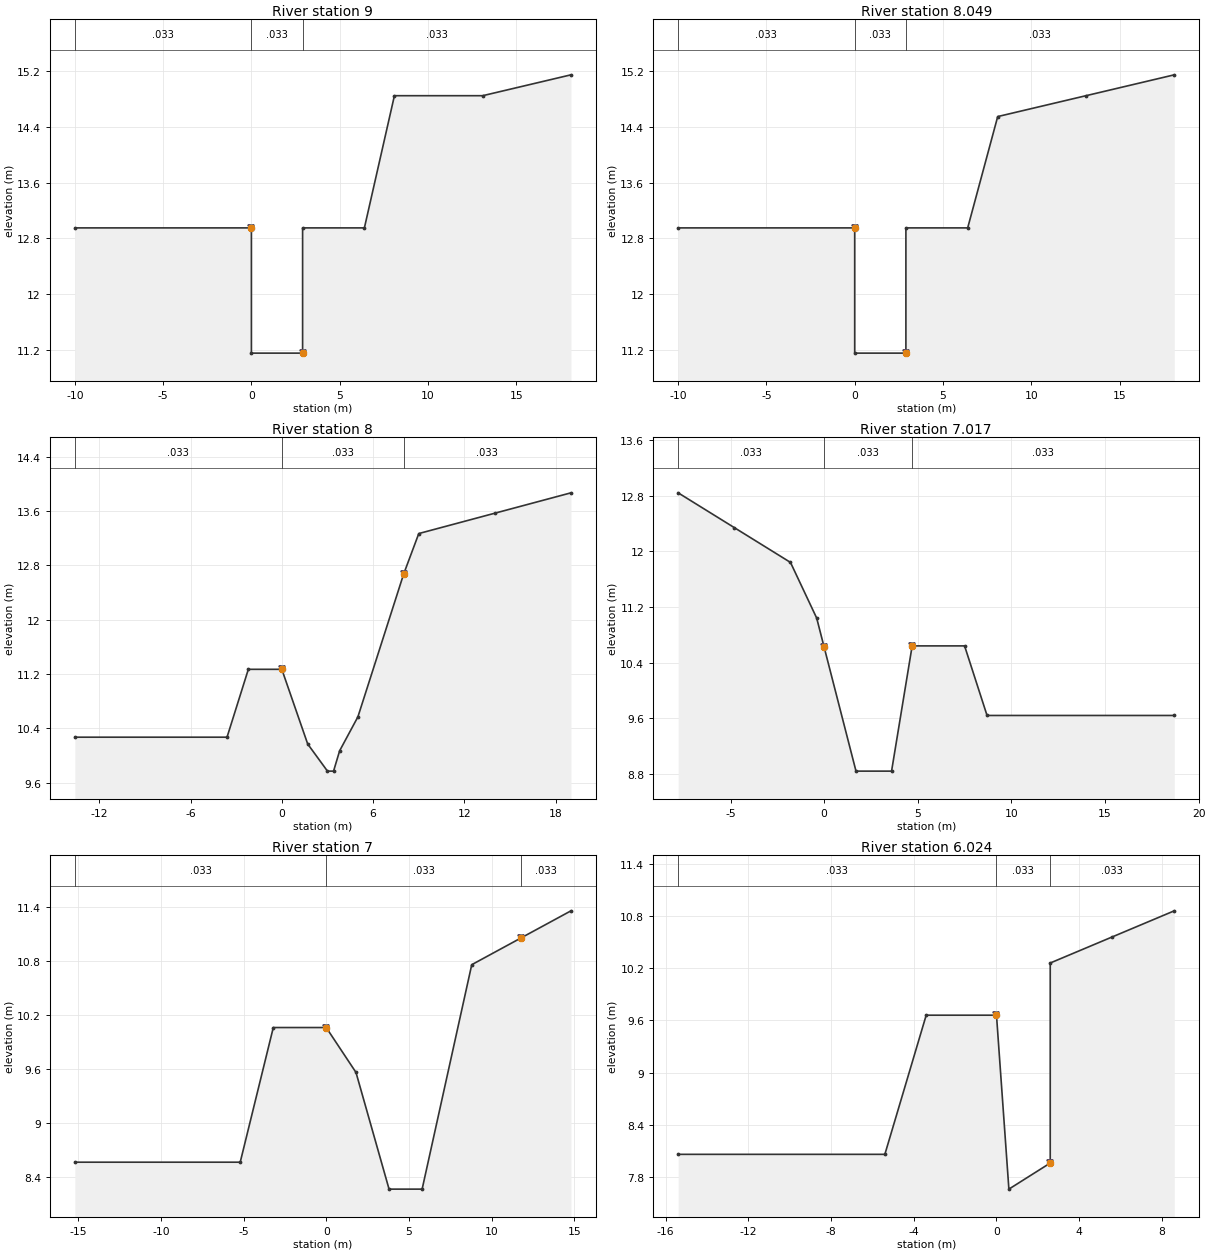
Type RM Length L Ch R = 1 ,9       ,1,1,1
#Sta/Elev= 9
     -10   12.95       0   12.95       0   11.15     2.9   11.15     2.9   12.95
     6.4   12.95     8.1   14.85    13.1   14.85    18.1   15.15
#Mann= 3 , 0 , 0
     -10    .033       0       0    .033       0     2.9    .033       0
Levee=-1,0,12.95,-1,2.9,11.15,,
Bank Sta=0,2.9
XS Rating Curve= 0
Exp/Cntr=.3,.1

Type RM Length L Ch R = 1 ,8.049   ,49,49,49
#Sta/Elev= 9
     -10   12.95       0   12.95       0   11.15     2.9   11.15     2.9   12.95
     6.4   12.95     8.1   14.55    13.1   14.85    18.1   15.15
#Mann= 3 , 0 , 0
     -10    .033       0       0    .033       0     2.9    .033       0
Levee=-1,0,12.95,-1,2.9,11.15,,
Bank Sta=0,2.9
XS Rating Curve= 0
Exp/Cntr=.3,.1

Type RM Length L Ch R = 1 ,8       ,33,33,33
#Sta/Elev= 13
   -13.6   10.27    -3.6   10.27    -2.2   11.27       0   11.27     1.7   10.17
       3    9.77     3.4    9.77     3.8   10.07       5   10.57       8   12.67
       9   13.27      14   13.57      19   13.87
#Mann= 3 , 0 , 0
   -13.6    .033       0       0    .033       0       8    .033       0
Levee=-1,0,11.27,-1,8,12.67,,
Bank Sta=0,8
XS Rating Curve= 0
Exp/Cntr=.3,.1

Type RM Length L Ch R = 1 ,7.017   ,17,17,17
#Sta/Elev= 11
    -7.8   12.84    -4.8   12.34    -1.8   11.84     -.4   11.04       0   10.62
     1.7    8.84     3.6    8.84     4.7   10.64     7.5   10.64     8.7    9.64
    18.7    9.64
#Mann= 3 , 0 , 0
    -7.8    .033       0       0    .033       0     4.7    .033       0
Levee=-1,0,10.62,-1,4.7,10.64,,
Bank Sta=0,4.7
XS Rating Curve= 0
Exp/Cntr=.3,.1

Type RM Length L Ch R = 1 ,7       ,26,26,26
#Sta/Elev= 10
   -15.2    8.56    -5.2    8.56    -3.2   10.06       0   10.06     1.8    9.56
     3.8    8.26     5.8    8.26     8.8   10.76    11.8   11.06    14.8   11.36
#Mann= 3 , 0 , 0
   -15.2    .033       0       0    .033       0    11.8    .033       0
Levee=-1,0,10.06,-1,11.8,11.06,,
Bank Sta=0,11.8
XS Rating Curve= 0
Exp/Cntr=.3,.1

Type RM Length L Ch R = 1 ,6.024   ,24,24,24
#Sta/Elev= 9
   -15.4    8.06    -5.4    8.06    -3.4    9.66       0    9.66      .6    7.66
     2.6    7.96     2.6   10.26     5.6   10.56     8.6   10.86
#Mann= 3 , 0 , 0
   -15.4    .033       0       0    .033       0     2.6    .033       0
Levee=-1,0,9.66,-1,2.6,7.96,,
Bank Sta=0,2.6
XS Rating Curve= 0
Exp/Cntr=.3,.1

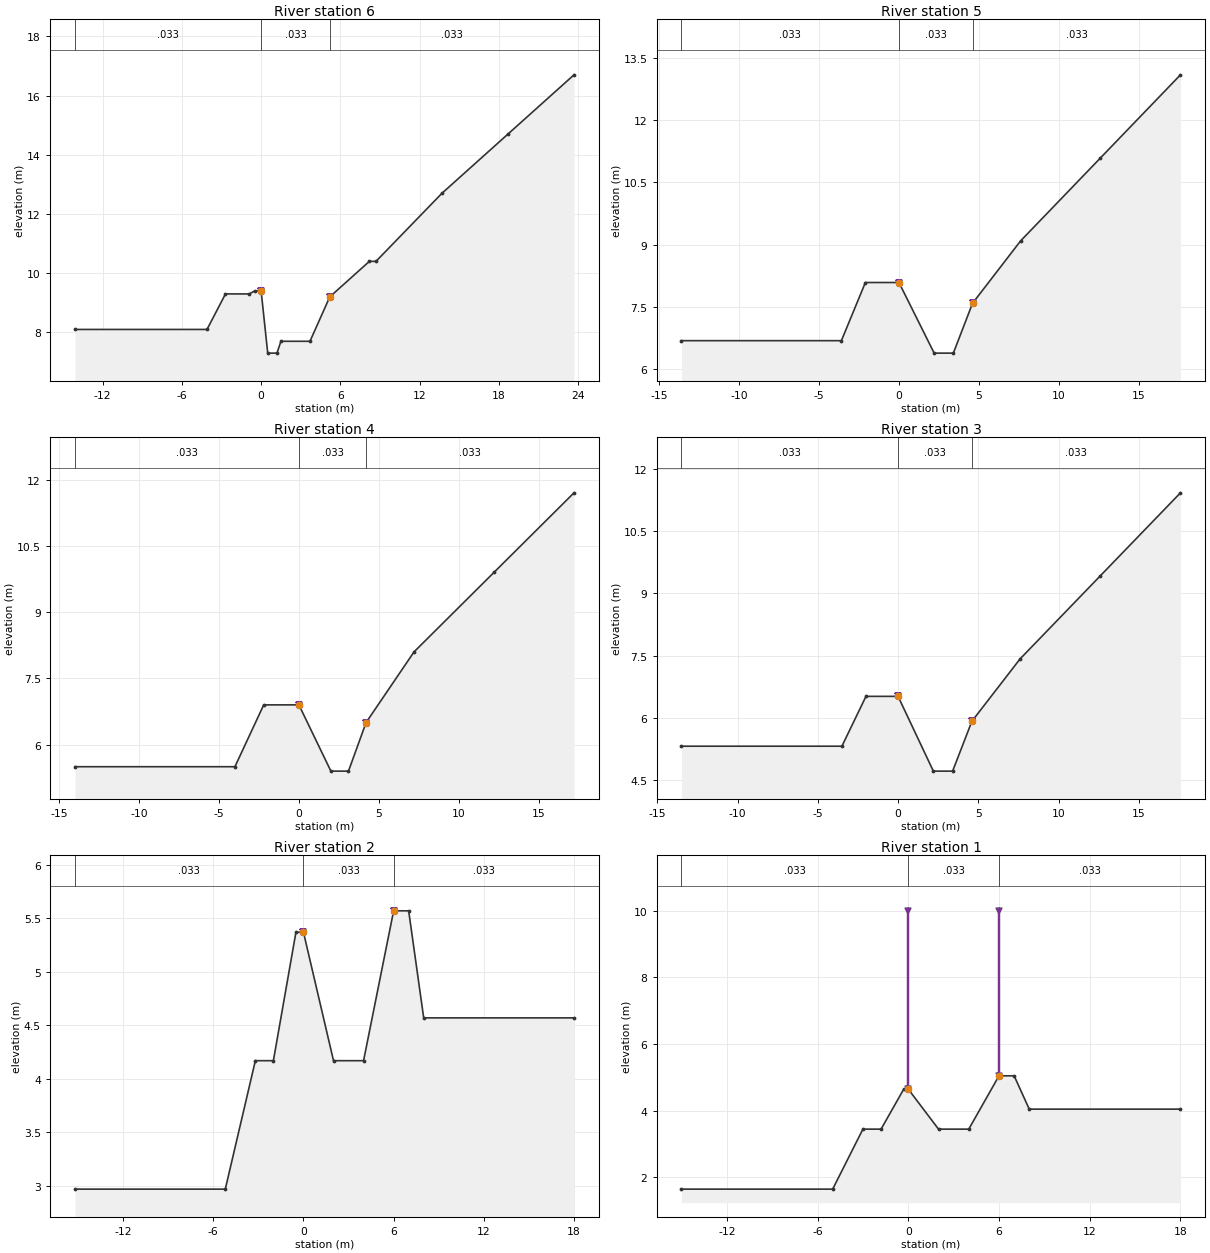
Type RM Length L Ch R = 1 ,6       ,50,50,50
#Sta/Elev= 16
   -14.1     8.1    -4.1     8.1    -2.7     9.3     -.9     9.3     -.5     9.4
       0     9.4      .5     7.3     1.2     7.3     1.5     7.7     3.7     7.7
     5.2     9.2     8.2    10.4     8.7    10.4    13.7    12.7    18.7    14.7
    23.7    16.7
#Mann= 3 , 0 , 0
   -14.1    .033       0       0    .033       0     5.2    .033       0
Levee=-1,0,9.4,-1,5.2,9.2,,
Bank Sta=0,5.2
XS Rating Curve= 0
Exp/Cntr=.3,.1

Type RM Length L Ch R = 1 ,5       ,50,50,50
#Sta/Elev= 10
   -13.6    6.69    -3.6    6.69    -2.1    8.09       0    8.09     2.2    6.39
     3.4    6.39     4.6    7.59     7.6    9.09    12.6   11.09    17.6   13.09
#Mann= 3 , 0 , 0
   -13.6    .033       0       0    .033       0     4.6    .033       0
Levee=-1,0,8.09,-1,4.6,7.59,,
Bank Sta=0,4.6
XS Rating Curve= 0
Exp/Cntr=.3,.1

Type RM Length L Ch R = 1 ,4       ,50,50,50
#Sta/Elev= 10
     -14     5.5      -4     5.5    -2.2     6.9       0     6.9       2     5.4
     3.1     5.4     4.2     6.5     7.2     8.1    12.2     9.9    17.2    11.7
#Mann= 3 , 0 , 0
     -14    .033       0       0    .033       0     4.2    .033       0
Levee=-1,0,6.9,-1,4.2,6.5,,
Bank Sta=0,4.2
XS Rating Curve= 0
Exp/Cntr=.3,.1

Type RM Length L Ch R = 1 ,3       ,50,50,50
#Sta/Elev= 10
   -13.5    5.32    -3.5    5.32      -2    6.52       0    6.52     2.2    4.72
     3.4    4.72     4.6    5.92     7.6    7.42    12.6    9.42    17.6   11.42
#Mann= 3 , 0 , 0
   -13.5    .033       0       0    .033       0     4.6    .033       0
Levee=-1,0,6.52,-1,4.6,5.92,,
Bank Sta=0,4.6
XS Rating Curve= 0
Exp/Cntr=.3,.1

Type RM Length L Ch R = 1 ,2       ,50,50,50
#Sta/Elev= 12
   -15.2    2.97    -5.2    2.97    -3.2    4.17      -2    4.17     -.5    5.37
       0    5.37       2    4.17       4    4.17       6    5.57       7    5.57
       8    4.57      18    4.57
#Mann= 3 , 0 , 0
   -15.2    .033       0       0    .033       0       6    .033       0
Levee=-1,0,5.37,-1,6,5.57,,
Bank Sta=0,6
XS Rating Curve= 0
Exp/Cntr=.3,.1

Type RM Length L Ch R = 1 ,1       ,50,50,50
#Sta/Elev= 12
     -15    1.65      -5    1.65      -3    3.45    -1.8    3.45     -.3    4.65
       0    4.65       2    3.45       4    3.45       6    5.05       7    5.05
       8    4.05      18    4.05
#Mann= 3 , 0 , 0
     -15    .033       0       0    .033       0       6    .033       0
Levee=-1,0,10,-1,6,10,,
Bank Sta=0,6
XS Rating Curve= 0
Exp/Cntr=.3,.1

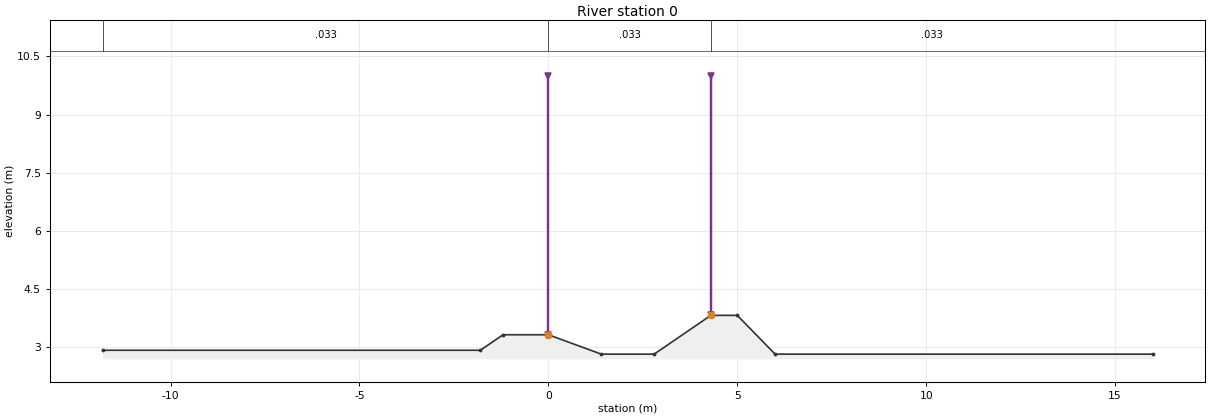
Type RM Length L Ch R = 1 ,0       ,0,0,0
#Sta/Elev= 10
   -11.8    2.92    -1.8    2.92    -1.2    3.32       0    3.32     1.4    2.82
     2.8    2.82     4.3    3.82       5    3.82       6    2.82      16    2.82
#Mann= 3 , 0 , 0
   -11.8    .033       0       0    .033       0     4.3    .033       0
Levee=-1,0,10,-1,4.3,10,,
Bank Sta=0,4.3
XS Rating Curve= 0
Exp/Cntr=.3,.1

Chan Stop Cuts=-1