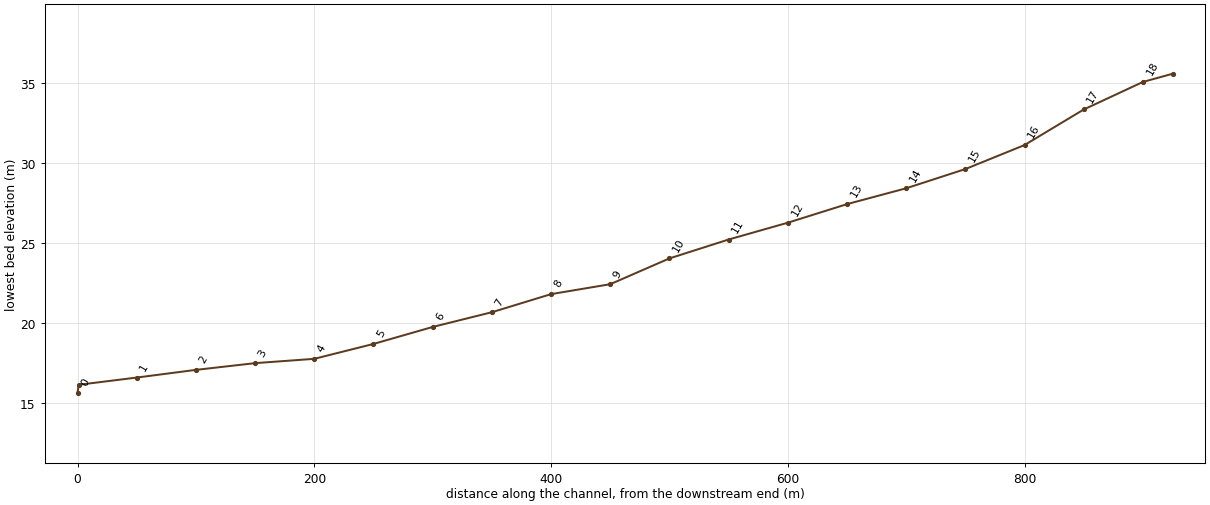
--- KSC.prj (project) ---

Proj Title=KIMSIN
Current Plan=p01
Default Exp/Contr=.3,.1
SI Units
Geom File=g01
Flow File=f01
Plan File=p01
Y Axis Title=Elevation
X Axis Title(PF)=Main Channel Distance
X Axis Title(XS)=Station
BEGIN DESCRIPTION:
           BACK WATER COMPUTATION
      APPLICATION OF HEC-2 BY Samju Construction Engineering
      KIMSIN-STREEM : 30 YR
END DESCRIPTION:
DSS Export Rating Curves= 0
DSS Export Rating Curve Sorted= 0
DSS Export Volume Flow Curves= 0
DXF OffsetX= 0
DXF OffsetY= 0
DXF ScaleX= 1
DXF ScaleY= 10

--- KSC.p01 (plan) ---

Plan Title=Imported Plan 01
Version=Version 3.0.1  Mar 2001
Short Identifier=Imported Pla
Geom File=g01
Flow File=f01
Subcritical Flow
K Sum by GR= 0
Std Step Tol= 0.003
Critical Tol= 0.003
Num of Std Step Trials= 20
Max Error Tol= 0.1
Flow Tol Ratio= 0.001
Split Flow NTrial= 30
Split Flow Tol= 0.02
Split Flow Ratio= 0.02
Log Output Level= 0
Friction Slope Method= 1
Unsteady Friction Slope Method= 2
Parabolic Critical Depth
Global Vel Dist= 0 , 0 , 0
Global Log Level= 0
CheckData=True
Encroach Param=-1 ,0,0, 0
Computation Interval=1HOUR
Output Interval=1HOUR
Run HTab= 0
Run UNet= 0
Run PostProcess= 0
UNET Theta= 1
UNET ZTol= 0.02
UNET ZSATol= 0.1
UNET MxIter= 20
UNET MaxInSteps= 20
UNET DtIC= 0
UNET DtMin= 0
UNET MaxCRTS= 20
UNET WFStab= 2
UNET SFStab= 1
UNET WFX= 1
UNET SFX= 1
UNET Convert EG Bridges=-1
UNET Use Existing IB Tables=-1
Instantaneous Interval=1HOUR
Write IC File= 0
Write Velocity= 0
Write Detailed= 0

--- KSC.f01 (steady flow) ---

Flow Title=Imported Flow 01
Version=Version 3.0.1  Mar 2001
Number of Profiles= 5
Profile Names=10YR,20YR,30YR,50YR,80YR
River Rch & RM=RIVER-1,Reach-1         ,18.025
   18.11   19.95   21.03   22.39   23.64
River Rch & RM=KIMSIN,KIMSIN          ,18.025
   18.11   19.95   21.03   22.39   23.64
Boundary for River Rch & Prof#=KIMSIN,KIMSIN          , 1
Up Type= 0
Dn Type= 3
Dn Slope=.024
Boundary for River Rch & Prof#=KIMSIN,KIMSIN          , 2
Up Type= 0
Dn Type= 3
Dn Slope=.024
Boundary for River Rch & Prof#=KIMSIN,KIMSIN          , 3
Up Type= 0
Dn Type= 3
Dn Slope=.024
Boundary for River Rch & Prof#=KIMSIN,KIMSIN          , 4
Up Type= 0
Dn Type= 3
Dn Slope=.024
Boundary for River Rch & Prof#=KIMSIN,KIMSIN          , 5
Up Type= 0
Dn Type= 3
Dn Slope=.024
DSS Import GetInterval= 0
DSS Import GetPeak= 0
DSS Import FillOption= 0

--- KSC.g01 (geometry) ---

Geom Title=Imported Geom 01
Version=Version 3.0.1  Mar 2001

River Reach=KIMSIN          ,KIMSIN
Reach XY= 2
              .5             .95              .5             .05

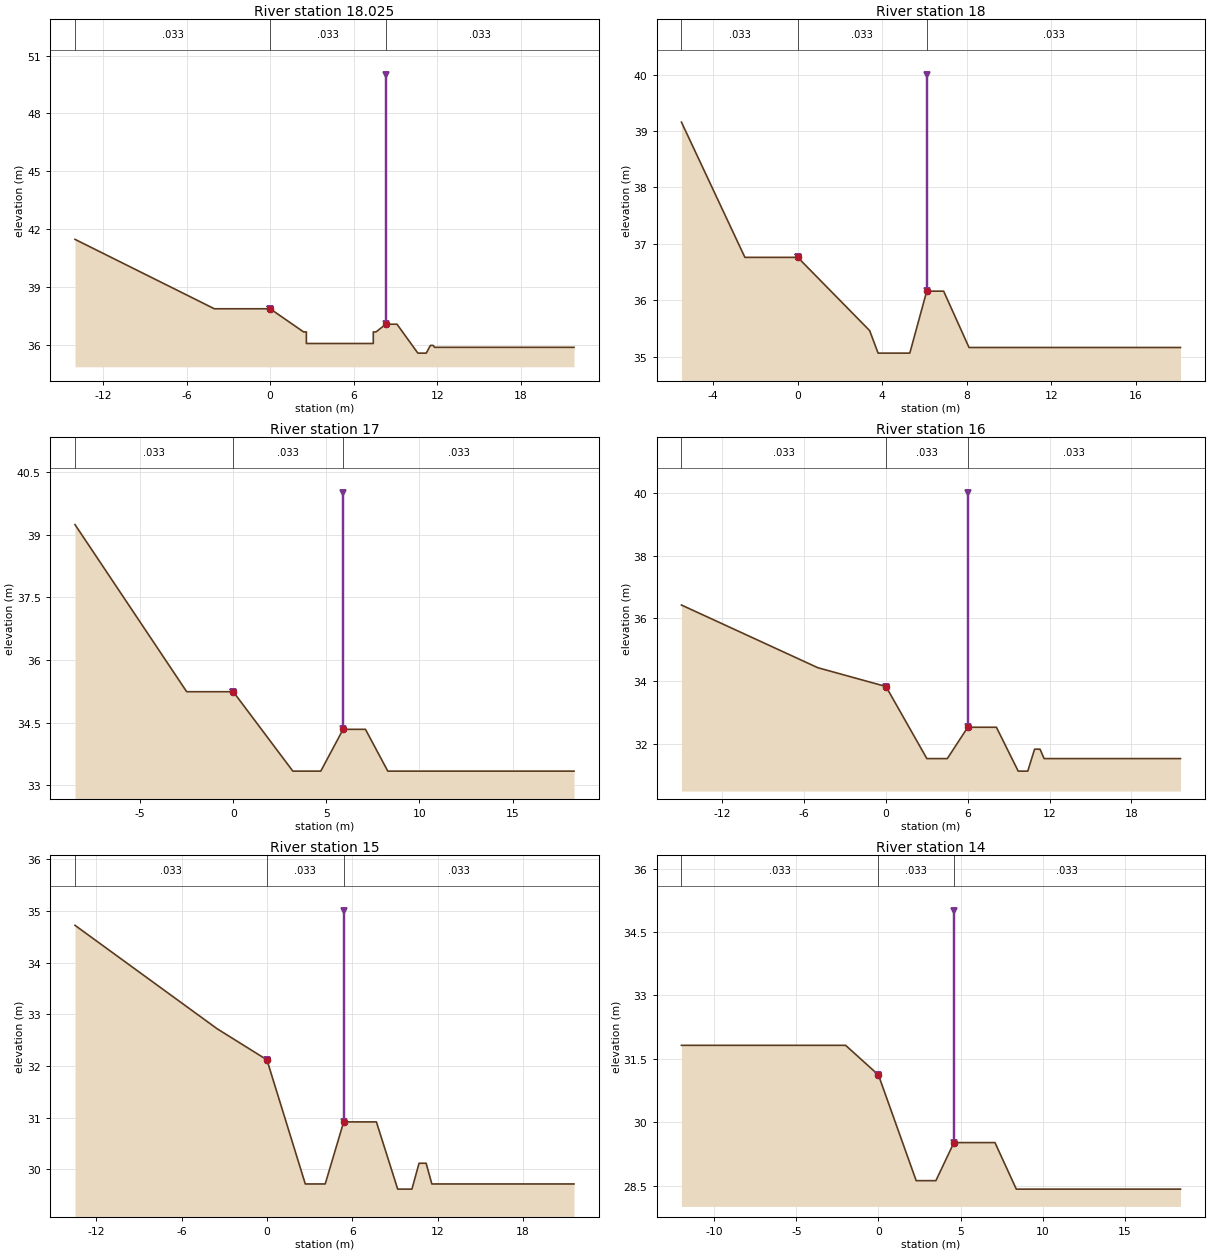
Type RM Length L Ch R = 1 ,18.025  ,25,25,25
#Sta/Elev= 18
     -14   41.47      -9   39.67      -4   37.87       0   37.87     2.4   36.67
     2.6   36.67     2.6   36.07     7.4   36.07     7.4   36.67     7.6   36.67
     8.3   37.07     9.1   37.07    10.6   35.57    11.2   35.57    11.5   35.97
    11.7   35.97    11.8   35.87    21.8   35.87
#Mann= 3 , 0 , 0
     -14    .033       0       0    .033       0     8.3    .033       0
Levee=-1,0,37.87,-1,8.3,50,,
Bank Sta=0,8.3
XS Rating Curve= 0
Exp/Cntr=.3,.1

Type RM Length L Ch R = 1 ,18      ,50,50,50
#Sta/Elev= 10
    -5.5   39.16    -2.5   36.76       0   36.76     3.4   35.46     3.8   35.06
     5.3   35.06     6.1   36.16     6.9   36.16     8.1   35.16    18.1   35.16
#Mann= 3 , 0 , 0
    -5.5    .033       0       0    .033       0     6.1    .033       0
Levee=-1,0,36.76,-1,6.1,40,,
Bank Sta=0,6.1
XS Rating Curve= 0
Exp/Cntr=.3,.1

Type RM Length L Ch R = 1 ,17      ,50,50,50
#Sta/Elev= 10
    -8.5   39.24    -5.5   37.24    -2.5   35.24       0   35.24     3.2   33.34
     4.7   33.34     5.9   34.34     7.1   34.34     8.3   33.34    18.3   33.34
#Mann= 3 , 0 , 0
    -8.5    .033       0       0    .033       0     5.9    .033       0
Levee=-1,0,35.24,-1,5.9,40,,
Bank Sta=0,5.9
XS Rating Curve= 0
Exp/Cntr=.3,.1

Type RM Length L Ch R = 1 ,16      ,50,50,50
#Sta/Elev= 14
     -15   36.42     -10   35.42      -5   34.42       0   33.82       3   31.52
     4.5   31.52       6   32.52     8.1   32.52     9.7   31.12    10.4   31.12
    10.9   31.82    11.3   31.82    11.6   31.52    21.6   31.52
#Mann= 3 , 0 , 0
     -15    .033       0       0    .033       0       6    .033       0
Levee=-1,0,33.82,-1,6,40,,
Bank Sta=0,6
XS Rating Curve= 0
Exp/Cntr=.3,.1

Type RM Length L Ch R = 1 ,15      ,50,50,50
#Sta/Elev= 14
   -13.5   34.72    -8.5   33.72    -3.5   32.72       0   32.12     2.7   29.72
     4.1   29.72     5.4   30.92     7.7   30.92     9.2   29.62    10.2   29.62
    10.7   30.12    11.2   30.12    11.6   29.72    21.6   29.72
#Mann= 3 , 0 , 0
   -13.5    .033       0       0    .033       0     5.4    .033       0
Levee=-1,0,32.12,-1,5.4,35,,
Bank Sta=0,5.4
XS Rating Curve= 0
Exp/Cntr=.3,.1

Type RM Length L Ch R = 1 ,14      ,50,50,50
#Sta/Elev= 9
     -12   31.82      -2   31.82       0   31.12     2.3   28.62     3.5   28.62
     4.6   29.52     7.1   29.52     8.4   28.42    18.4   28.42
#Mann= 3 , 0 , 0
     -12    .033       0       0    .033       0     4.6    .033       0
Levee=-1,0,31.12,-1,4.6,35,,
Bank Sta=0,4.6
XS Rating Curve= 0
Exp/Cntr=.3,.1

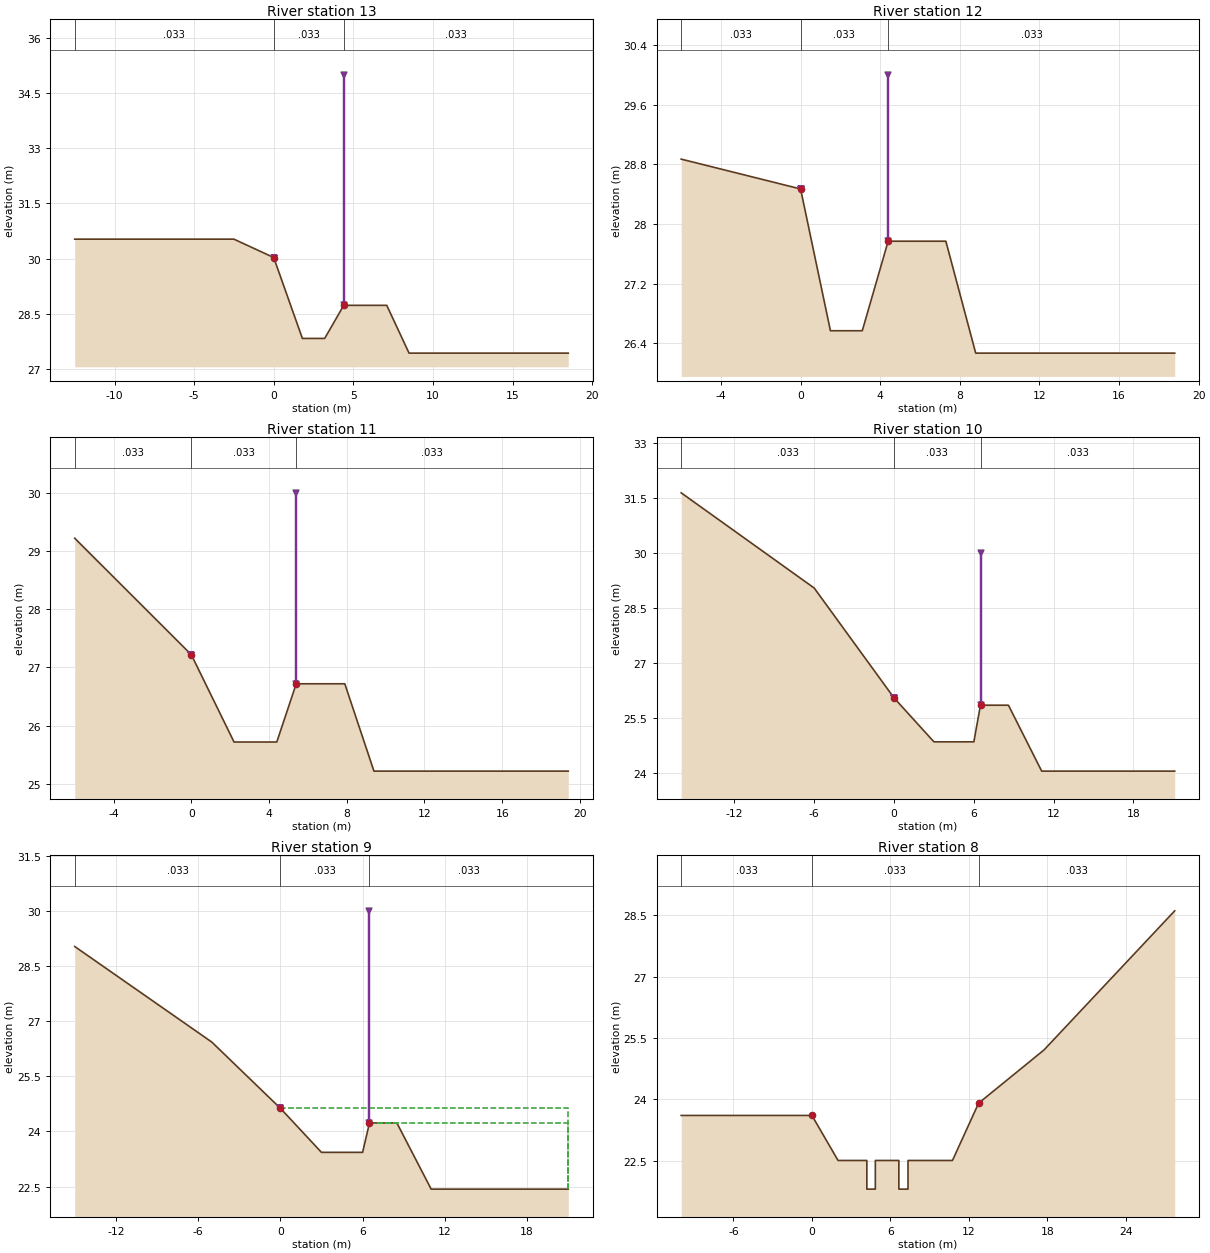
Type RM Length L Ch R = 1 ,13      ,50,50,50
#Sta/Elev= 9
   -12.5   30.53    -2.5   30.53       0   30.03     1.8   27.83     3.2   27.83
     4.4   28.73     7.1   28.73     8.5   27.43    18.5   27.43
#Mann= 3 , 0 , 0
   -12.5    .033       0       0    .033       0     4.4    .033       0
Levee=-1,0,30.03,-1,4.4,35,,
Bank Sta=0,4.4
XS Rating Curve= 0
Exp/Cntr=.3,.1

Type RM Length L Ch R = 1 ,12      ,50,50,50
#Sta/Elev= 9
      -6   28.87      -3   28.67       0   28.47     1.5   26.57     3.1   26.57
     4.4   27.77     7.3   27.77     8.8   26.27    18.8   26.27
#Mann= 3 , 0 , 0
      -6    .033       0       0    .033       0     4.4    .033       0
Levee=-1,0,28.47,-1,4.4,30,,
Bank Sta=0,4.4
XS Rating Curve= 0
Exp/Cntr=.3,.1

Type RM Length L Ch R = 1 ,11      ,50,50,50
#Sta/Elev= 9
      -6   29.22      -3   28.22       0   27.22     2.2   25.72     4.4   25.72
     5.4   26.72     7.9   26.72     9.4   25.22    19.4   25.22
#Mann= 3 , 0 , 0
      -6    .033       0       0    .033       0     5.4    .033       0
Levee=-1,0,27.22,-1,5.4,30,,
Bank Sta=0,5.4
XS Rating Curve= 0
Exp/Cntr=.3,.1

Type RM Length L Ch R = 1 ,10      ,50,50,50
#Sta/Elev= 11
     -16   31.64     -11   30.34      -6   29.04      -3   27.54       0   26.04
       3   24.84       6   24.84     6.5   25.84     8.6   25.84    11.1   24.04
    21.1   24.04
#Mann= 3 , 0 , 0
     -16    .033       0       0    .033       0     6.5    .033       0
Levee=-1,0,26.04,-1,6.5,30,,
Bank Sta=0,6.5
XS Rating Curve= 0
Exp/Cntr=.3,.1

Type RM Length L Ch R = 1 ,9       ,50,50,50
#Sta/Elev= 10
     -15   29.03     -10   27.73      -5   26.43       0   24.63       3   23.43
       6   23.43     6.5   24.23     8.5   24.23      11   22.43      21   22.43
#Mann= 3 , 0 , 0
     -15    .033       0       0    .033       0     6.5    .033       0
Levee=-1,0,24.63,-1,6.5,30,,
#XS Ineff= 2 , 0
       0       0   24.63     6.5       0   24.23
Permanent Ineff=
       F       F
Bank Sta=0,6.5
XS Rating Curve= 0
Exp/Cntr=.3,.1

Type RM Length L Ch R = 1 ,8       ,50,50,50
#Sta/Elev= 16
     -10   23.61       0   23.61       2   22.51     4.2   22.51     4.2   21.81
    4.85   21.81    4.85   22.51    6.65   22.51    6.65   21.81    7.35   21.81
    7.35   22.51   10.75   22.51   12.75   23.91   17.75   25.21   22.75   26.91
   27.75   28.61
#Mann= 3 , 0 , 0
     -10    .033       0       0    .033       0   12.75    .033       0
Bank Sta=0,12.75
XS Rating Curve= 0
Exp/Cntr=.3,.1

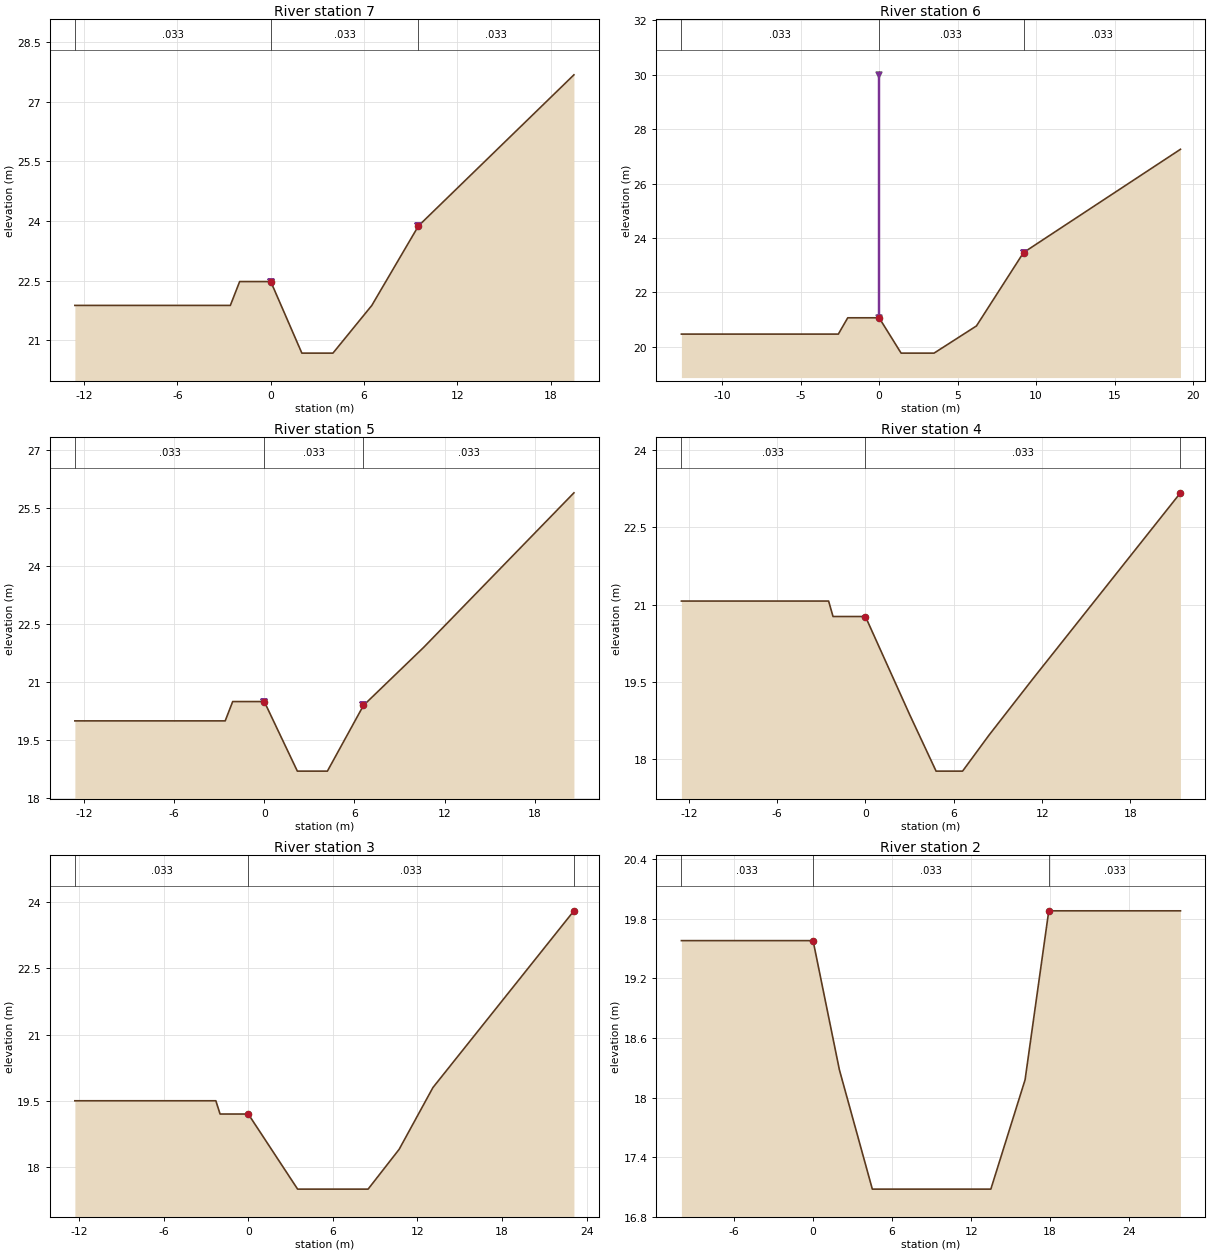
Type RM Length L Ch R = 1 ,7       ,50,50,50
#Sta/Elev= 10
   -12.6   21.88    -2.6   21.88      -2   22.48       0   22.48       2   20.68
       4   20.68     6.5   21.88     9.5   23.88    14.5   25.78    19.5   27.68
#Mann= 3 , 0 , 0
   -12.6    .033       0       0    .033       0     9.5    .033       0
Levee=-1,0,22.48,-1,9.5,23.88,,
Bank Sta=0,9.5
XS Rating Curve= 0
Exp/Cntr=.3,.1

Type RM Length L Ch R = 1 ,6       ,50,50,50
#Sta/Elev= 10
   -12.6   20.46    -2.6   20.46      -2   21.06       0   21.06     1.4   19.76
     3.5   19.76     6.2   20.76     9.2   23.46    14.2   25.36    19.2   27.26
#Mann= 3 , 0 , 0
   -12.6    .033       0       0    .033       0     9.2    .033       0
Levee=-1,0,30,-1,9.2,23.46,,
Bank Sta=0,9.2
XS Rating Curve= 0
Exp/Cntr=.3,.1

Type RM Length L Ch R = 1 ,5       ,50,50,50
#Sta/Elev= 10
   -12.6      20    -2.6      20    -2.1    20.5       0    20.5     2.2    18.7
     4.2    18.7     6.6    20.4    10.6    21.9    15.6    23.9    20.6    25.9
#Mann= 3 , 0 , 0
   -12.6    .033       0       0    .033       0     6.6    .033       0
Levee=-1,0,20.5,-1,6.6,20.4,,
Bank Sta=0,6.6
XS Rating Curve= 0
Exp/Cntr=.3,.1

Type RM Length L Ch R = 1 ,4       ,50,50,50
#Sta/Elev= 11
   -12.5   21.07    -2.5   21.07    -2.2   20.77       0   20.77       3   18.87
     4.8   17.77     6.6   17.77     8.4   18.47    11.4   19.57    16.4   21.37
    21.4   23.17
#Mann= 3 , 0 , 0
   -12.5    .033       0       0    .033       0    21.4    .033       0
Bank Sta=0,21.4
XS Rating Curve= 0
Exp/Cntr=.3,.1

Type RM Length L Ch R = 1 ,3       ,50,50,50
#Sta/Elev= 10
   -12.3    19.5    -2.3    19.5      -2    19.2       0    19.2     3.5    17.5
     8.5    17.5    10.7    18.4    13.1    19.8    18.1    21.8    23.1    23.8
#Mann= 3 , 0 , 0
   -12.3    .033       0       0    .033       0    23.1    .033       0
Bank Sta=0,23.1
XS Rating Curve= 0
Exp/Cntr=.3,.1

Type RM Length L Ch R = 1 ,2       ,50,50,50
#Sta/Elev= 8
     -10   19.58       0   19.58       2   18.28     4.5   17.08    13.5   17.08
    16.1   18.18    17.9   19.88    27.9   19.88
#Mann= 3 , 0 , 0
     -10    .033       0       0    .033       0    17.9    .033       0
Bank Sta=0,17.9
XS Rating Curve= 0
Exp/Cntr=.3,.1

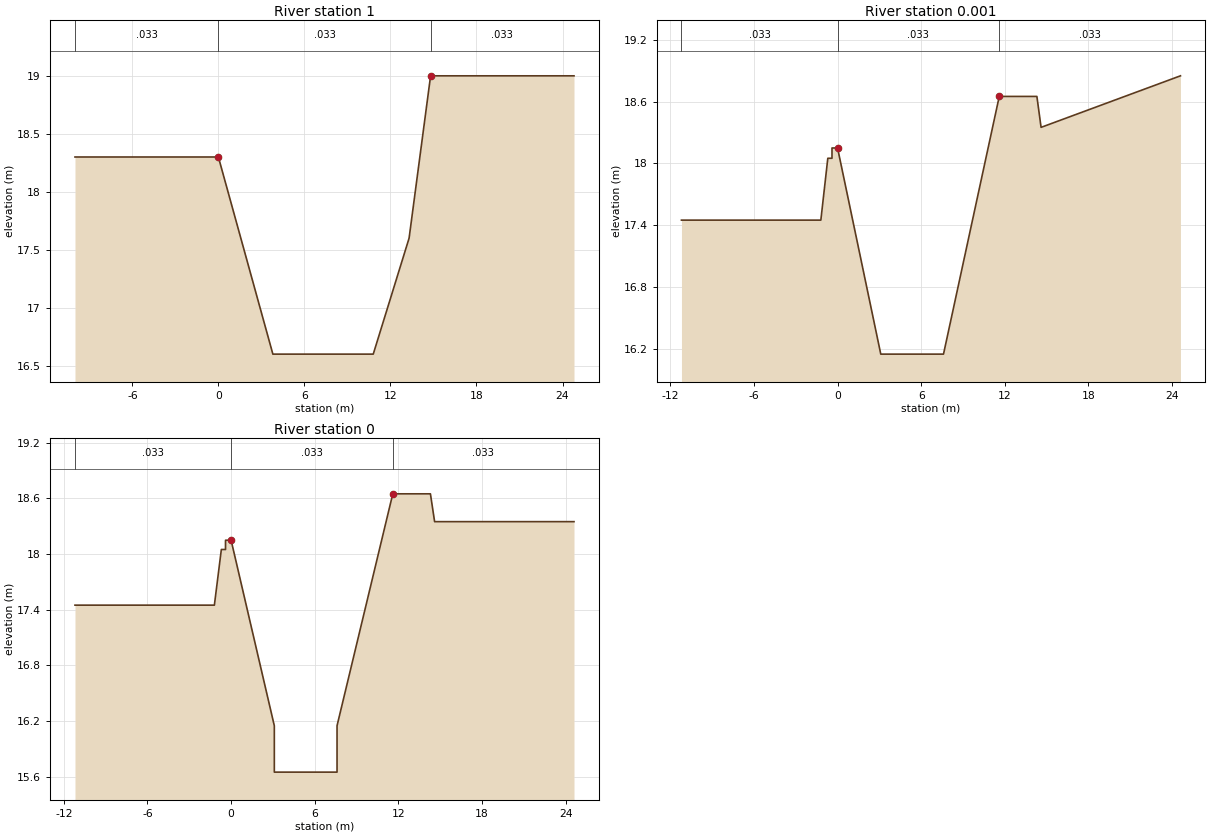
Type RM Length L Ch R = 1 ,1       ,49,49,49
#Sta/Elev= 7
     -10    18.3       0    18.3     3.8    16.6    10.8    16.6    13.3    17.6
    14.8      19    24.8      19
#Mann= 3 , 0 , 0
     -10    .033       0       0    .033       0    14.8    .033       0
Bank Sta=0,14.8
XS Rating Curve= 0
Exp/Cntr=.3,.1

Type RM Length L Ch R = 1 ,0.001   ,1,1,1
#Sta/Elev= 12
   -11.2   17.45    -1.2   17.45     -.7   18.05     -.4   18.05     -.4   18.15
       0   18.15     3.1   16.15     7.6   16.15    11.6   18.65    14.3   18.65
    14.6   18.35    24.6   18.85
#Mann= 3 , 0 , 0
   -11.2    .033       0       0    .033       0    11.6    .033       0
Bank Sta=0,11.6
XS Rating Curve= 0
Exp/Cntr=.3,.1

Type RM Length L Ch R = 1 ,0       ,0,0,0
#Sta/Elev= 14
   -11.2   17.45    -1.2   17.45     -.7   18.05     -.4   18.05     -.4   18.15
       0   18.15     3.1   16.15     3.1   15.65     7.6   15.65     7.6   16.15
    11.6   18.65    14.3   18.65    14.6   18.35    24.6   18.35
#Mann= 3 , 0 , 0
   -11.2    .033       0       0    .033       0    11.6    .033       0
Bank Sta=0,11.6
XS Rating Curve= 0
Exp/Cntr=.3,.1

Chan Stop Cuts=-1