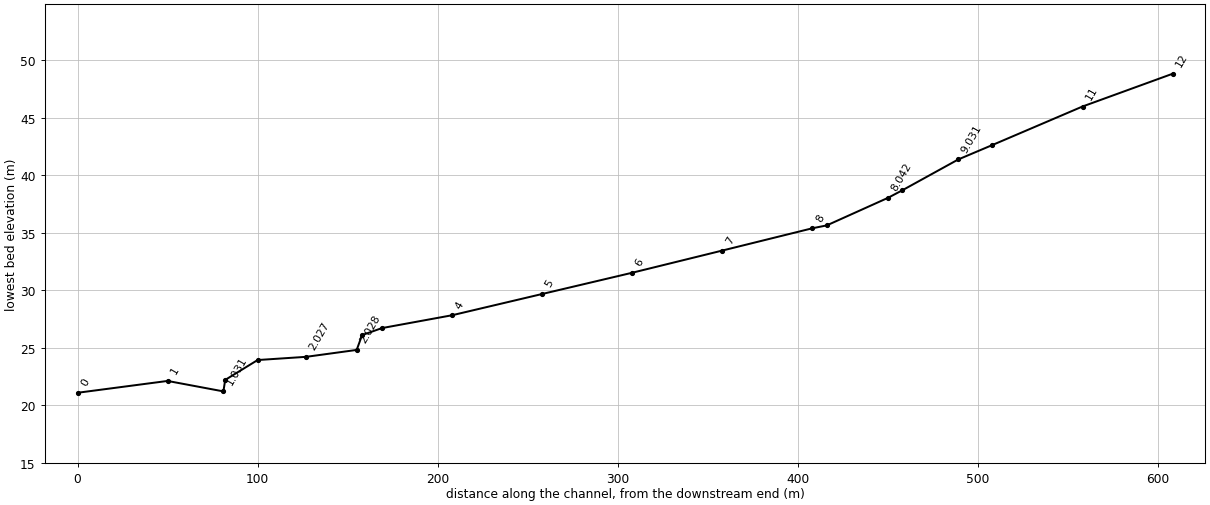
--- KSC.prj (project) ---

Proj Title=KYOSUNG
Current Plan=p01
Default Exp/Contr=.3,.1
SI Units
Geom File=g01
Flow File=f01
Plan File=p01
Y Axis Title=Elevation
X Axis Title(PF)=Main Channel Distance
X Axis Title(XS)=Station
BEGIN DESCRIPTION:
           BACK WATER COMPUTATION
      APPLICATION OF HEC-2 BY Samju Construction Engineering
      KYOSONG-STREEM : 30 YR
END DESCRIPTION:
DSS Export Rating Curves= 0
DSS Export Rating Curve Sorted= 0
DSS Export Volume Flow Curves= 0
DXF OffsetX= 0
DXF OffsetY= 0
DXF ScaleX= 1
DXF ScaleY= 10

--- KSC.p01 (plan) ---

Plan Title=Imported Plan 01
Version=Version 3.0.1  Mar 2001
Short Identifier=Imported Pla
Geom File=g01
Flow File=f01
Subcritical Flow
K Sum by GR= 0
Std Step Tol= 0.003
Critical Tol= 0.003
Num of Std Step Trials= 20
Max Error Tol= 0.1
Flow Tol Ratio= 0.001
Split Flow NTrial= 30
Split Flow Tol= 0.02
Split Flow Ratio= 0.02
Log Output Level= 0
Friction Slope Method= 1
Unsteady Friction Slope Method= 2
Parabolic Critical Depth
Global Vel Dist= 0 , 0 , 0
Global Log Level= 0
CheckData=True
Encroach Param=-1 ,0,0, 0
Computation Interval=1HOUR
Output Interval=1HOUR
Run HTab= 0
Run UNet= 0
Run PostProcess= 0
UNET Theta= 1
UNET ZTol= 0.02
UNET ZSATol= 0.1
UNET MxIter= 20
UNET MaxInSteps= 20
UNET DtIC= 0
UNET DtMin= 0
UNET MaxCRTS= 20
UNET WFStab= 2
UNET SFStab= 1
UNET WFX= 1
UNET SFX= 1
UNET Convert EG Bridges=-1
UNET Use Existing IB Tables=-1
Instantaneous Interval=1HOUR
Write IC File= 0
Write Velocity= 0
Write Detailed= 0

--- KSC.f01 (steady flow) ---

Flow Title=Imported Flow 01
Version=Version 3.0.1  Mar 2001
Number of Profiles= 5
Profile Names=10YR,20YR,30YR,50YR,80YR
River Rch & RM=RIVER-1,Reach-1         ,12
    3.94    4.34    4.57    4.87    5.14
River Rch & RM=KYOSUNG,KYOSUNG         ,12
    3.94    4.34    4.57    4.87    5.14
Boundary for River Rch & Prof#=KYOSUNG,KYOSUNG         , 1
Up Type= 0
Dn Type= 3
Dn Slope=.046
Boundary for River Rch & Prof#=KYOSUNG,KYOSUNG         , 2
Up Type= 0
Dn Type= 3
Dn Slope=.046
Boundary for River Rch & Prof#=KYOSUNG,KYOSUNG         , 3
Up Type= 0
Dn Type= 3
Dn Slope=.046
Boundary for River Rch & Prof#=KYOSUNG,KYOSUNG         , 4
Up Type= 0
Dn Type= 3
Dn Slope=.046
Boundary for River Rch & Prof#=KYOSUNG,KYOSUNG         , 5
Up Type= 0
Dn Type= 3
Dn Slope=.046
DSS Import GetInterval= 0
DSS Import GetPeak= 0
DSS Import FillOption= 0

--- KSC.g01 (geometry) ---

Geom Title=Imported Geom 01
Version=Version 3.0.1  Mar 2001

River Reach=KYOSUNG         ,KYOSUNG
Reach XY= 2
              .5             .95              .5             .05

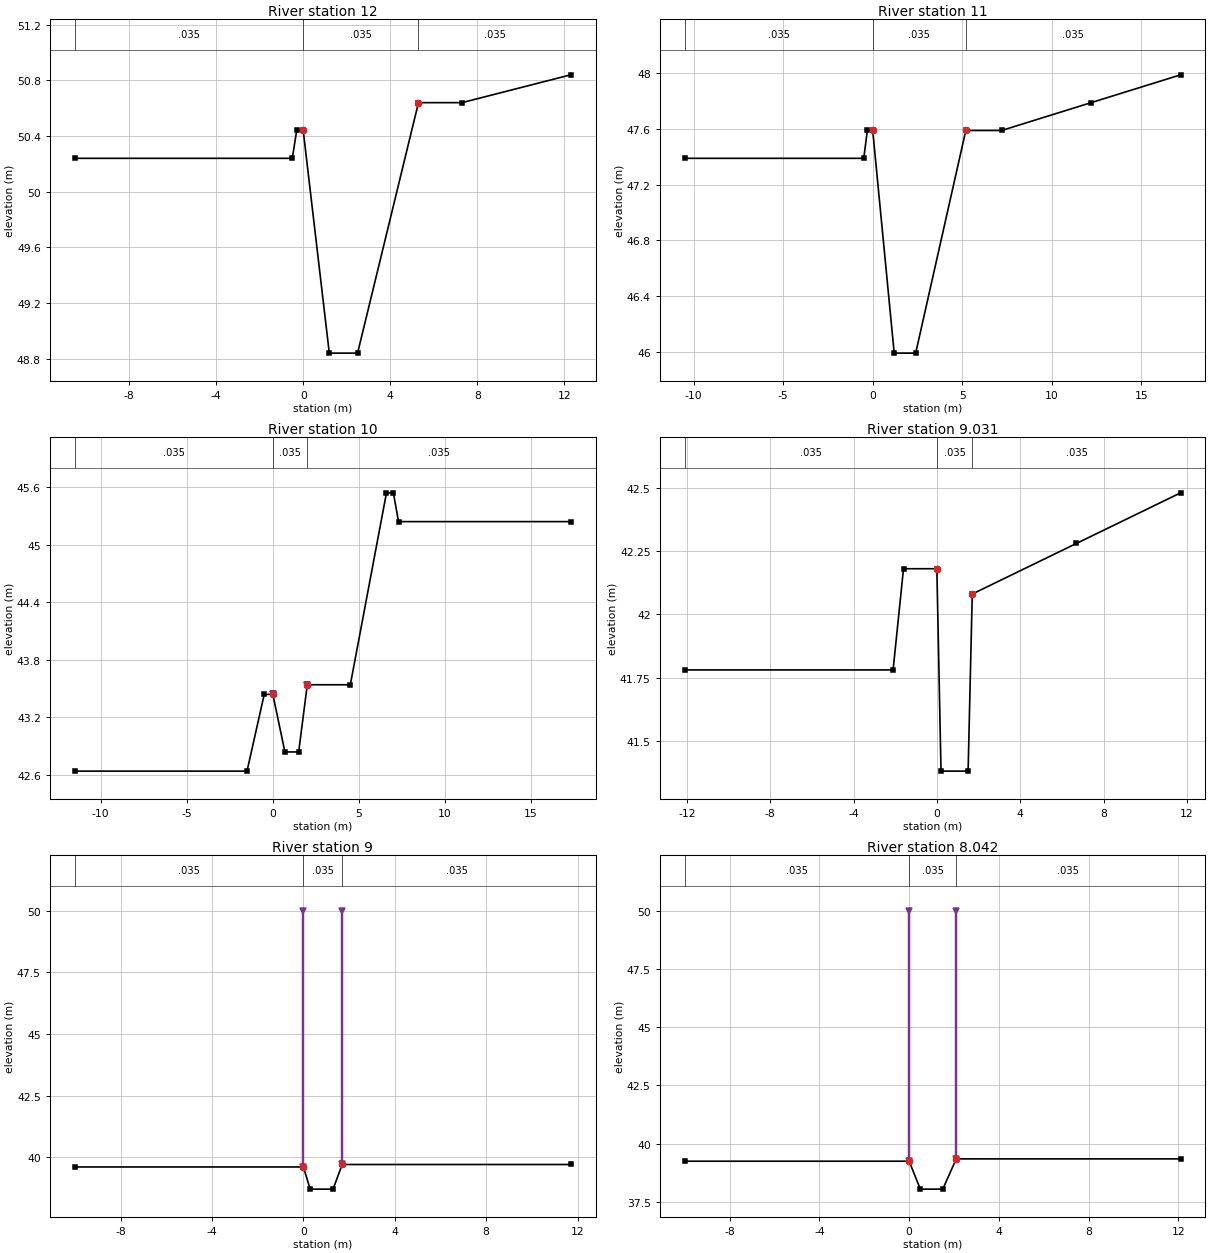
Type RM Length L Ch R = 1 ,12      ,50,50,50
#Sta/Elev= 9
   -10.5   50.24     -.5   50.24     -.3   50.44       0   50.44     1.2   48.84
     2.5   48.84     5.3   50.64     7.3   50.64    12.3   50.84
#Mann= 3 , 0 , 0
   -10.5    .035       0       0    .035       0     5.3    .035       0
Bank Sta=0,5.3
XS Rating Curve= 0
Exp/Cntr=.3,.1

Type RM Length L Ch R = 1 ,11      ,50,50,50
#Sta/Elev= 10
   -10.5   47.39     -.5   47.39     -.3   47.59       0   47.59     1.2   45.99
     2.4   45.99     5.2   47.59     7.2   47.59    12.2   47.79    17.2   47.99
#Mann= 3 , 0 , 0
   -10.5    .035       0       0    .035       0     5.2    .035       0
Bank Sta=0,5.2
XS Rating Curve= 0
Exp/Cntr=.3,.1

Type RM Length L Ch R = 1 ,10      ,19,19,19
#Sta/Elev= 12
   -11.5   42.64    -1.5   42.64     -.5   43.44       0   43.44      .7   42.84
     1.5   42.84       2   43.54     4.5   43.54     6.6   45.54       7   45.54
     7.3   45.24    17.3   45.24
#Mann= 3 , 0 , 0
   -11.5    .035       0       0    .035       0       2    .035       0
Levee=-1,0,43.44,-1,2,43.54,,
Bank Sta=0,2
XS Rating Curve= 0
Exp/Cntr=.3,.1

Type RM Length L Ch R = 1 ,9.031   ,31,31,31
#Sta/Elev= 9
   -12.1   41.78    -2.1   41.78    -1.6   42.18       0   42.18      .2   41.38
     1.5   41.38     1.7   42.08     6.7   42.28    11.7   42.48
#Mann= 3 , 0 , 0
   -12.1    .035       0       0    .035       0     1.7    .035       0
Bank Sta=0,1.7
XS Rating Curve= 0
Exp/Cntr=.3,.1

Type RM Length L Ch R = 1 ,9       ,8,8,8
#Sta/Elev= 6
     -10    39.6       0    39.6      .3    38.7     1.3    38.7     1.7    39.7
    11.7    39.7
#Mann= 3 , 0 , 0
     -10    .035       0       0    .035       0     1.7    .035       0
Levee=-1,0,50,-1,1.7,50,,
Bank Sta=0,1.7
XS Rating Curve= 0
Exp/Cntr=.3,.1

Type RM Length L Ch R = 1 ,8.042   ,34,34,34
#Sta/Elev= 6
     -10   39.24       0   39.24      .5   38.04     1.5   38.04     2.1   39.34
    12.1   39.34
#Mann= 3 , 0 , 0
     -10    .035       0       0    .035       0     2.1    .035       0
Levee=-1,0,50,-1,2.1,50,,
Bank Sta=0,2.1
XS Rating Curve= 0
Exp/Cntr=.3,.1

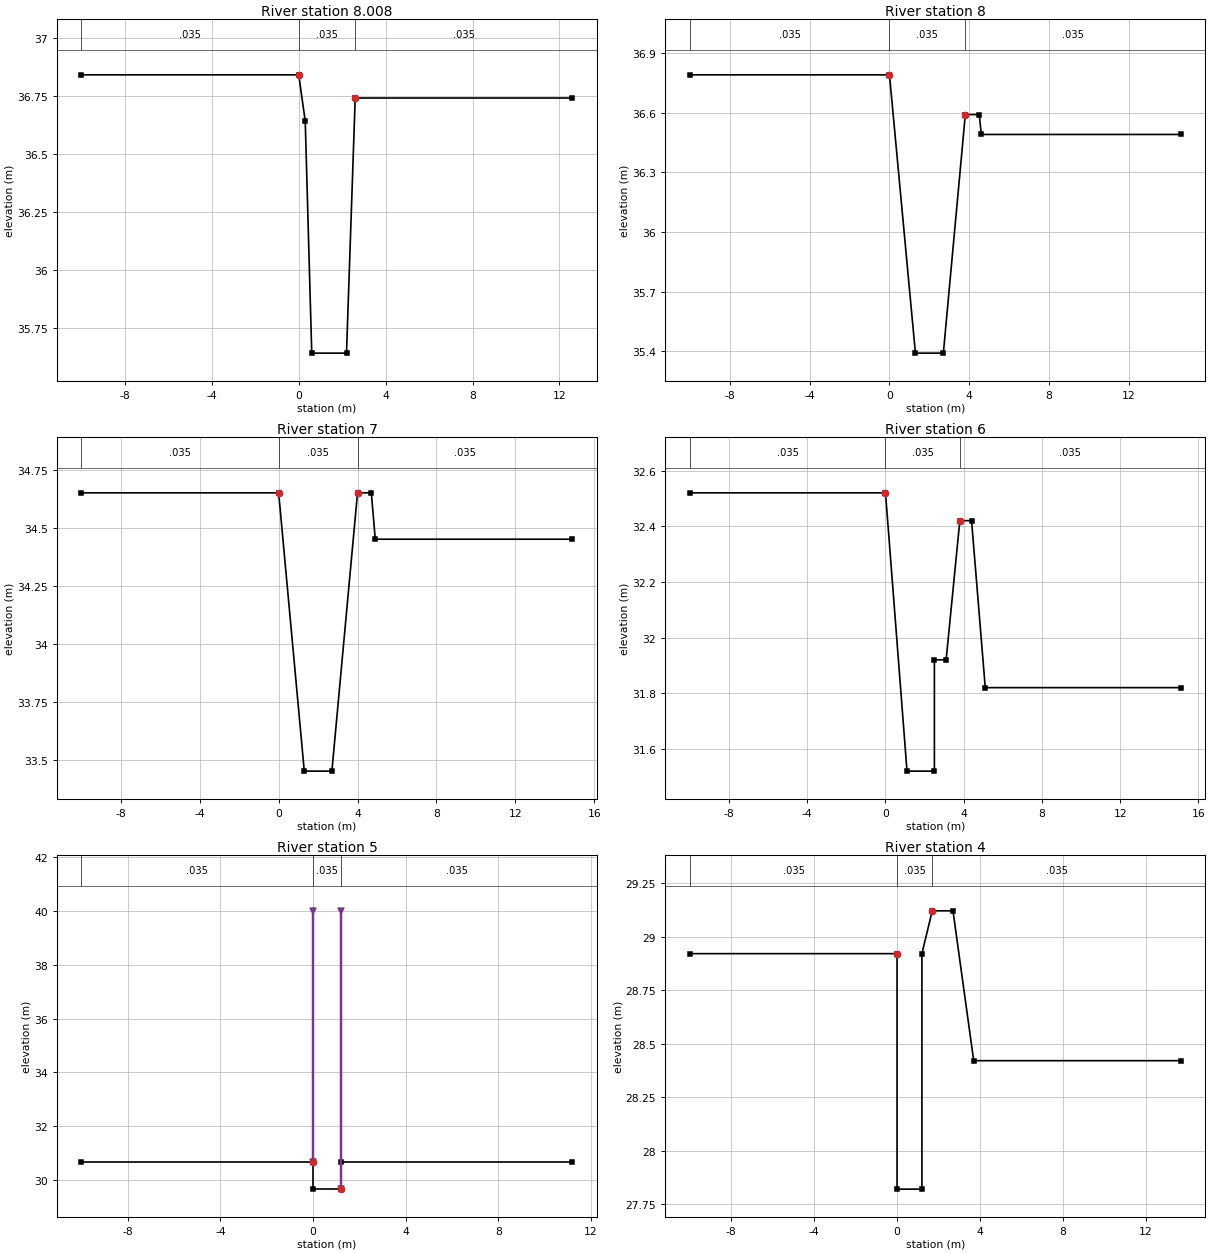
Type RM Length L Ch R = 1 ,8.008   ,8,8,8
#Sta/Elev= 7
     -10   36.84       0   36.84      .3   36.64      .6   35.64     2.2   35.64
     2.6   36.74    12.6   36.74
#Mann= 3 , 0 , 0
     -10    .035       0       0    .035       0     2.6    .035       0
Bank Sta=0,2.6
XS Rating Curve= 0
Exp/Cntr=.3,.1

Type RM Length L Ch R = 1 ,8       ,50,50,50
#Sta/Elev= 8
     -10   36.79       0   36.79     1.3   35.39     2.7   35.39     3.8   36.59
     4.5   36.59     4.6   36.49    14.6   36.49
#Mann= 3 , 0 , 0
     -10    .035       0       0    .035       0     3.8    .035       0
Bank Sta=0,3.8
XS Rating Curve= 0
Exp/Cntr=.3,.1

Type RM Length L Ch R = 1 ,7       ,50,50,50
#Sta/Elev= 8
     -10   34.65       0   34.65     1.3   33.45     2.7   33.45       4   34.65
     4.7   34.65     4.9   34.45    14.9   34.45
#Mann= 3 , 0 , 0
     -10    .035       0       0    .035       0       4    .035       0
Bank Sta=0,4
XS Rating Curve= 0
Exp/Cntr=.3,.1

Type RM Length L Ch R = 1 ,6       ,50,50,50
#Sta/Elev= 10
     -10   32.52       0   32.52     1.1   31.52     2.5   31.52     2.5   31.92
     3.1   31.92     3.8   32.42     4.4   32.42     5.1   31.82    15.1   31.82
#Mann= 3 , 0 , 0
     -10    .035       0       0    .035       0     3.8    .035       0
Bank Sta=0,3.8
XS Rating Curve= 0
Exp/Cntr=.3,.1

Type RM Length L Ch R = 1 ,5       ,50,50,50
#Sta/Elev= 6
     -10   30.67       0   30.67       0   29.67     1.2   29.67     1.2   30.67
    11.2   30.67
#Mann= 3 , 0 , 0
     -10    .035       0       0    .035       0     1.2    .035       0
Levee=-1,0,40,-1,1.2,40,,
Bank Sta=0,1.2
XS Rating Curve= 0
Exp/Cntr=.3,.1

Type RM Length L Ch R = 1 ,4       ,39,39,39
#Sta/Elev= 9
     -10   28.92       0   28.92       0   27.82     1.2   27.82     1.2   28.92
     1.7   29.12     2.7   29.12     3.7   28.42    13.7   28.42
#Mann= 3 , 0 , 0
     -10    .035       0       0    .035       0     1.7    .035       0
Bank Sta=0,1.7
XS Rating Curve= 0
Exp/Cntr=.3,.1

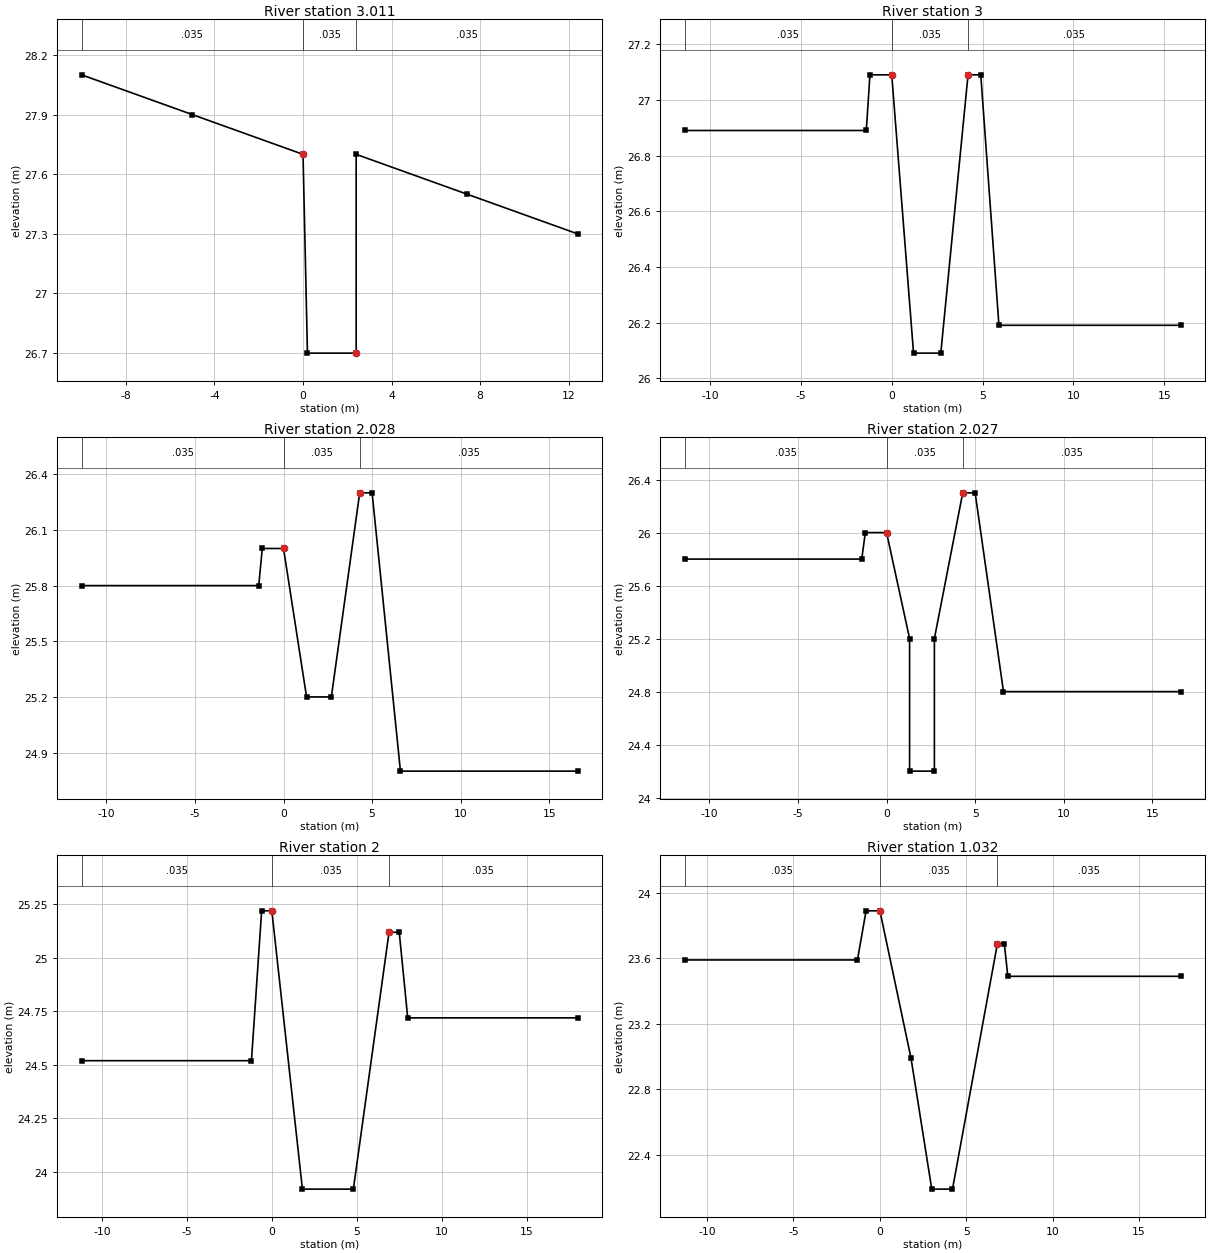
Type RM Length L Ch R = 1 ,3.011   ,11,11,11
#Sta/Elev= 8
     -10    28.1      -5    27.9       0    27.7      .2    26.7     2.4    26.7
     2.4    27.7     7.4    27.5    12.4    27.3
#Mann= 3 , 0 , 0
     -10    .035       0       0    .035       0     2.4    .035       0
Bank Sta=0,2.4
XS Rating Curve= 0
Exp/Cntr=.3,.1

Type RM Length L Ch R = 1 ,3       ,3,3,3
#Sta/Elev= 10
   -11.4   26.89    -1.4   26.89    -1.2   27.09       0   27.09     1.2   26.09
     2.7   26.09     4.2   27.09     4.9   27.09     5.9   26.19    15.9   26.19
#Mann= 3 , 0 , 0
   -11.4    .035       0       0    .035       0     4.2    .035       0
Bank Sta=0,4.2
XS Rating Curve= 0
Exp/Cntr=.3,.1

Type RM Length L Ch R = 1 ,2.028   ,28,28,28
#Sta/Elev= 10
   -11.4    25.8    -1.4    25.8    -1.2      26       0      26     1.3    25.2
     2.7    25.2     4.3    26.3       5    26.3     6.6    24.8    16.6    24.8
#Mann= 3 , 0 , 0
   -11.4    .035       0       0    .035       0     4.3    .035       0
Bank Sta=0,4.3
XS Rating Curve= 0
Exp/Cntr=.3,.1

Type RM Length L Ch R = 1 ,2.027   ,27,27,27
#Sta/Elev= 12
   -11.4    25.8    -1.4    25.8    -1.2      26       0      26     1.3    25.2
     1.3    24.2     2.7    24.2     2.7    25.2     4.3    26.3       5    26.3
     6.6    24.8    16.6    24.8
#Mann= 3 , 0 , 0
   -11.4    .035       0       0    .035       0     4.3    .035       0
Bank Sta=0,4.3
XS Rating Curve= 0
Exp/Cntr=.3,.1

Type RM Length L Ch R = 1 ,2       ,18,18,18
#Sta/Elev= 10
   -11.2   24.52    -1.2   24.52     -.6   25.22       0   25.22     1.8   23.92
     4.8   23.92     6.9   25.12     7.5   25.12       8   24.72      18   24.72
#Mann= 3 , 0 , 0
   -11.2    .035       0       0    .035       0     6.9    .035       0
Bank Sta=0,6.9
XS Rating Curve= 0
Exp/Cntr=.3,.1

Type RM Length L Ch R = 1 ,1.032   ,1,1,1
#Sta/Elev= 11
   -11.3   23.59    -1.3   23.59     -.8   23.89       0   23.89     1.8   22.99
       3   22.19     4.2   22.19     6.8   23.69     7.2   23.69     7.4   23.49
    17.4   23.49
#Mann= 3 , 0 , 0
   -11.3    .035       0       0    .035       0     6.8    .035       0
Bank Sta=0,6.8
XS Rating Curve= 0
Exp/Cntr=.3,.1

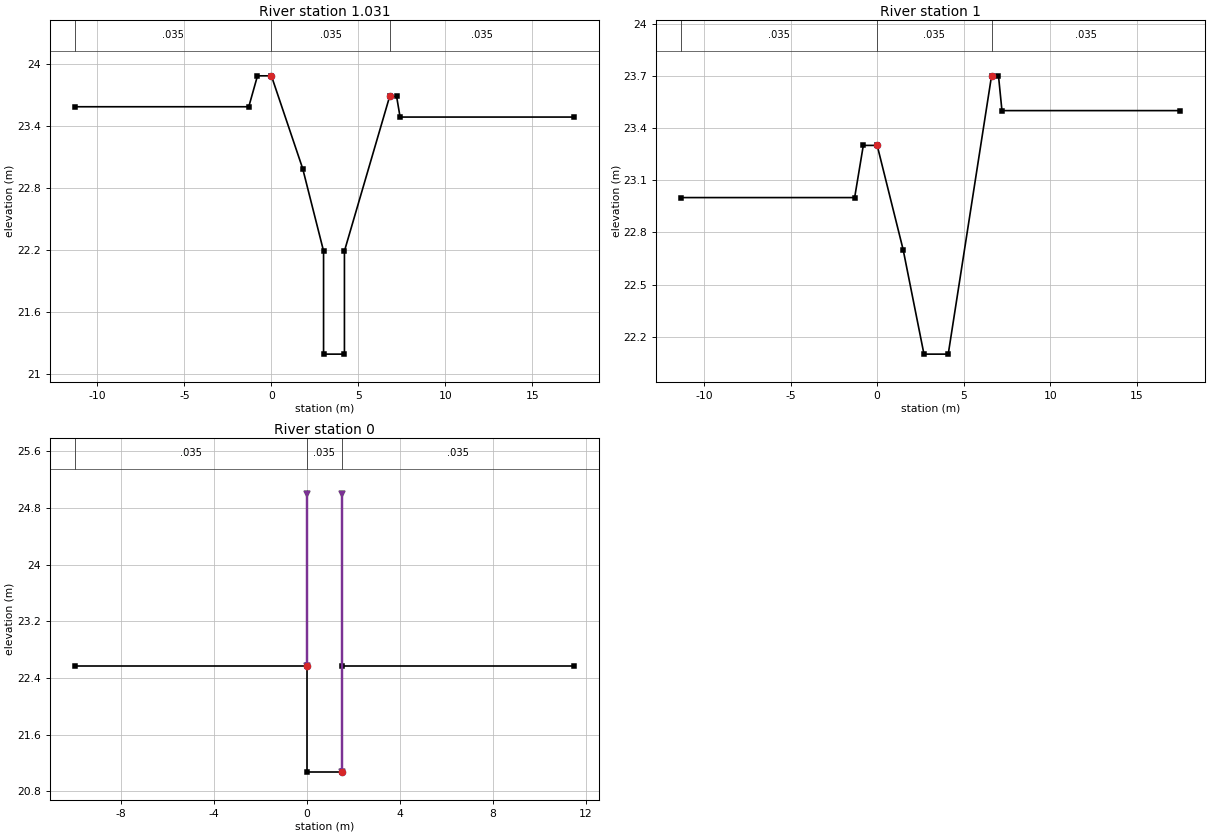
Type RM Length L Ch R = 1 ,1.031   ,31,31,31
#Sta/Elev= 13
   -11.3   23.59    -1.3   23.59     -.8   23.89       0   23.89     1.8   22.99
       3   22.19       3   21.19     4.2   21.19     4.2   22.19     6.8   23.69
     7.2   23.69     7.4   23.49    17.4   23.49
#Mann= 3 , 0 , 0
   -11.3    .035       0       0    .035       0     6.8    .035       0
Bank Sta=0,6.8
XS Rating Curve= 0
Exp/Cntr=.3,.1

Type RM Length L Ch R = 1 ,1       ,50,50,50
#Sta/Elev= 11
   -11.3      23    -1.3      23     -.8    23.3       0    23.3     1.5    22.7
     2.7    22.1     4.1    22.1     6.6    23.7       7    23.7     7.2    23.5
    17.5    23.5
#Mann= 3 , 0 , 0
   -11.3    .035       0       0    .035       0     6.6    .035       0
Bank Sta=0,6.6
XS Rating Curve= 0
Exp/Cntr=.3,.1

Type RM Length L Ch R = 1 ,0       ,0,0,0
#Sta/Elev= 6
     -10   22.57       0   22.57       0   21.07     1.5   21.07     1.5   22.57
    11.5   22.57
#Mann= 3 , 0 , 0
     -10    .035       0       0    .035       0     1.5    .035       0
Levee=-1,0,25,-1,1.5,25,,
Bank Sta=0,1.5
XS Rating Curve= 0
Exp/Cntr=.3,.1

Chan Stop Cuts=-1