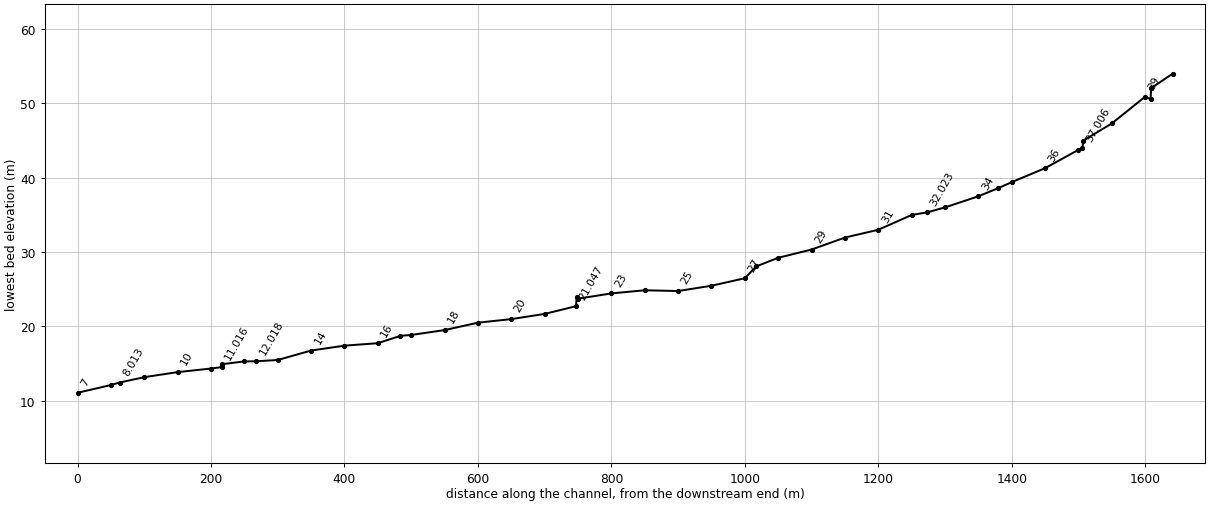
--- ODC.prj (project) ---

Proj Title=ODONG
Current Plan=p01
Default Exp/Contr=.3,.1
SI Units
Geom File=g01
Flow File=f01
Plan File=p01
Y Axis Title=Elevation
X Axis Title(PF)=Main Channel Distance
X Axis Title(XS)=Station
BEGIN DESCRIPTION:
           BACK WATER COMPUTATION
      APPLICATION OF HEC-2 BY Samju Construction Engineering
      ODONG-STREEM : 30 YR
END DESCRIPTION:
DSS Export Rating Curves= 0
DSS Export Rating Curve Sorted= 0
DSS Export Volume Flow Curves= 0
DXF OffsetX= 0
DXF OffsetY= 0
DXF ScaleX= 1
DXF ScaleY= 10

--- ODC.p01 (plan) ---

Plan Title=Imported Plan 01
Version=Version 3.0.1  Mar 2001
Short Identifier=Imported Pla
Geom File=g01
Flow File=f01
Subcritical Flow
K Sum by GR= 0
Std Step Tol= 0.003
Critical Tol= 0.003
Num of Std Step Trials= 20
Max Error Tol= 0.1
Flow Tol Ratio= 0.001
Split Flow NTrial= 30
Split Flow Tol= 0.02
Split Flow Ratio= 0.02
Log Output Level= 0
Friction Slope Method= 1
Unsteady Friction Slope Method= 2
Parabolic Critical Depth
Global Vel Dist= 0 , 0 , 0
Global Log Level= 0
CheckData=True
Encroach Param=-1 ,0,0, 0
Computation Interval=1HOUR
Output Interval=1HOUR
Run HTab= 0
Run UNet= 0
Run PostProcess= 0
UNET Theta= 1
UNET ZTol= 0.02
UNET ZSATol= 0.1
UNET MxIter= 20
UNET MaxInSteps= 20
UNET DtIC= 0
UNET DtMin= 0
UNET MaxCRTS= 20
UNET WFStab= 2
UNET SFStab= 1
UNET WFX= 1
UNET SFX= 1
UNET Convert EG Bridges=-1
UNET Use Existing IB Tables=-1
Instantaneous Interval=1HOUR
Write IC File= 0
Write Velocity= 0
Write Detailed= 0

--- ODC.f01 (steady flow) ---

Flow Title=Imported Flow 01
Version=Version 3.0.1  Mar 2001
Number of Profiles= 5
Profile Names=10YR,20YR,30YR,50YR,80YR
River Rch & RM=RIVER-1,Reach-1         ,39.041
    16.3   17.96   18.94   20.16   21.29
River Rch & RM=RIVER-1,Reach-1         ,22
   20.07   22.13   23.33   24.85   26.25
River Rch & RM=ODONG,ODONG           ,39.041
    16.3   17.96   18.94   20.16   21.29
River Rch & RM=ODONG,ODONG           ,22
   20.07   22.13   23.33   24.85   26.25
Boundary for River Rch & Prof#=ODONG,ODONG           , 1
Up Type= 0
Dn Type= 3
Dn Slope=.025
Boundary for River Rch & Prof#=ODONG,ODONG           , 2
Up Type= 0
Dn Type= 3
Dn Slope=.025
Boundary for River Rch & Prof#=ODONG,ODONG           , 3
Up Type= 0
Dn Type= 3
Dn Slope=.025
Boundary for River Rch & Prof#=ODONG,ODONG           , 4
Up Type= 0
Dn Type= 3
Dn Slope=.025
Boundary for River Rch & Prof#=ODONG,ODONG           , 5
Up Type= 0
Dn Type= 3
Dn Slope=.025
DSS Import GetInterval= 0
DSS Import GetPeak= 0
DSS Import FillOption= 0

--- ODC.g01 (geometry) ---

Geom Title=Imported Geom 01
Version=Version 3.0.1  Mar 2001

River Reach=ODONG           ,ODONG
Reach XY= 2
              .5             .95              .5             .05

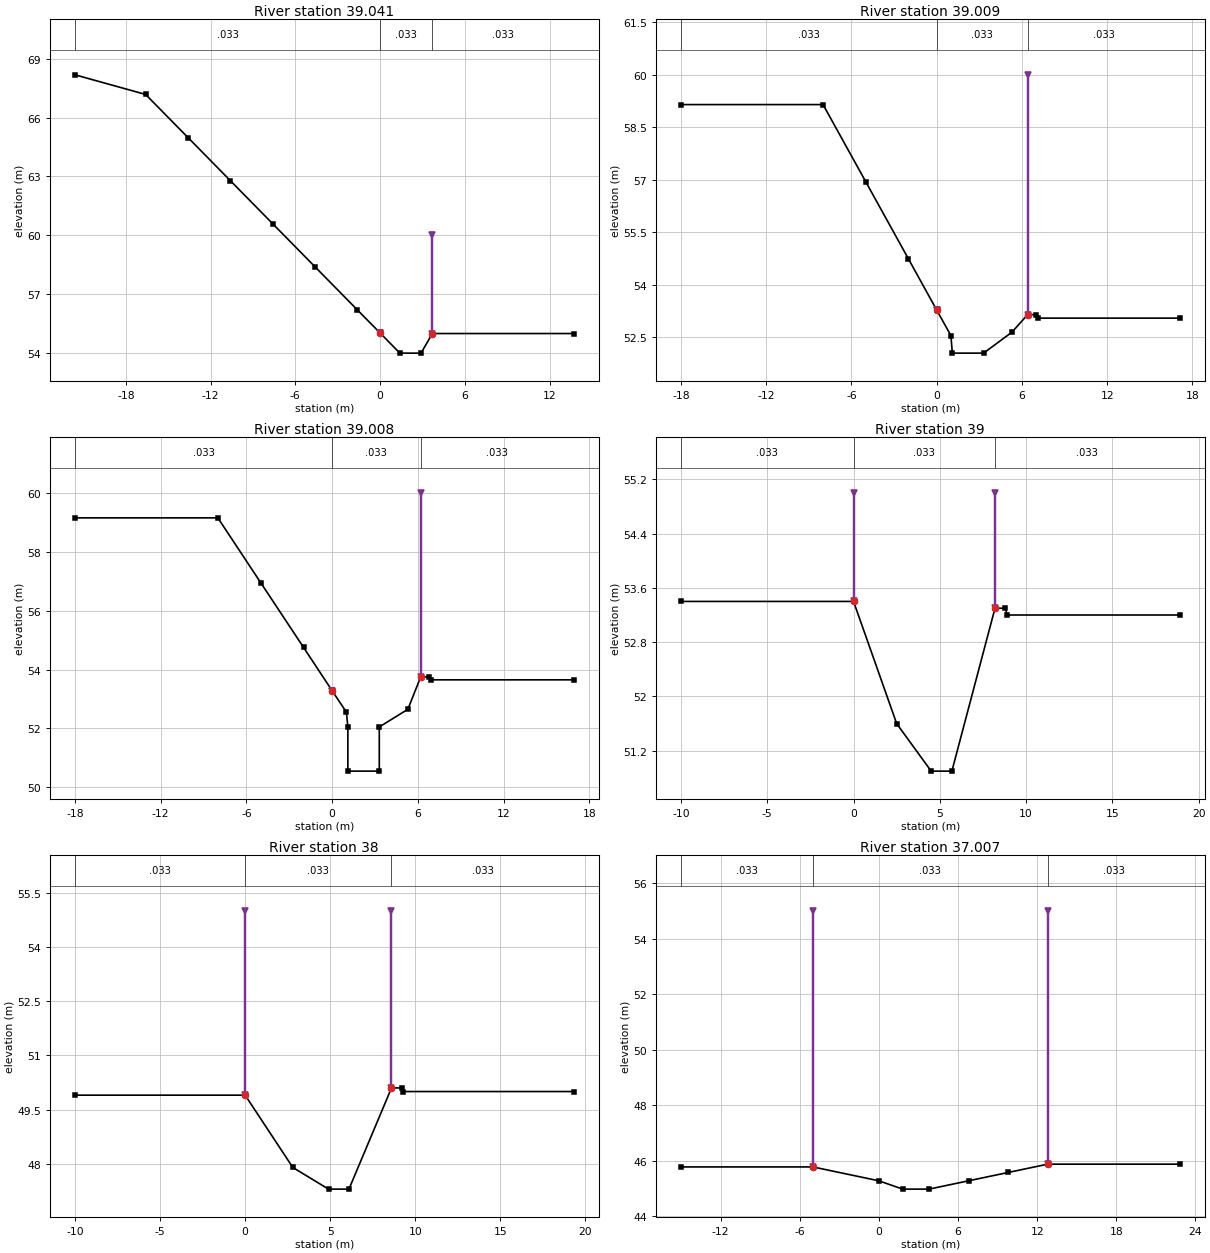
Type RM Length L Ch R = 1 ,39.041  ,32,32,32
#Sta/Elev= 12
   -21.6   68.18   -16.6   67.18   -13.6   64.98   -10.6   62.78    -7.6   60.58
    -4.6   58.38    -1.6   56.18       0   55.01     1.4   53.98     2.9   53.98
     3.7   54.98    13.7   54.98
#Mann= 3 , 0 , 0
   -21.6    .033       0       0    .033       0     3.7    .033       0
Levee=-1,0,55.01,-1,3.7,60,,
Bank Sta=0,3.7
XS Rating Curve= 0
Exp/Cntr=.3,.1

Type RM Length L Ch R = 1 ,39.009  ,1,1,1
#Sta/Elev= 13
     -18   59.15      -8   59.15      -5   56.95      -2   54.75       0   53.28
       1   52.55     1.1   52.05     3.3   52.05     5.3   52.65     6.4   53.15
       7   53.15     7.1   53.05    17.1   53.05
#Mann= 3 , 0 , 0
     -18    .033       0       0    .033       0     6.4    .033       0
Levee=-1,0,53.28,-1,6.4,60,,
Bank Sta=0,6.4
XS Rating Curve= 0
Exp/Cntr=.3,.1

Type RM Length L Ch R = 1 ,39.008  ,8,8,8
#Sta/Elev= 15
     -18   59.15      -8   59.15      -5   56.95      -2   54.75       0   53.28
       1   52.55     1.1   52.05     1.1   50.55     3.3   50.55     3.3   52.05
     5.3   52.65     6.2   53.75     6.8   53.75     6.9   53.65    16.9   53.65
#Mann= 3 , 0 , 0
     -18    .033       0       0    .033       0     6.2    .033       0
Levee=-1,0,53.28,-1,6.2,60,,
Bank Sta=0,6.2
XS Rating Curve= 0
Exp/Cntr=.3,.1

Type RM Length L Ch R = 1 ,39      ,50,50,50
#Sta/Elev= 9
     -10    53.4       0    53.4     2.5    51.6     4.5    50.9     5.7    50.9
     8.2    53.3     8.8    53.3     8.9    53.2    18.9    53.2
#Mann= 3 , 0 , 0
     -10    .033       0       0    .033       0     8.2    .033       0
Levee=-1,0,55,-1,8.2,55,,
Bank Sta=0,8.2
XS Rating Curve= 0
Exp/Cntr=.3,.1

Type RM Length L Ch R = 1 ,38      ,43,43,43
#Sta/Elev= 9
     -10    49.9       0    49.9     2.8    47.9     4.9    47.3     6.1    47.3
     8.6    50.1     9.2    50.1     9.3      50    19.3      50
#Mann= 3 , 0 , 0
     -10    .033       0       0    .033       0     8.6    .033       0
Levee=-1,0,55,-1,8.6,55,,
Bank Sta=0,8.6
XS Rating Curve= 0
Exp/Cntr=.3,.1

Type RM Length L Ch R = 1 ,37.007  ,1,1,1
#Sta/Elev= 9
     -15   45.77      -5   45.77       0   45.27     1.8   44.97     3.8   44.97
     6.8   45.27     9.8   45.57    12.8   45.87    22.8   45.87
#Mann= 3 , 0 , 0
     -15    .033       0      -5    .033       0    12.8    .033       0
Levee=-1,-5,55,-1,12.8,55,,
Bank Sta=-5,12.8
XS Rating Curve= 0
Exp/Cntr=.3,.1

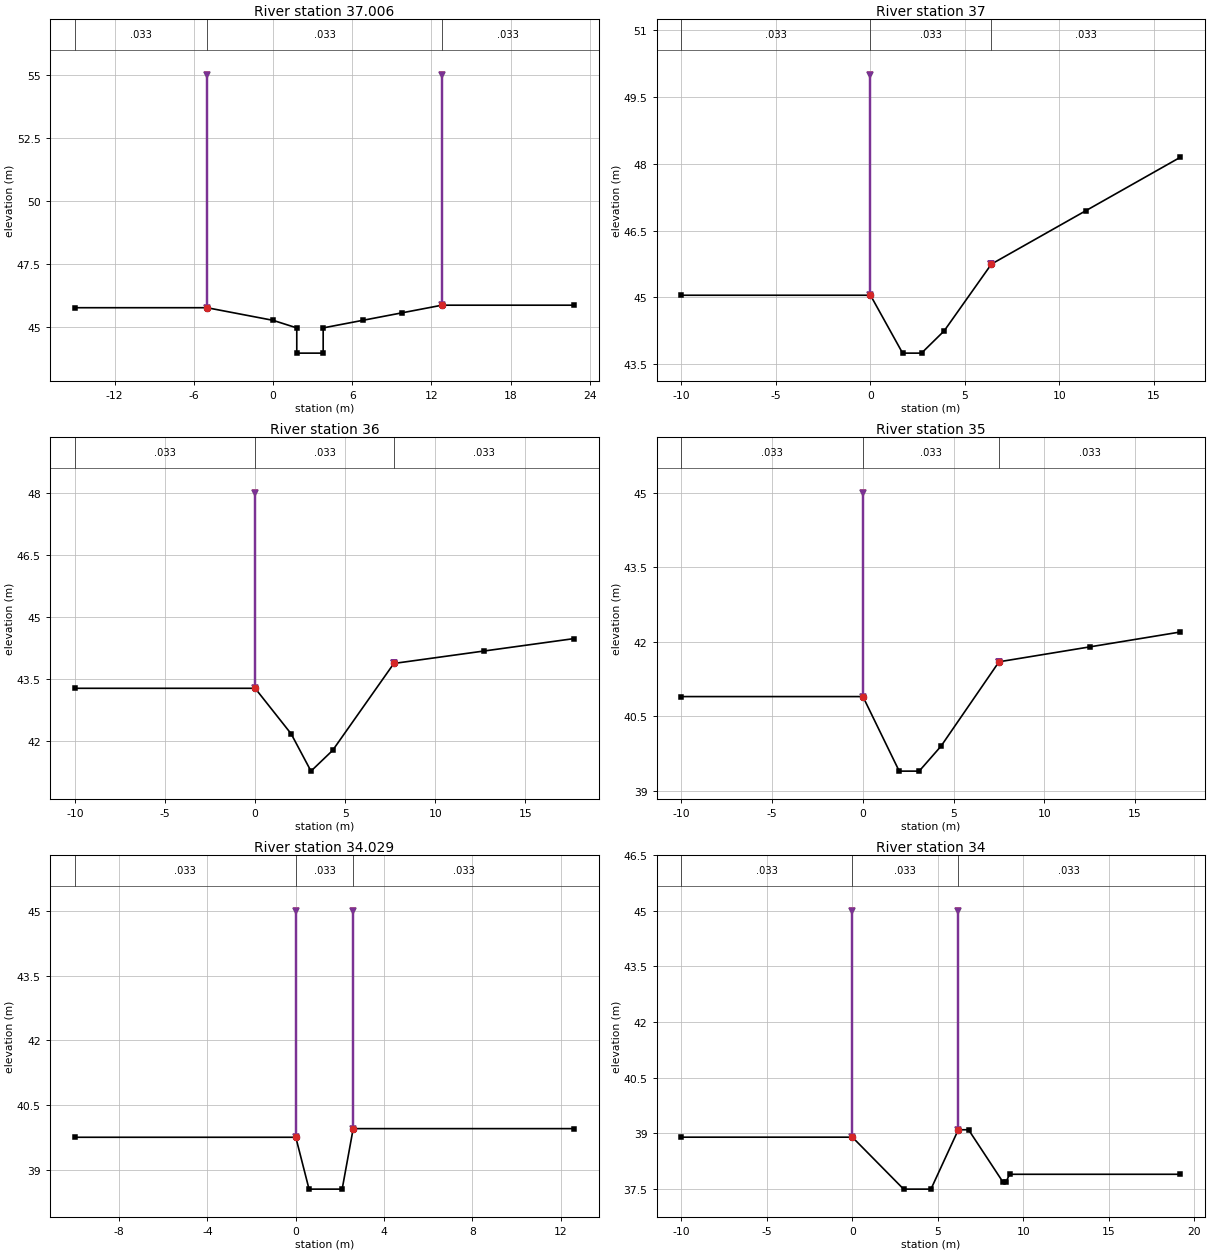
Type RM Length L Ch R = 1 ,37.006  ,6,6,6
#Sta/Elev= 11
     -15   45.77      -5   45.77       0   45.27     1.8   44.97     1.8   43.97
     3.8   43.97     3.8   44.97     6.8   45.27     9.8   45.57    12.8   45.87
    22.8   45.87
#Mann= 3 , 0 , 0
     -15    .033       0      -5    .033       0    12.8    .033       0
Levee=-1,-5,55,-1,12.8,55,,
Bank Sta=-5,12.8
XS Rating Curve= 0
Exp/Cntr=.3,.1

Type RM Length L Ch R = 1 ,37      ,50,50,50
#Sta/Elev= 8
     -10   45.05       0   45.05     1.7   43.75     2.7   43.75     3.9   44.25
     6.4   45.75    11.4   46.95    16.4   48.15
#Mann= 3 , 0 , 0
     -10    .033       0       0    .033       0     6.4    .033       0
Levee=-1,0,50,-1,6.4,45.75,,
Bank Sta=0,6.4
XS Rating Curve= 0
Exp/Cntr=.3,.1

Type RM Length L Ch R = 1 ,36      ,50,50,50
#Sta/Elev= 8
     -10   43.28       0   43.28       2   42.18     3.1   41.28     4.3   41.78
     7.7   43.88    12.7   44.18    17.7   44.48
#Mann= 3 , 0 , 0
     -10    .033       0       0    .033       0     7.7    .033       0
Levee=-1,0,48,-1,7.7,43.88,,
Bank Sta=0,7.7
XS Rating Curve= 0
Exp/Cntr=.3,.1

Type RM Length L Ch R = 1 ,35      ,21,21,21
#Sta/Elev= 8
     -10    40.9       0    40.9       2    39.4     3.1    39.4     4.3    39.9
     7.5    41.6    12.5    41.9    17.5    42.2
#Mann= 3 , 0 , 0
     -10    .033       0       0    .033       0     7.5    .033       0
Levee=-1,0,45,-1,7.5,41.6,,
Bank Sta=0,7.5
XS Rating Curve= 0
Exp/Cntr=.3,.1

Type RM Length L Ch R = 1 ,34.029  ,29,29,29
#Sta/Elev= 6
     -10   39.76       0   39.76      .6   38.56     2.1   38.56     2.6   39.96
    12.6   39.96
#Mann= 3 , 0 , 0
     -10    .033       0       0    .033       0     2.6    .033       0
Levee=-1,0,45,-1,2.6,45,,
Bank Sta=0,2.6
XS Rating Curve= 0
Exp/Cntr=.3,.1

Type RM Length L Ch R = 1 ,34      ,50,50,50
#Sta/Elev= 10
     -10    38.9       0    38.9       3    37.5     4.6    37.5     6.2    39.1
     6.8    39.1     8.8    37.7       9    37.7     9.2    37.9    19.2    37.9
#Mann= 3 , 0 , 0
     -10    .033       0       0    .033       0     6.2    .033       0
Levee=-1,0,45,-1,6.2,45,,
Bank Sta=0,6.2
XS Rating Curve= 0
Exp/Cntr=.3,.1

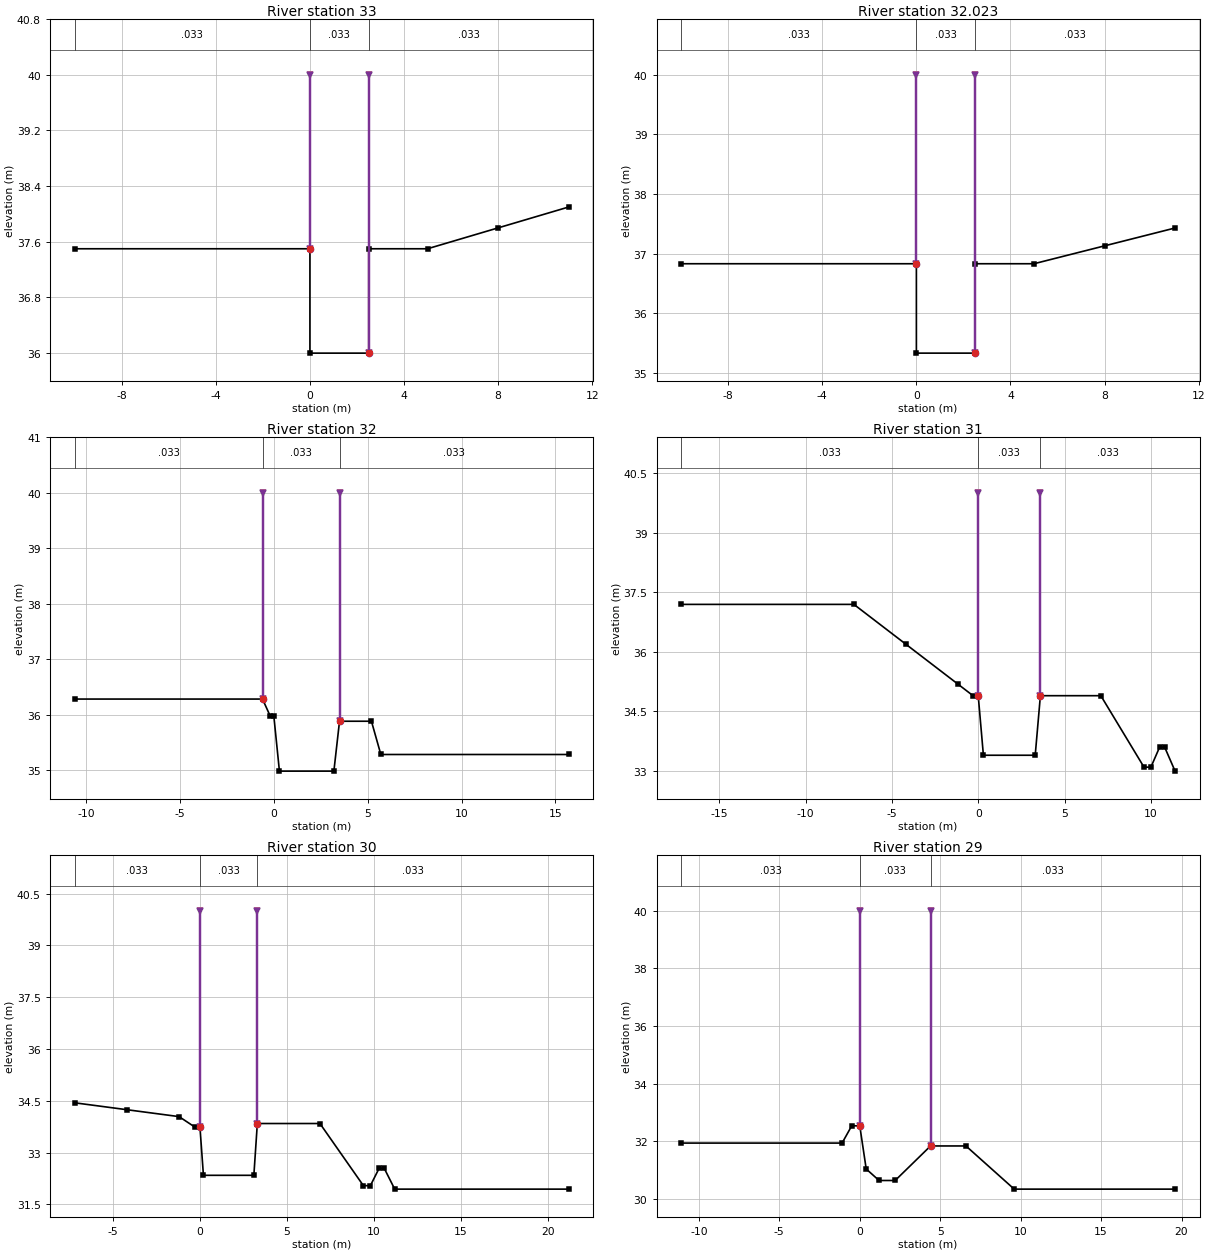
Type RM Length L Ch R = 1 ,33      ,27,27,27
#Sta/Elev= 8
     -10    37.5       0    37.5       0      36     2.5      36     2.5    37.5
       5    37.5       8    37.8      11    38.1
#Mann= 3 , 0 , 0
     -10    .033       0       0    .033       0     2.5    .033       0
Levee=-1,0,40,-1,2.5,40,,
Bank Sta=0,2.5
XS Rating Curve= 0
Exp/Cntr=.3,.1

Type RM Length L Ch R = 1 ,32.023  ,23,23,23
#Sta/Elev= 8
     -10   36.83       0   36.83       0   35.33     2.5   35.33     2.5   36.83
       5   36.83       8   37.13      11   37.43
#Mann= 3 , 0 , 0
     -10    .033       0       0    .033       0     2.5    .033       0
Levee=-1,0,40,-1,2.5,40,,
Bank Sta=0,2.5
XS Rating Curve= 0
Exp/Cntr=.3,.1

Type RM Length L Ch R = 1 ,32      ,50,50,50
#Sta/Elev= 10
   -10.6   36.28     -.6   36.28     -.2   35.98       0   35.98      .3   34.98
     3.2   34.98     3.5   35.88     5.2   35.88     5.7   35.28    15.7   35.28
#Mann= 3 , 0 , 0
   -10.6    .033       0     -.6    .033       0     3.5    .033       0
Levee=-1,-.6,40,-1,3.5,40,,
Bank Sta=-.6,3.5
XS Rating Curve= 0
Exp/Cntr=.3,.1

Type RM Length L Ch R = 1 ,31      ,50,50,50
#Sta/Elev= 15
   -17.2   37.19    -7.2   37.19    -4.2   36.19    -1.2   35.19     -.3   34.89
       0   34.89      .3   33.39     3.3   33.39     3.6   34.89     7.1   34.89
     9.6   33.09      10   33.09    10.5   33.59    10.8   33.59    11.4   32.99
#Mann= 3 , 0 , 0
   -17.2    .033       0       0    .033       0     3.6    .033       0
Levee=-1,0,40,-1,3.6,40,,
Bank Sta=0,3.6
XS Rating Curve= 0
Exp/Cntr=.3,.1

Type RM Length L Ch R = 1 ,30      ,50,50,50
#Sta/Elev= 15
    -7.2   34.44    -4.2   34.24    -1.2   34.04     -.3   33.74       0   33.74
      .2   32.34     3.1   32.34     3.3   33.84     6.9   33.84     9.4   32.04
     9.8   32.04    10.3   32.54    10.6   32.54    11.2   31.94    21.2   31.94
#Mann= 3 , 0 , 0
    -7.2    .033       0       0    .033       0     3.3    .033       0
Levee=-1,0,40,-1,3.3,40,,
Bank Sta=0,3.3
XS Rating Curve= 0
Exp/Cntr=.3,.1

Type RM Length L Ch R = 1 ,29      ,50,50,50
#Sta/Elev= 11
   -11.1   31.93    -1.1   31.93     -.5   32.53       0   32.53      .4   31.03
     1.2   30.63     2.2   30.63     4.4   31.83     6.6   31.83     9.6   30.33
    19.6   30.33
#Mann= 3 , 0 , 0
   -11.1    .033       0       0    .033       0     4.4    .033       0
Levee=-1,0,40,-1,4.4,40,,
Bank Sta=0,4.4
XS Rating Curve= 0
Exp/Cntr=.3,.1

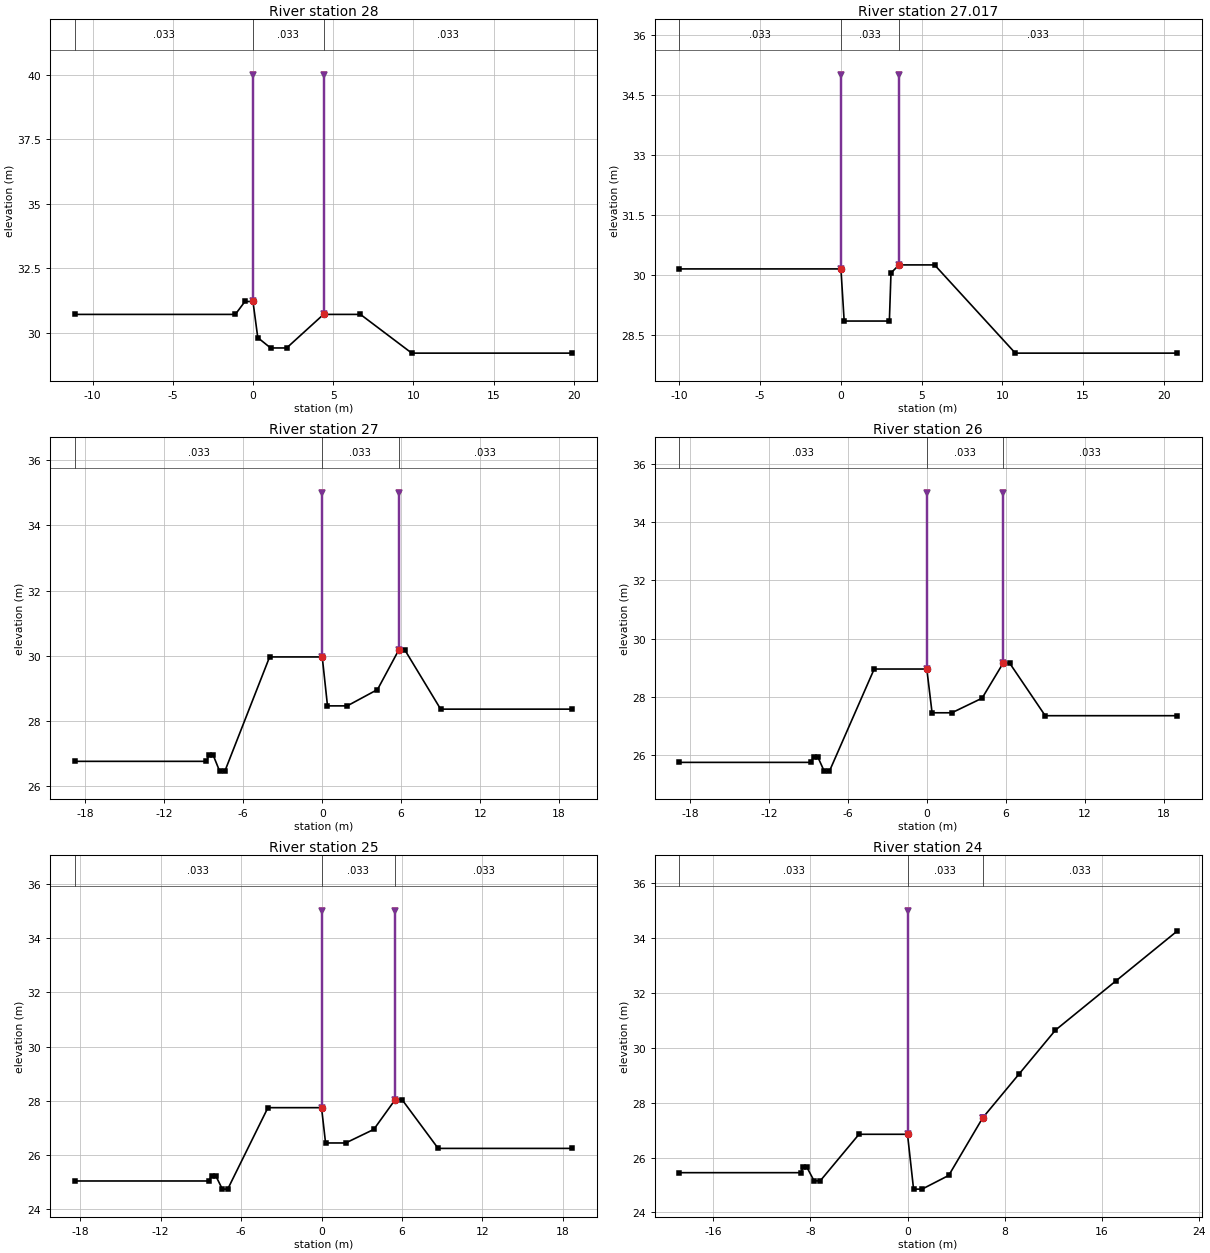
Type RM Length L Ch R = 1 ,28      ,33,33,33
#Sta/Elev= 11
   -11.1   30.72    -1.1   30.72     -.5   31.22       0   31.22      .3   29.82
     1.1   29.42     2.1   29.42     4.4   30.72     6.7   30.72     9.9   29.22
    19.9   29.22
#Mann= 3 , 0 , 0
   -11.1    .033       0       0    .033       0     4.4    .033       0
Levee=-1,0,40,-1,4.4,40,,
Bank Sta=0,4.4
XS Rating Curve= 0
Exp/Cntr=.3,.1

Type RM Length L Ch R = 1 ,27.017  ,17,17,17
#Sta/Elev= 9
     -10   30.16       0   30.16      .2   28.86       3   28.86     3.1   30.06
     3.6   30.26     5.8   30.26    10.8   28.06    20.8   28.06
#Mann= 3 , 0 , 0
     -10    .033       0       0    .033       0     3.6    .033       0
Levee=-1,0,35,-1,3.6,35,,
Bank Sta=0,3.6
XS Rating Curve= 0
Exp/Cntr=.3,.1

Type RM Length L Ch R = 1 ,27      ,50,50,50
#Sta/Elev= 15
   -18.8   26.77    -8.8   26.77    -8.6   26.97    -8.3   26.97    -7.8   26.47
    -7.4   26.47      -4   29.97       0   29.97      .4   28.47     1.9   28.47
     4.2   28.97     5.8   30.17     6.3   30.17       9   28.37      19   28.37
#Mann= 3 , 0 , 0
   -18.8    .033       0       0    .033       0     5.8    .033       0
Levee=-1,0,35,-1,5.8,35,,
Bank Sta=0,5.8
XS Rating Curve= 0
Exp/Cntr=.3,.1

Type RM Length L Ch R = 1 ,26      ,50,50,50
#Sta/Elev= 15
   -18.8   25.76    -8.8   25.76    -8.6   25.96    -8.3   25.96    -7.8   25.46
    -7.4   25.46      -4   28.96       0   28.96      .4   27.46     1.9   27.46
     4.2   27.96     5.8   29.16     6.3   29.16       9   27.36      19   27.36
#Mann= 3 , 0 , 0
   -18.8    .033       0       0    .033       0     5.8    .033       0
Levee=-1,0,35,-1,5.8,35,,
Bank Sta=0,5.8
XS Rating Curve= 0
Exp/Cntr=.3,.1

Type RM Length L Ch R = 1 ,25      ,50,50,50
#Sta/Elev= 15
   -18.4   25.05    -8.4   25.05    -8.2   25.25    -7.9   25.25    -7.4   24.75
      -7   24.75      -4   27.75       0   27.75      .3   26.45     1.8   26.45
     3.9   26.95     5.5   28.05       6   28.05     8.7   26.25    18.7   26.25
#Mann= 3 , 0 , 0
   -18.4    .033       0       0    .033       0     5.5    .033       0
Levee=-1,0,35,-1,5.5,35,,
Bank Sta=0,5.5
XS Rating Curve= 0
Exp/Cntr=.3,.1

Type RM Length L Ch R = 1 ,24      ,50,50,50
#Sta/Elev= 16
   -18.8   25.45    -8.8   25.45    -8.6   25.65    -8.3   25.65    -7.7   25.15
    -7.2   25.15      -4   26.85       0   26.85      .5   24.85     1.2   24.85
     3.4   25.35     6.2   27.45     9.2   29.05    12.2   30.65    17.2   32.45
    22.2   34.25
#Mann= 3 , 0 , 0
   -18.8    .033       0       0    .033       0     6.2    .033       0
Levee=-1,0,35,-1,6.2,27.45,,
Bank Sta=0,6.2
XS Rating Curve= 0
Exp/Cntr=.3,.1

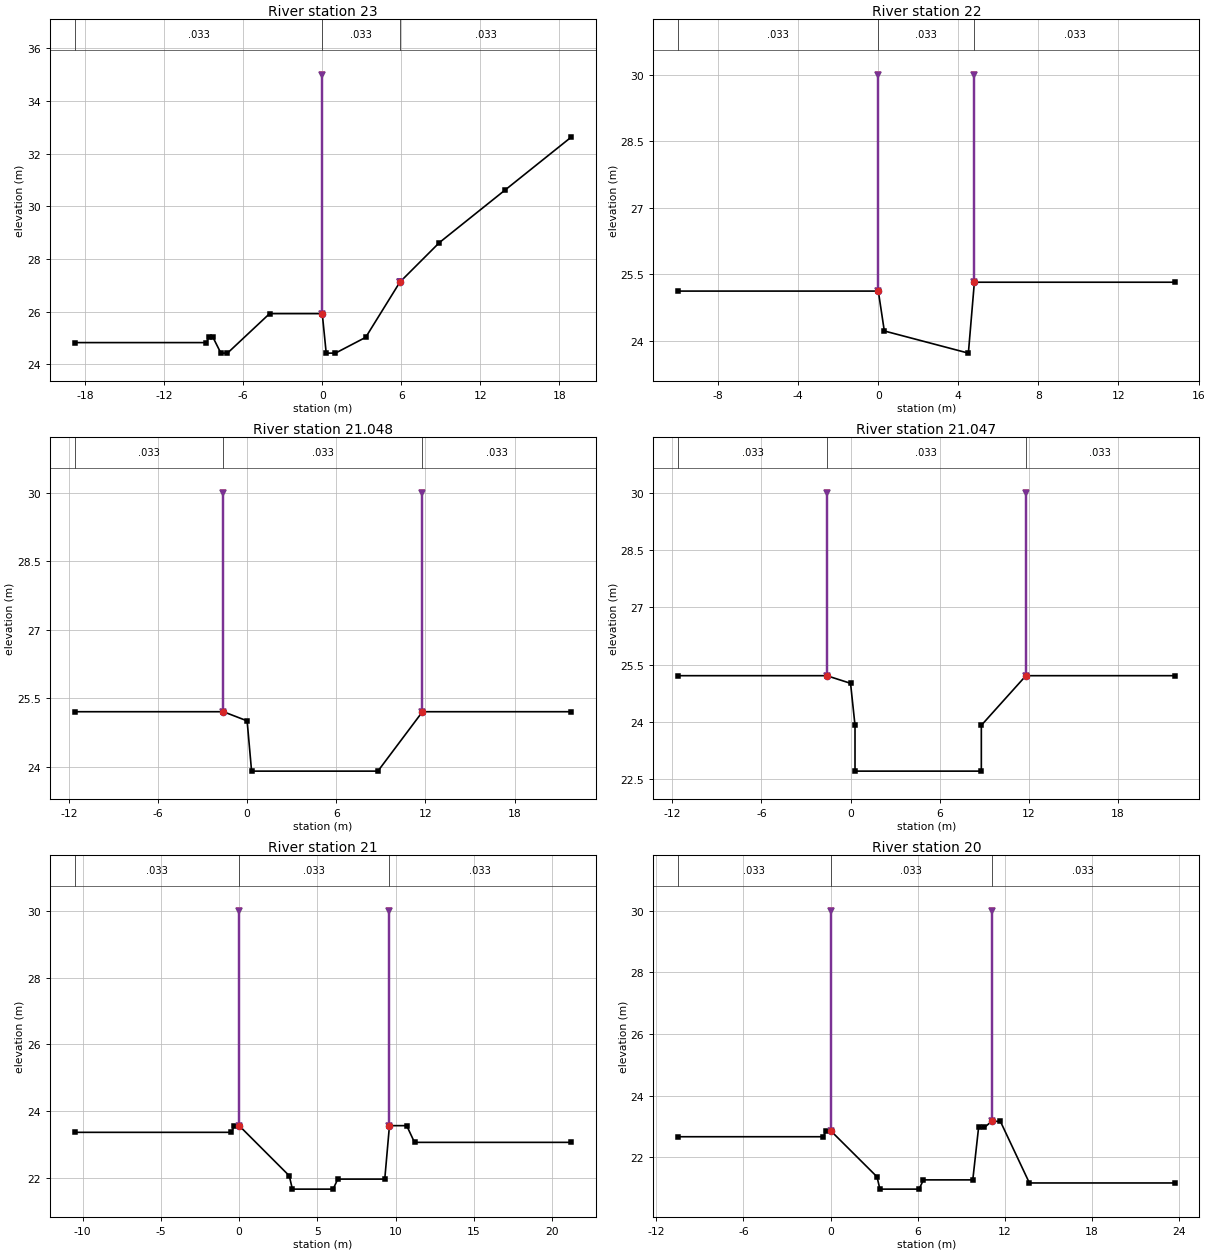
Type RM Length L Ch R = 1 ,23      ,50,50,50
#Sta/Elev= 15
   -18.8   24.83    -8.8   24.83    -8.6   25.03    -8.3   25.03    -7.7   24.43
    -7.2   24.43      -4   25.93       0   25.93      .3   24.43       1   24.43
     3.3   25.03     5.9   27.13     8.9   28.63    13.9   30.63    18.9   32.63
#Mann= 3 , 0 , 0
   -18.8    .033       0       0    .033       0     5.9    .033       0
Levee=-1,0,35,-1,5.9,27.13,,
Bank Sta=0,5.9
XS Rating Curve= 0
Exp/Cntr=.3,.1

Type RM Length L Ch R = 1 ,22      ,2,2,2
#Sta/Elev= 6
     -10   25.12       0   25.12      .3   24.22     4.5   23.72     4.8   25.32
    14.8   25.32
#Mann= 3 , 0 , 0
     -10    .033       0       0    .033       0     4.8    .033       0
Levee=-1,0,30,-1,4.8,30,,
Bank Sta=0,4.8
XS Rating Curve= 0
Exp/Cntr=.3,.1

Type RM Length L Ch R = 1 ,21.048  ,1,1,1
#Sta/Elev= 7
   -11.6   25.21    -1.6   25.21       0   25.01      .3   23.91     8.8   23.91
    11.8   25.21    21.8   25.21
#Mann= 3 , 0 , 0
   -11.6    .033       0    -1.6    .033       0    11.8    .033       0
Levee=-1,-1.6,30,-1,11.8,30,,
Bank Sta=-1.6,11.8
XS Rating Curve= 0
Exp/Cntr=.3,.1

Type RM Length L Ch R = 1 ,21.047  ,47,47,47
#Sta/Elev= 9
   -11.6   25.21    -1.6   25.21       0   25.01      .3   23.91      .3   22.71
     8.8   22.71     8.8   23.91    11.8   25.21    21.8   25.21
#Mann= 3 , 0 , 0
   -11.6    .033       0    -1.6    .033       0    11.8    .033       0
Levee=-1,-1.6,30,-1,11.8,30,,
Bank Sta=-1.6,11.8
XS Rating Curve= 0
Exp/Cntr=.3,.1

Type RM Length L Ch R = 1 ,21      ,50,50,50
#Sta/Elev= 13
   -10.5   23.37     -.5   23.37     -.3   23.57       0   23.57     3.2   22.07
     3.4   21.67       6   21.67     6.3   21.97     9.3   21.97     9.6   23.57
    10.7   23.57    11.2   23.07    21.2   23.07
#Mann= 3 , 0 , 0
   -10.5    .033       0       0    .033       0     9.6    .033       0
Levee=-1,0,30,-1,9.6,30,,
Bank Sta=0,9.6
XS Rating Curve= 0
Exp/Cntr=.3,.1

Type RM Length L Ch R = 1 ,20      ,50,50,50
#Sta/Elev= 15
   -10.5   22.67     -.5   22.67     -.3   22.87       0   22.87     3.2   21.37
     3.4   20.97     6.1   20.97     6.4   21.27     9.8   21.27    10.2   22.97
    10.6   22.97    11.1   23.17    11.7   23.17    13.7   21.17    23.7   21.17
#Mann= 3 , 0 , 0
   -10.5    .033       0       0    .033       0    11.1    .033       0
Levee=-1,0,30,-1,11.1,30,,
Bank Sta=0,11.1
XS Rating Curve= 0
Exp/Cntr=.3,.1

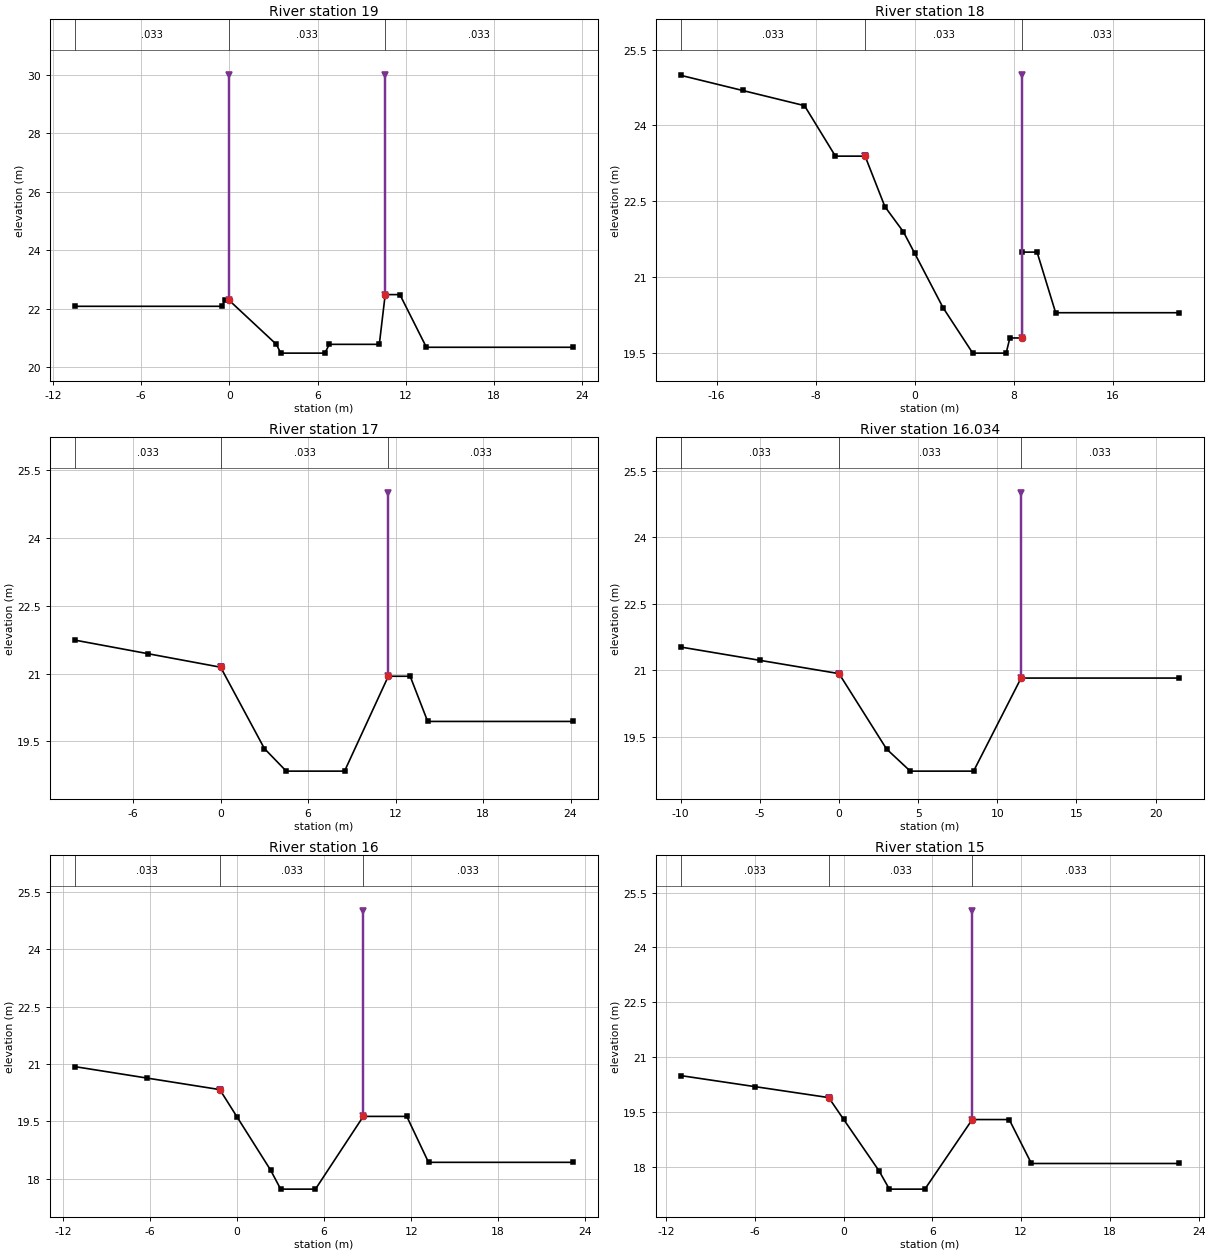
Type RM Length L Ch R = 1 ,19      ,50,50,50
#Sta/Elev= 13
   -10.5   22.09     -.5   22.09     -.3   22.29       0   22.29     3.2   20.79
     3.5   20.49     6.5   20.49     6.8   20.79    10.2   20.79    10.6   22.49
    11.6   22.49    13.4   20.69    23.4   20.69
#Mann= 3 , 0 , 0
   -10.5    .033       0       0    .033       0    10.6    .033       0
Levee=-1,0,30,-1,10.6,30,,
Bank Sta=0,10.6
XS Rating Curve= 0
Exp/Cntr=.3,.1

Type RM Length L Ch R = 1 ,18      ,50,50,50
#Sta/Elev= 17
   -18.9   24.99   -13.9   24.69    -8.9   24.39    -6.4   23.39      -4   23.39
    -2.4   22.39     -.9   21.89       0   21.47     2.3   20.39     4.7   19.49
     7.4   19.49     7.7   19.79     8.7   19.79     8.7   21.49     9.9   21.49
    11.4   20.29    21.4   20.29
#Mann= 3 , 0 , 0
   -18.9    .033       0      -4    .033       0     8.7    .033       0
Levee=-1,-4,23.39,-1,8.7,25,,
Bank Sta=-4,8.7
XS Rating Curve= 0
Exp/Cntr=.3,.1

Type RM Length L Ch R = 1 ,17      ,16,16,16
#Sta/Elev= 10
     -10   21.74      -5   21.44       0   21.14       3   19.34     4.5   18.84
     8.5   18.84    11.5   20.94      13   20.94    14.2   19.94    24.2   19.94
#Mann= 3 , 0 , 0
     -10    .033       0       0    .033       0    11.5    .033       0
Levee=-1,0,21.14,-1,11.5,25,,
Bank Sta=0,11.5
XS Rating Curve= 0
Exp/Cntr=.3,.1

Type RM Length L Ch R = 1 ,16.034  ,34,34,34
#Sta/Elev= 8
     -10   21.52      -5   21.22       0   20.92       3   19.22     4.5   18.72
     8.5   18.72    11.5   20.82    21.5   20.82
#Mann= 3 , 0 , 0
     -10    .033       0       0    .033       0    11.5    .033       0
Levee=-1,0,20.92,-1,11.5,25,,
Bank Sta=0,11.5
XS Rating Curve= 0
Exp/Cntr=.3,.1

Type RM Length L Ch R = 1 ,16      ,50,50,50
#Sta/Elev= 11
   -11.2   20.93    -6.2   20.63    -1.2   20.33       0   19.61     2.3   18.23
       3   17.73     5.4   17.73     8.7   19.63    11.7   19.63    13.2   18.43
    23.2   18.43
#Mann= 3 , 0 , 0
   -11.2    .033       0    -1.2    .033       0     8.7    .033       0
Levee=-1,-1.2,20.33,-1,8.7,25,,
Bank Sta=-1.2,8.7
XS Rating Curve= 0
Exp/Cntr=.3,.1

Type RM Length L Ch R = 1 ,15      ,50,50,50
#Sta/Elev= 11
     -11    20.5      -6    20.2      -1    19.9       0   19.31     2.4    17.9
     3.1    17.4     5.5    17.4     8.7    19.3    11.2    19.3    12.7    18.1
    22.7    18.1
#Mann= 3 , 0 , 0
     -11    .033       0      -1    .033       0     8.7    .033       0
Levee=-1,-1,19.9,-1,8.7,25,,
Bank Sta=-1,8.7
XS Rating Curve= 0
Exp/Cntr=.3,.1

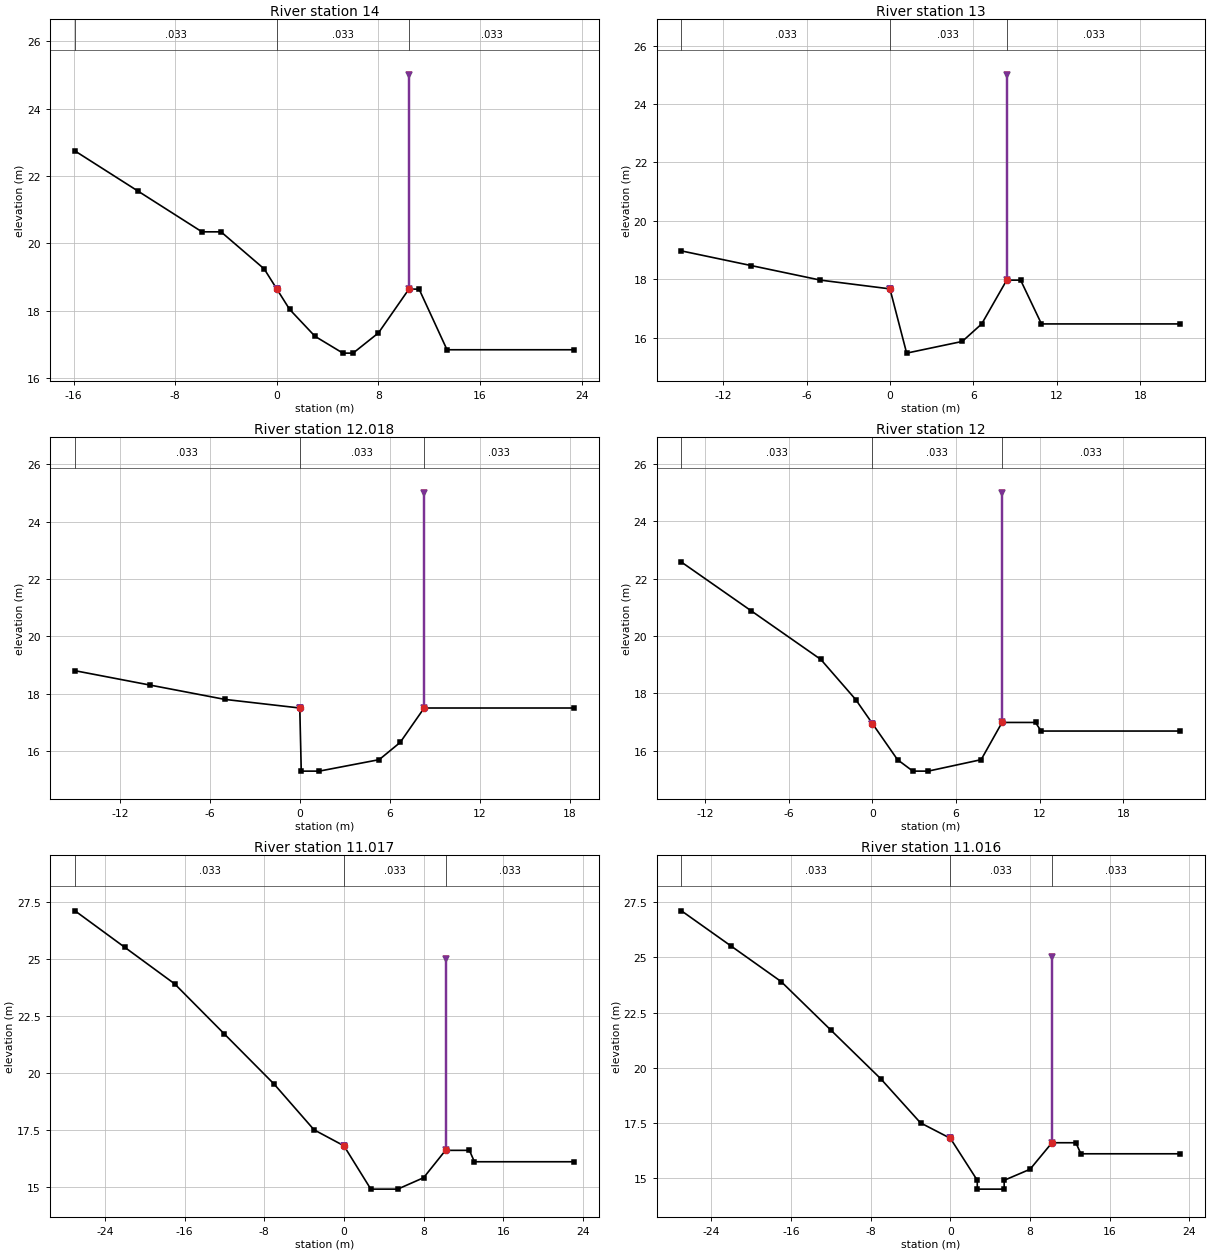
Type RM Length L Ch R = 1 ,14      ,50,50,50
#Sta/Elev= 15
   -15.9   22.74   -10.9   21.54    -5.9   20.34    -4.4   20.34      -1   19.24
       0   18.64       1   18.04       3   17.24     5.2   16.74       6   16.74
       8   17.34    10.4   18.64    11.2   18.64    13.4   16.84    23.4   16.84
#Mann= 3 , 0 , 0
   -15.9    .033       0       0    .033       0    10.4    .033       0
Levee=-1,0,18.64,-1,10.4,25,,
Bank Sta=0,10.4
XS Rating Curve= 0
Exp/Cntr=.3,.1

Type RM Length L Ch R = 1 ,13      ,32,32,32
#Sta/Elev= 11
     -15   18.97     -10   18.47      -5   17.97       0   17.67     1.2   15.47
     5.2   15.87     6.6   16.47     8.4   17.97     9.4   17.97    10.9   16.47
    20.9   16.47
#Mann= 3 , 0 , 0
     -15    .033       0       0    .033       0     8.4    .033       0
Levee=-1,0,17.67,-1,8.4,25,,
Bank Sta=0,8.4
XS Rating Curve= 0
Exp/Cntr=.3,.1

Type RM Length L Ch R = 1 ,12.018  ,18,18,18
#Sta/Elev= 10
     -15    18.8     -10    18.3      -5    17.8       0    17.5      .1    15.3
     1.3    15.3     5.3    15.7     6.7    16.3     8.3    17.5    18.3    17.5
#Mann= 3 , 0 , 0
     -15    .033       0       0    .033       0     8.3    .033       0
Levee=-1,0,17.5,-1,8.3,25,,
Bank Sta=0,8.3
XS Rating Curve= 0
Exp/Cntr=.3,.1

Type RM Length L Ch R = 1 ,12      ,33,33,33
#Sta/Elev= 13
   -13.7   22.58    -8.7   20.88    -3.7   19.18    -1.2   17.78       0   16.94
     1.8   15.68     2.9   15.28       4   15.28     7.8   15.68     9.3   16.98
    11.7   16.98    12.1   16.68    22.1   16.68
#Mann= 3 , 0 , 0
   -13.7    .033       0       0    .033       0     9.3    .033       0
Levee=-1,0,16.94,-1,9.3,25,,
Bank Sta=0,9.3
XS Rating Curve= 0
Exp/Cntr=.3,.1

Type RM Length L Ch R = 1 ,11.017  ,1,1,1
#Sta/Elev= 14
     -27   27.11     -22   25.51     -17   23.91     -12   21.71      -7   19.51
      -3   17.51       0   16.81     2.7   14.91     5.4   14.91       8   15.41
    10.2   16.61    12.6   16.61    13.1   16.11    23.1   16.11
#Mann= 3 , 0 , 0
     -27    .033       0       0    .033       0    10.2    .033       0
Levee=-1,0,16.81,-1,10.2,25,,
Bank Sta=0,10.2
XS Rating Curve= 0
Exp/Cntr=.3,.1

Type RM Length L Ch R = 1 ,11.016  ,16,16,16
#Sta/Elev= 16
     -27   27.11     -22   25.51     -17   23.91     -12   21.71      -7   19.51
      -3   17.51       0   16.81     2.7   14.91     2.7   14.51     5.4   14.51
     5.4   14.91       8   15.41    10.2   16.61    12.6   16.61    13.1   16.11
    23.1   16.11
#Mann= 3 , 0 , 0
     -27    .033       0       0    .033       0    10.2    .033       0
Levee=-1,0,16.81,-1,10.2,25,,
Bank Sta=0,10.2
XS Rating Curve= 0
Exp/Cntr=.3,.1

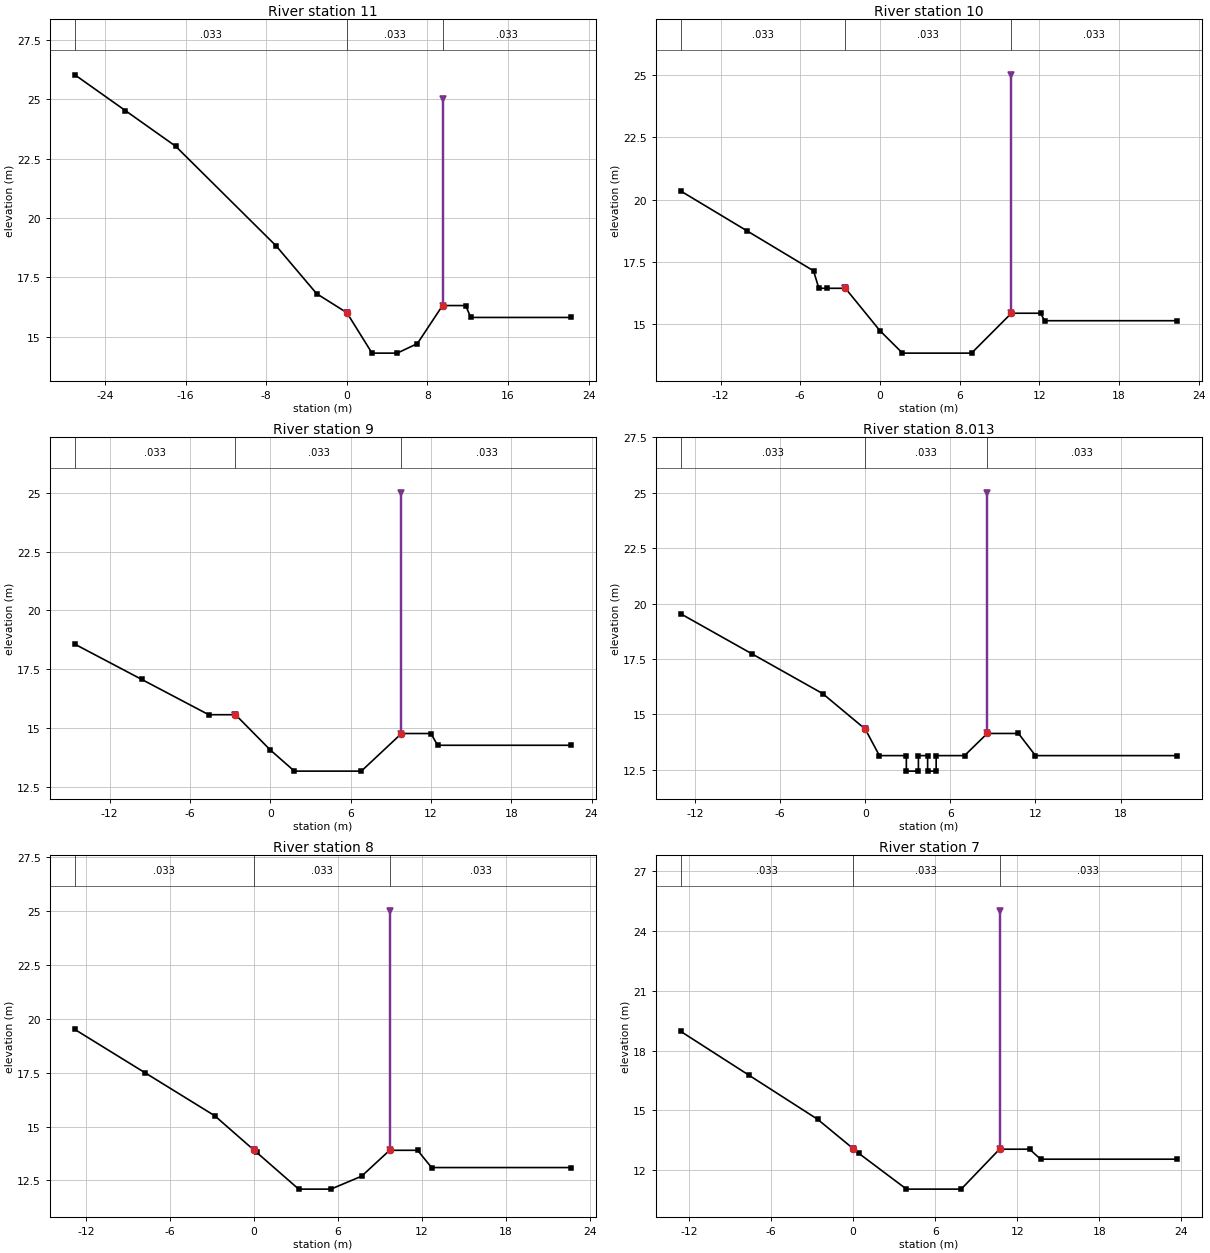
Type RM Length L Ch R = 1 ,11      ,50,50,50
#Sta/Elev= 13
     -27   26.02     -22   24.52     -17   23.02      -7   18.82      -3   16.82
       0   16.02     2.5   14.32       5   14.32       7   14.72     9.5   16.32
    11.8   16.32    12.3   15.82    22.3   15.82
#Mann= 3 , 0 , 0
     -27    .033       0       0    .033       0     9.5    .033       0
Levee=-1,0,16.02,-1,9.5,25,,
Bank Sta=0,9.5
XS Rating Curve= 0
Exp/Cntr=.3,.1

Type RM Length L Ch R = 1 ,10      ,50,50,50
#Sta/Elev= 13
     -15   20.34     -10   18.74      -5   17.14    -4.6   16.44   -3.95   16.44
    -2.6   16.44       0   14.74     1.7   13.84     6.9   13.84     9.9   15.44
    12.1   15.44    12.4   15.14    22.4   15.14
#Mann= 3 , 0 , 0
     -15    .033       0    -2.6    .033       0     9.9    .033       0
Levee=-1,-2.6,16.44,-1,9.9,25,,
Bank Sta=-2.6,9.9
XS Rating Curve= 0
Exp/Cntr=.3,.1

Type RM Length L Ch R = 1 ,9       ,37,37,37
#Sta/Elev= 11
   -14.6   18.56    -9.6   17.06    -4.6   15.56    -2.6   15.56       0   14.06
     1.8   13.16     6.8   13.16     9.8   14.76      12   14.76    12.5   14.26
    22.5   14.26
#Mann= 3 , 0 , 0
   -14.6    .033       0    -2.6    .033       0     9.8    .033       0
Levee=-1,-2.6,15.56,-1,9.8,25,,
Bank Sta=-2.6,9.8
XS Rating Curve= 0
Exp/Cntr=.3,.1

Type RM Length L Ch R = 1 ,8.013   ,13,13,13
#Sta/Elev= 18
     -13   19.54      -8   17.74      -3   15.94       0   14.34       1   13.14
     2.9   13.14     2.9   12.44    3.75   12.44    3.75   13.14     4.4   13.14
     4.4   12.44       5   12.44       5   13.14       7   13.14     8.6   14.14
    10.8   14.14      12   13.14      22   13.14
#Mann= 3 , 0 , 0
     -13    .033       0       0    .033       0     8.6    .033       0
Levee=-1,0,14.34,-1,8.6,25,,
Bank Sta=0,8.6
XS Rating Curve= 0
Exp/Cntr=.3,.1

Type RM Length L Ch R = 1 ,8       ,50,50,50
#Sta/Elev= 12
   -12.8    19.5    -7.8    17.5    -2.8    15.5       0   13.91      .2    13.8
     3.2    12.1     5.5    12.1     7.7    12.7     9.7    13.9    11.7    13.9
    12.7    13.1    22.7    13.1
#Mann= 3 , 0 , 0
   -12.8    .033       0       0    .033       0     9.7    .033       0
Levee=-1,0,13.91,-1,9.7,25,,
Bank Sta=0,9.7
XS Rating Curve= 0
Exp/Cntr=.3,.1

Type RM Length L Ch R = 1 ,7       ,50,50,50
#Sta/Elev= 11
   -12.6   18.96    -7.6   16.76    -2.6   14.56       0   13.09      .4   12.86
     3.9   11.06     7.9   11.06    10.7   13.06    12.9   13.06    13.7   12.56
    23.7   12.56
#Mann= 3 , 0 , 0
   -12.6    .033       0       0    .033       0    10.7    .033       0
Levee=-1,0,13.09,-1,10.7,25,,
Bank Sta=0,10.7
XS Rating Curve= 0
Exp/Cntr=.3,.1