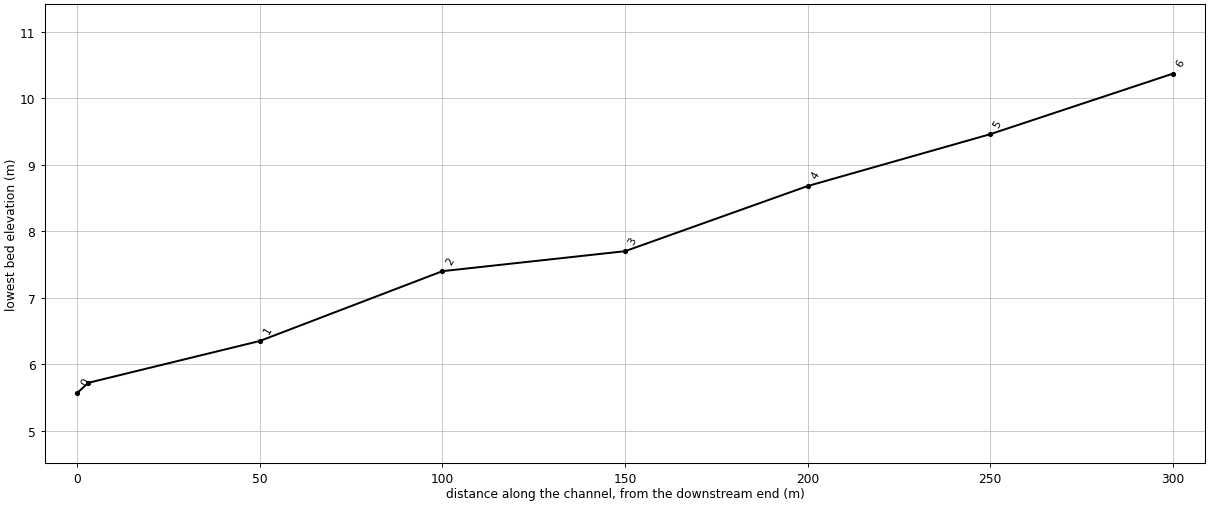
HEC-RAS study ODC.prj: ODONG

--- ODC.g01 (geometry) --- (continued)

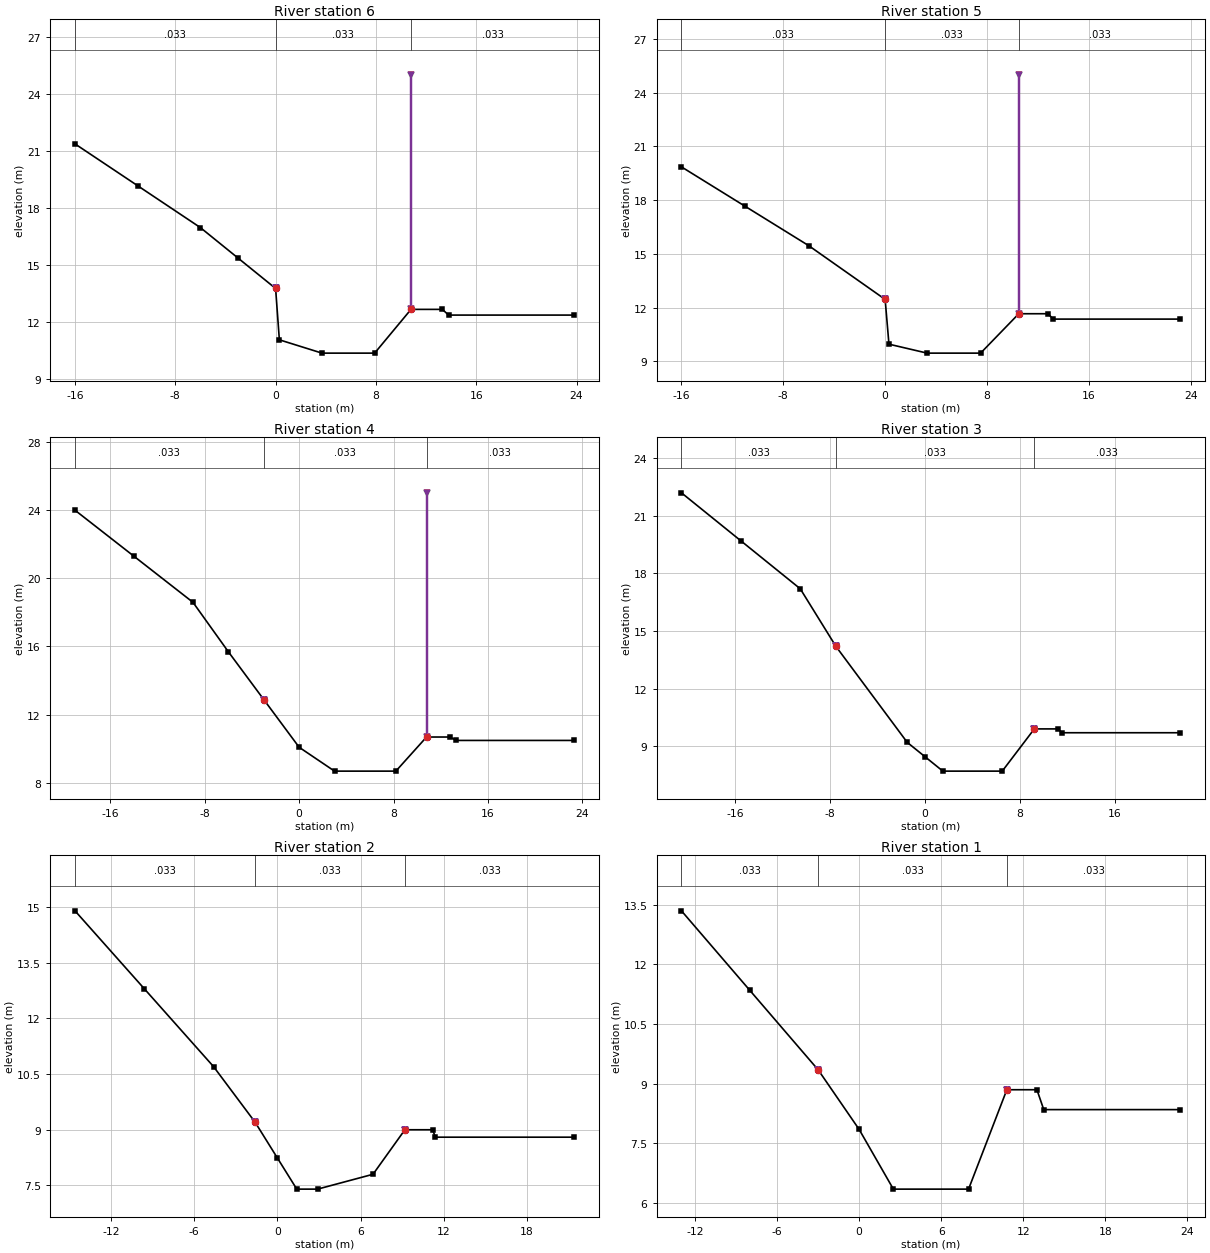
Type RM Length L Ch R = 1 ,6       ,50,50,50
#Sta/Elev= 12
     -16   21.37     -11   19.17      -6   16.97      -3   15.37       0   13.77
      .3   11.07     3.7   10.37     7.9   10.37    10.8   12.67    13.3   12.67
    13.8   12.37    23.8   12.37
#Mann= 3 , 0 , 0
     -16    .033       0       0    .033       0    10.8    .033       0
Levee=-1,0,13.77,-1,10.8,25,,
Bank Sta=0,10.8
XS Rating Curve= 0
Exp/Cntr=.3,.1

Type RM Length L Ch R = 1 ,5       ,50,50,50
#Sta/Elev= 11
     -16   19.86     -11   17.66      -6   15.46       0   12.46      .3    9.96
     3.3    9.46     7.5    9.46    10.5   11.66    12.8   11.66    13.2   11.36
    23.2   11.36
#Mann= 3 , 0 , 0
     -16    .033       0       0    .033       0    10.5    .033       0
Levee=-1,0,12.46,-1,10.5,25,,
Bank Sta=0,10.5
XS Rating Curve= 0
Exp/Cntr=.3,.1

Type RM Length L Ch R = 1 ,4       ,50,50,50
#Sta/Elev= 12
     -19   23.98     -14   21.28      -9   18.58      -6   15.68      -3   12.88
       0   10.08       3    8.68     8.2    8.68    10.8   10.68    12.8   10.68
    13.3   10.48    23.3   10.48
#Mann= 3 , 0 , 0
     -19    .033       0      -3    .033       0    10.8    .033       0
Levee=-1,-3,12.88,-1,10.8,25,,
Bank Sta=-3,10.8
XS Rating Curve= 0
Exp/Cntr=.3,.1

Type RM Length L Ch R = 1 ,3       ,50,50,50
#Sta/Elev= 12
   -20.5    22.2   -15.5    19.7   -10.5    17.2    -7.5    14.2    -1.5     9.2
       0    8.45     1.5     7.7     6.5     7.7     9.2     9.9    11.2     9.9
    11.5     9.7    21.5     9.7
#Mann= 3 , 0 , 0
   -20.5    .033       0    -7.5    .033       0     9.2    .033       0
Levee=-1,-7.5,14.2,-1,9.2,9.9,,
Bank Sta=-7.5,9.2
XS Rating Curve= 0
Exp/Cntr=.3,.1

Type RM Length L Ch R = 1 ,2       ,50,50,50
#Sta/Elev= 12
   -14.6    14.9    -9.6    12.8    -4.6    10.7    -1.6     9.2       0    8.24
     1.4     7.4     2.9     7.4     6.9     7.8     9.2       9    11.2       9
    11.4     8.8    21.4     8.8
#Mann= 3 , 0 , 0
   -14.6    .033       0    -1.6    .033       0     9.2    .033       0
Levee=-1,-1.6,9.2,-1,9.2,9,,
Bank Sta=-1.6,9.2
XS Rating Curve= 0
Exp/Cntr=.3,.1

Type RM Length L Ch R = 1 ,1       ,47,47,47
#Sta/Elev= 10
     -13   13.35      -8   11.35      -3    9.35       0    7.85     2.5    6.35
       8    6.35    10.8    8.85      13    8.85    13.5    8.35    23.5    8.35
#Mann= 3 , 0 , 0
     -13    .033       0      -3    .033       0    10.8    .033       0
Levee=-1,-3,9.35,-1,10.8,8.85,,
Bank Sta=-3,10.8
XS Rating Curve= 0
Exp/Cntr=.3,.1

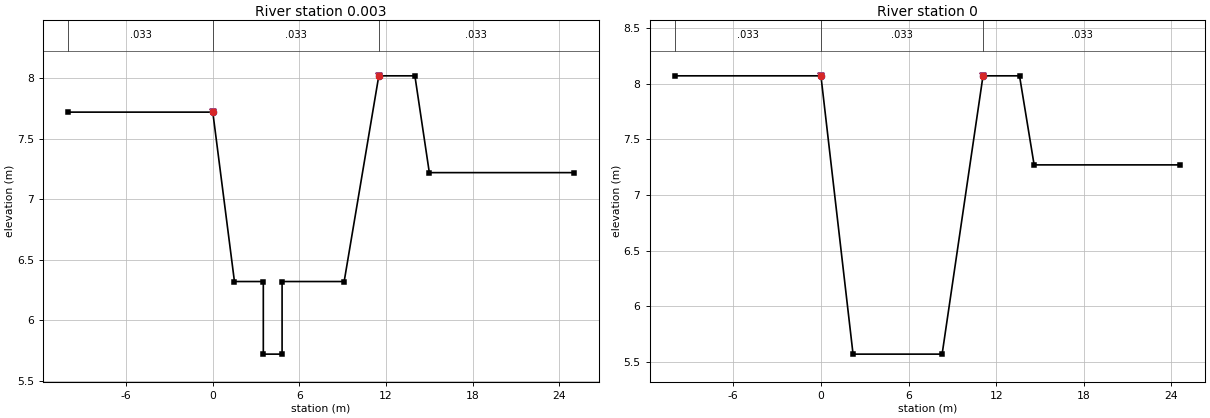
Type RM Length L Ch R = 1 ,0.003   ,3,3,3
#Sta/Elev= 12
     -10    7.72       0    7.72     1.5    6.32     3.5    6.32     3.5    5.72
     4.8    5.72     4.8    6.32     9.1    6.32    11.5    8.02      14    8.02
      15    7.22      25    7.22
#Mann= 3 , 0 , 0
     -10    .033       0       0    .033       0    11.5    .033       0
Levee=-1,0,7.72,-1,11.5,8.02,,
Bank Sta=0,11.5
XS Rating Curve= 0
Exp/Cntr=.3,.1

Type RM Length L Ch R = 1 ,0       ,0,0,0
#Sta/Elev= 8
     -10    8.07       0    8.07     2.2    5.57     8.3    5.57    11.1    8.07
    13.6    8.07    14.6    7.27    24.6    7.27
#Mann= 3 , 0 , 0
     -10    .033       0       0    .033       0    11.1    .033       0
Levee=-1,0,8.07,-1,11.1,8.07,,
Bank Sta=0,11.1
XS Rating Curve= 0
Exp/Cntr=.3,.1

Chan Stop Cuts=-1