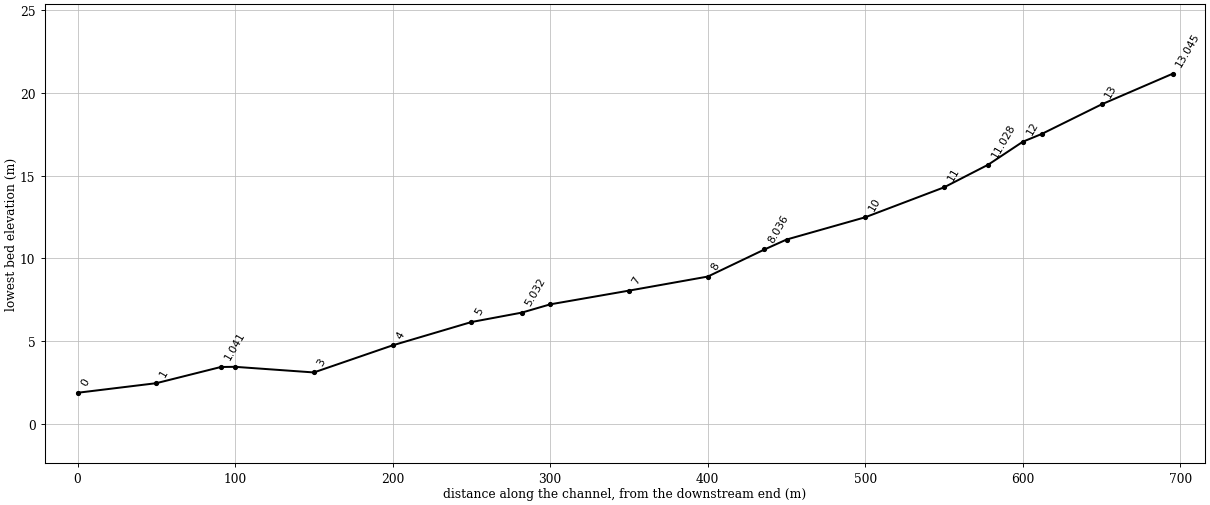
--- MMC.prj (project) ---

Proj Title=MAIMI
Current Plan=p01
Default Exp/Contr=.3,.1
SI Units
Geom File=g01
Flow File=f01
Plan File=p01
Y Axis Title=Elevation
X Axis Title(PF)=Main Channel Distance
X Axis Title(XS)=Station
BEGIN DESCRIPTION:
           BACK WATER COMPUTATION
      APPLICATION OF HEC-2 BY Samju Construction Engineering
      MAEMI-STREEM : 30 YR
END DESCRIPTION:
DSS Export Rating Curves= 0
DSS Export Rating Curve Sorted= 0
DSS Export Volume Flow Curves= 0
DXF OffsetX= 0
DXF OffsetY= 0
DXF ScaleX= 1
DXF ScaleY= 10

--- MMC.p01 (plan) ---

Plan Title=Imported Plan 01
Version=Version 3.0.1  Mar 2001
Short Identifier=Imported Pla
Geom File=g01
Flow File=f01
Subcritical Flow
K Sum by GR= 0
Std Step Tol= 0.003
Critical Tol= 0.003
Num of Std Step Trials= 20
Max Error Tol= 0.1
Flow Tol Ratio= 0.001
Split Flow NTrial= 30
Split Flow Tol= 0.02
Split Flow Ratio= 0.02
Log Output Level= 0
Friction Slope Method= 1
Unsteady Friction Slope Method= 2
Parabolic Critical Depth
Global Vel Dist= 0 , 0 , 0
Global Log Level= 0
CheckData=True
Encroach Param=-1 ,0,0, 0
Computation Interval=1HOUR
Output Interval=1HOUR
Run HTab= 0
Run UNet= 0
Run PostProcess= 0
UNET Theta= 1
UNET ZTol= 0.02
UNET ZSATol= 0.1
UNET MxIter= 20
UNET MaxInSteps= 20
UNET DtIC= 0
UNET DtMin= 0
UNET MaxCRTS= 20
UNET WFStab= 2
UNET SFStab= 1
UNET WFX= 1
UNET SFX= 1
UNET Convert EG Bridges=-1
UNET Use Existing IB Tables=-1
Instantaneous Interval=1HOUR
Write IC File= 0
Write Velocity= 0
Write Detailed= 0

--- MMC.f01 (steady flow) ---

Flow Title=Imported Flow 01
Version=Version 3.0.1  Mar 2001
Number of Profiles= 5
Profile Names=10YR,20YR,30YR,50YR,80YR
River Rch & RM=RIVER-1,Reach-1         ,13.045
   16.06    17.7   18.65   19.85   20.96
River Rch & RM=MAEMI,MAEMI           ,13.045
   16.06    17.7   18.65   19.85   20.96
Boundary for River Rch & Prof#=MAEMI,MAEMI           , 1
Up Type= 0
Dn Type= 3
Dn Slope=.029
Boundary for River Rch & Prof#=MAEMI,MAEMI           , 2
Up Type= 0
Dn Type= 3
Dn Slope=.029
Boundary for River Rch & Prof#=MAEMI,MAEMI           , 3
Up Type= 0
Dn Type= 3
Dn Slope=.029
Boundary for River Rch & Prof#=MAEMI,MAEMI           , 4
Up Type= 0
Dn Type= 3
Dn Slope=.029
Boundary for River Rch & Prof#=MAEMI,MAEMI           , 5
Up Type= 0
Dn Type= 3
Dn Slope=.029
DSS Import GetInterval= 0
DSS Import GetPeak= 0
DSS Import FillOption= 0

--- MMC.g01 (geometry) ---

Geom Title=Imported Geom 01
Version=Version 3.0.1  Mar 2001

River Reach=MAEMI           ,MAEMI
Reach XY= 2
              .5             .95              .5             .05

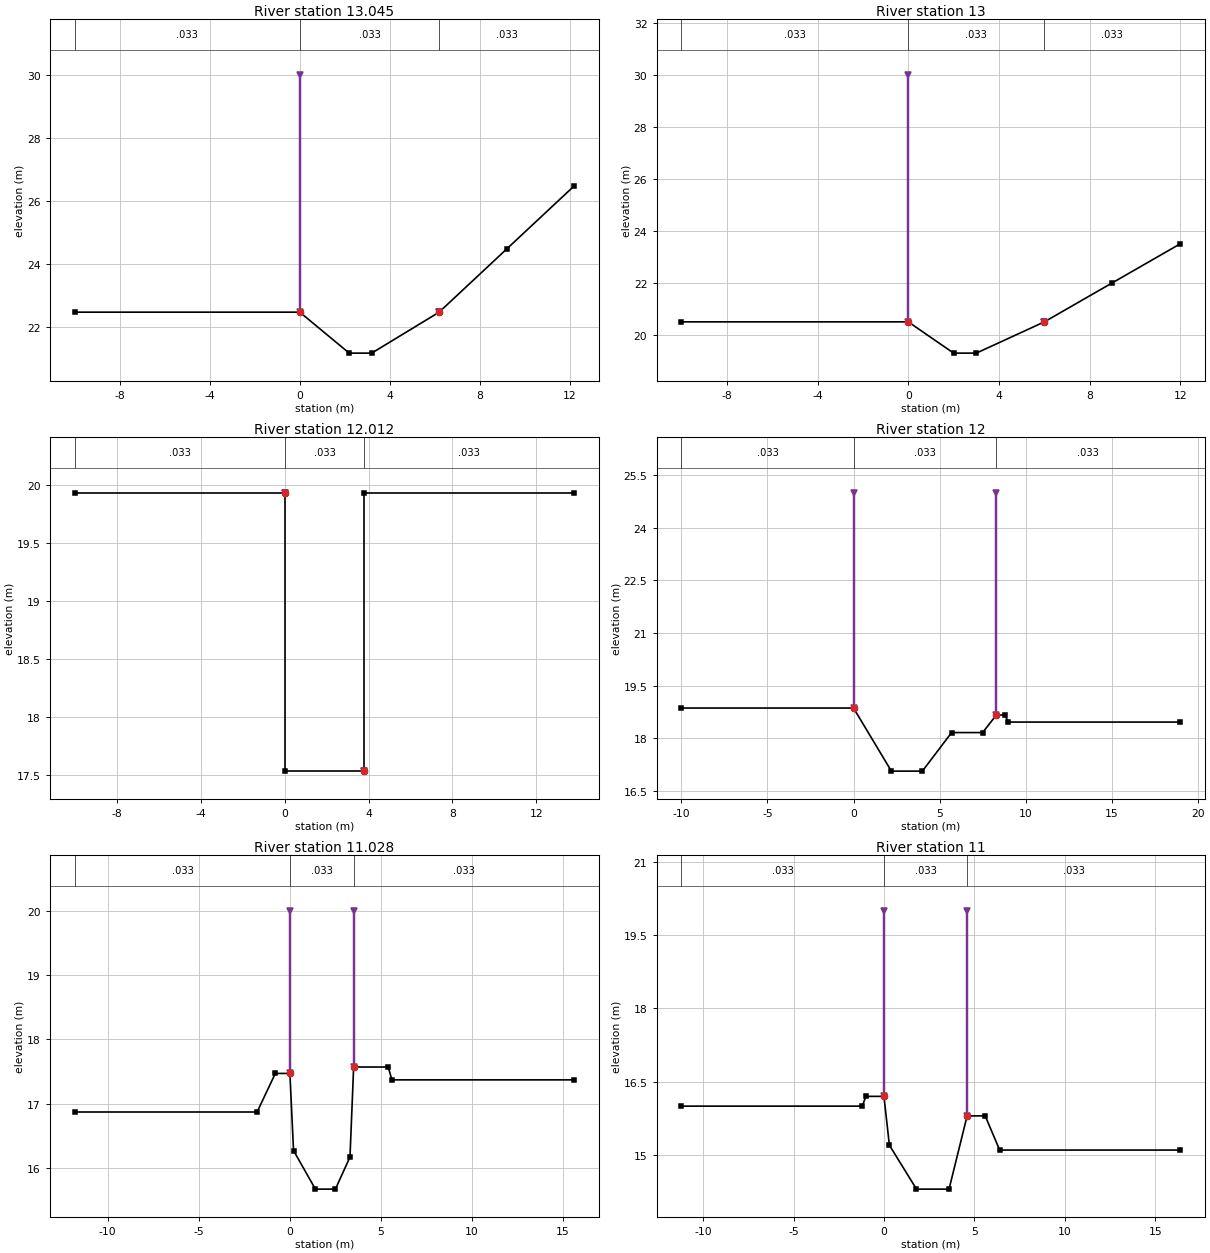
Type RM Length L Ch R = 1 ,13.045  ,45,45,45
#Sta/Elev= 7
     -10   22.47       0   22.47     2.2   21.17     3.2   21.17     6.2   22.47
     9.2   24.47    12.2   26.47
#Mann= 3 , 0 , 0
     -10    .033       0       0    .033       0     6.2    .033       0
Levee=-1,0,30,-1,6.2,22.47,,
Bank Sta=0,6.2
XS Rating Curve= 0
Exp/Cntr=.3,.1

Type RM Length L Ch R = 1 ,13      ,38,38,38
#Sta/Elev= 7
     -10   20.52       0   20.52       2   19.32       3   19.32       6   20.52
       9   22.02      12   23.52
#Mann= 3 , 0 , 0
     -10    .033       0       0    .033       0       6    .033       0
Levee=-1,0,30,-1,6,20.52,,
Bank Sta=0,6
XS Rating Curve= 0
Exp/Cntr=.3,.1

Type RM Length L Ch R = 1 ,12.012  ,12,12,12
#Sta/Elev= 6
     -10   19.93       0   19.93       0   17.53     3.8   17.53     3.8   19.93
    13.8   19.93
#Mann= 3 , 0 , 0
     -10    .033       0       0    .033       0     3.8    .033       0
Levee=-1,0,19.93,-1,3.8,17.53,,
Bank Sta=0,3.8
XS Rating Curve= 0
Exp/Cntr=.3,.1

Type RM Length L Ch R = 1 ,12      ,22,22,22
#Sta/Elev= 10
     -10   18.86       0   18.86     2.2   17.06       4   17.06     5.7   18.16
     7.5   18.16     8.3   18.66     8.8   18.66       9   18.46      19   18.46
#Mann= 3 , 0 , 0
     -10    .033       0       0    .033       0     8.3    .033       0
Levee=-1,0,25,-1,8.3,25,,
Bank Sta=0,8.3
XS Rating Curve= 0
Exp/Cntr=.3,.1

Type RM Length L Ch R = 1 ,11.028  ,28,28,28
#Sta/Elev= 12
   -11.8   16.87    -1.8   16.87     -.8   17.47       0   17.47      .2   16.27
     1.4   15.67     2.5   15.67     3.3   16.17     3.5   17.57     5.4   17.57
     5.6   17.37    15.6   17.37
#Mann= 3 , 0 , 0
   -11.8    .033       0       0    .033       0     3.5    .033       0
Levee=-1,0,20,-1,3.5,20,,
Bank Sta=0,3.5
XS Rating Curve= 0
Exp/Cntr=.3,.1

Type RM Length L Ch R = 1 ,11      ,50,50,50
#Sta/Elev= 11
   -11.2      16    -1.2      16      -1    16.2       0    16.2      .3    15.2
     1.8    14.3     3.6    14.3     4.6    15.8     5.6    15.8     6.4    15.1
    16.4    15.1
#Mann= 3 , 0 , 0
   -11.2    .033       0       0    .033       0     4.6    .033       0
Levee=-1,0,20,-1,4.6,20,,
Bank Sta=0,4.6
XS Rating Curve= 0
Exp/Cntr=.3,.1

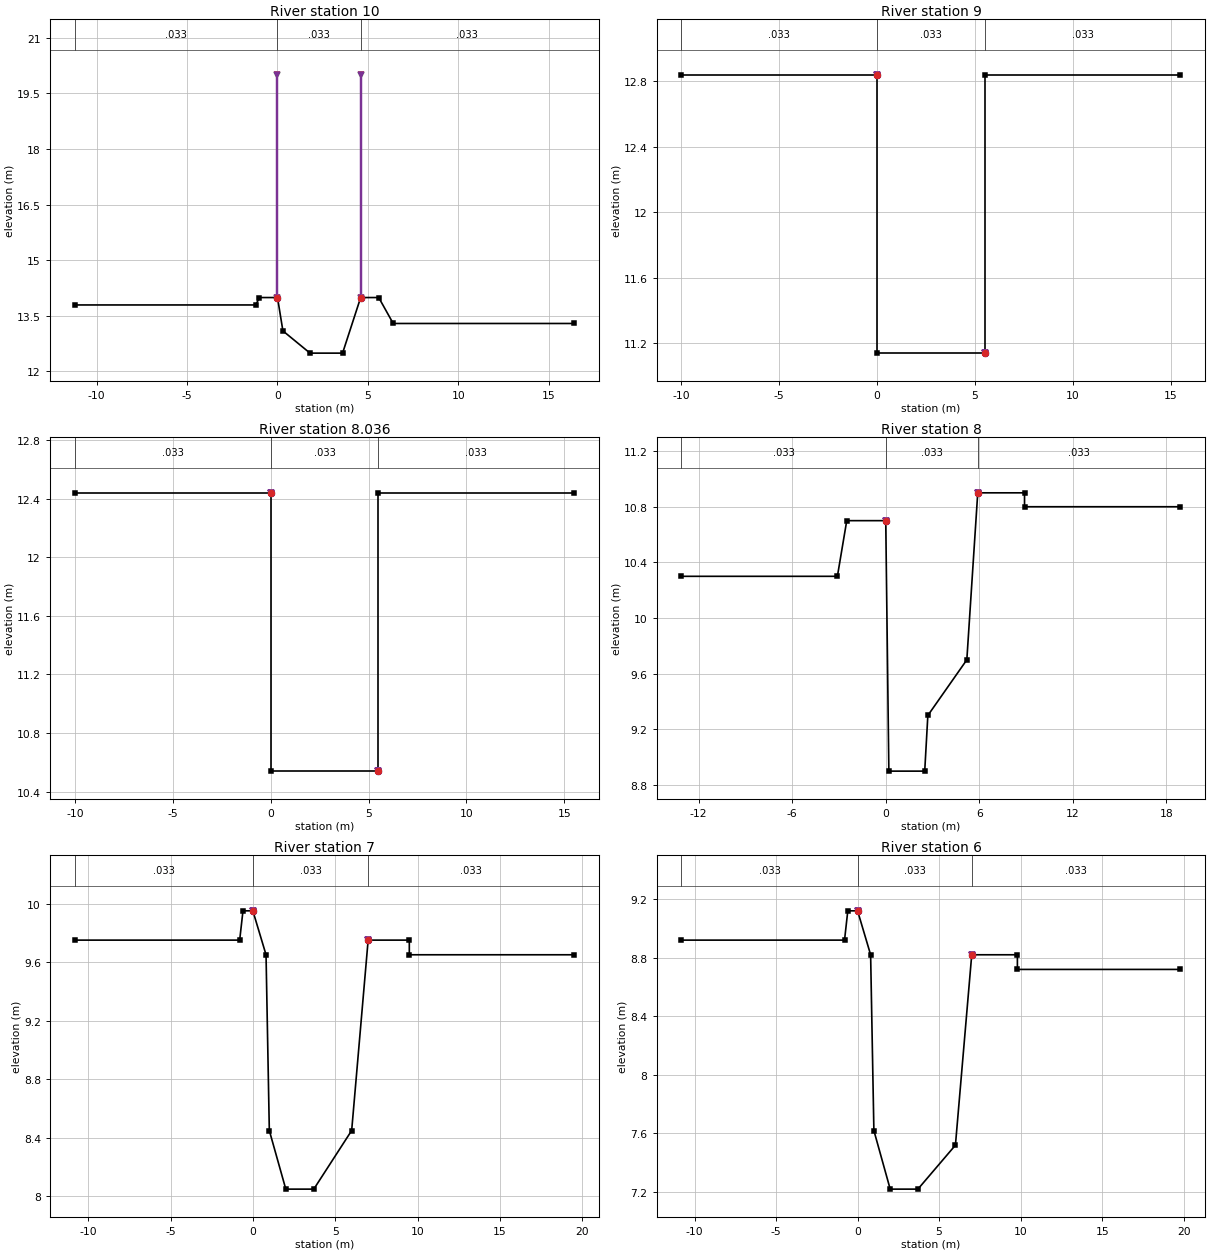
Type RM Length L Ch R = 1 ,10      ,50,50,50
#Sta/Elev= 11
   -11.2   13.79    -1.2   13.79      -1   13.99       0   13.99      .3   13.09
     1.8   12.49     3.6   12.49     4.6   13.99     5.6   13.99     6.4   13.29
    16.4   13.29
#Mann= 3 , 0 , 0
   -11.2    .033       0       0    .033       0     4.6    .033       0
Levee=-1,0,20,-1,4.6,20,,
Bank Sta=0,4.6
XS Rating Curve= 0
Exp/Cntr=.3,.1

Type RM Length L Ch R = 1 ,9       ,14,14,14
#Sta/Elev= 6
     -10   12.84       0   12.84       0   11.14     5.5   11.14     5.5   12.84
    15.5   12.84
#Mann= 3 , 0 , 0
     -10    .033       0       0    .033       0     5.5    .033       0
Levee=-1,0,12.84,-1,5.5,11.14,,
Bank Sta=0,5.5
XS Rating Curve= 0
Exp/Cntr=.3,.1

Type RM Length L Ch R = 1 ,8.036   ,36,36,36
#Sta/Elev= 6
     -10   12.44       0   12.44       0   10.54     5.5   10.54     5.5   12.44
    15.5   12.44
#Mann= 3 , 0 , 0
     -10    .033       0       0    .033       0     5.5    .033       0
Levee=-1,0,12.44,-1,5.5,10.54,,
Bank Sta=0,5.5
XS Rating Curve= 0
Exp/Cntr=.3,.1

Type RM Length L Ch R = 1 ,8       ,50,50,50
#Sta/Elev= 12
   -13.1    10.3    -3.1    10.3    -2.5    10.7       0    10.7      .2     8.9
     2.5     8.9     2.7     9.3     5.2     9.7     5.9    10.9     8.9    10.9
     8.9    10.8    18.9    10.8
#Mann= 3 , 0 , 0
   -13.1    .033       0       0    .033       0     5.9    .033       0
Levee=-1,0,10.7,-1,5.9,10.9,,
Bank Sta=0,5.9
XS Rating Curve= 0
Exp/Cntr=.3,.1

Type RM Length L Ch R = 1 ,7       ,50,50,50
#Sta/Elev= 13
   -10.8    9.75     -.8    9.75     -.6    9.95       0    9.95      .8    9.65
       1    8.45       2    8.05     3.7    8.05       6    8.45       7    9.75
     9.5    9.75     9.5    9.65    19.5    9.65
#Mann= 3 , 0 , 0
   -10.8    .033       0       0    .033       0       7    .033       0
Levee=-1,0,9.95,-1,7,9.75,,
Bank Sta=0,7
XS Rating Curve= 0
Exp/Cntr=.3,.1

Type RM Length L Ch R = 1 ,6       ,18,18,18
#Sta/Elev= 13
   -10.8    8.92     -.8    8.92     -.6    9.12       0    9.12      .8    8.82
       1    7.62       2    7.22     3.7    7.22       6    7.52       7    8.82
     9.8    8.82     9.8    8.72    19.8    8.72
#Mann= 3 , 0 , 0
   -10.8    .033       0       0    .033       0       7    .033       0
Levee=-1,0,9.12,-1,7,8.82,,
Bank Sta=0,7
XS Rating Curve= 0
Exp/Cntr=.3,.1

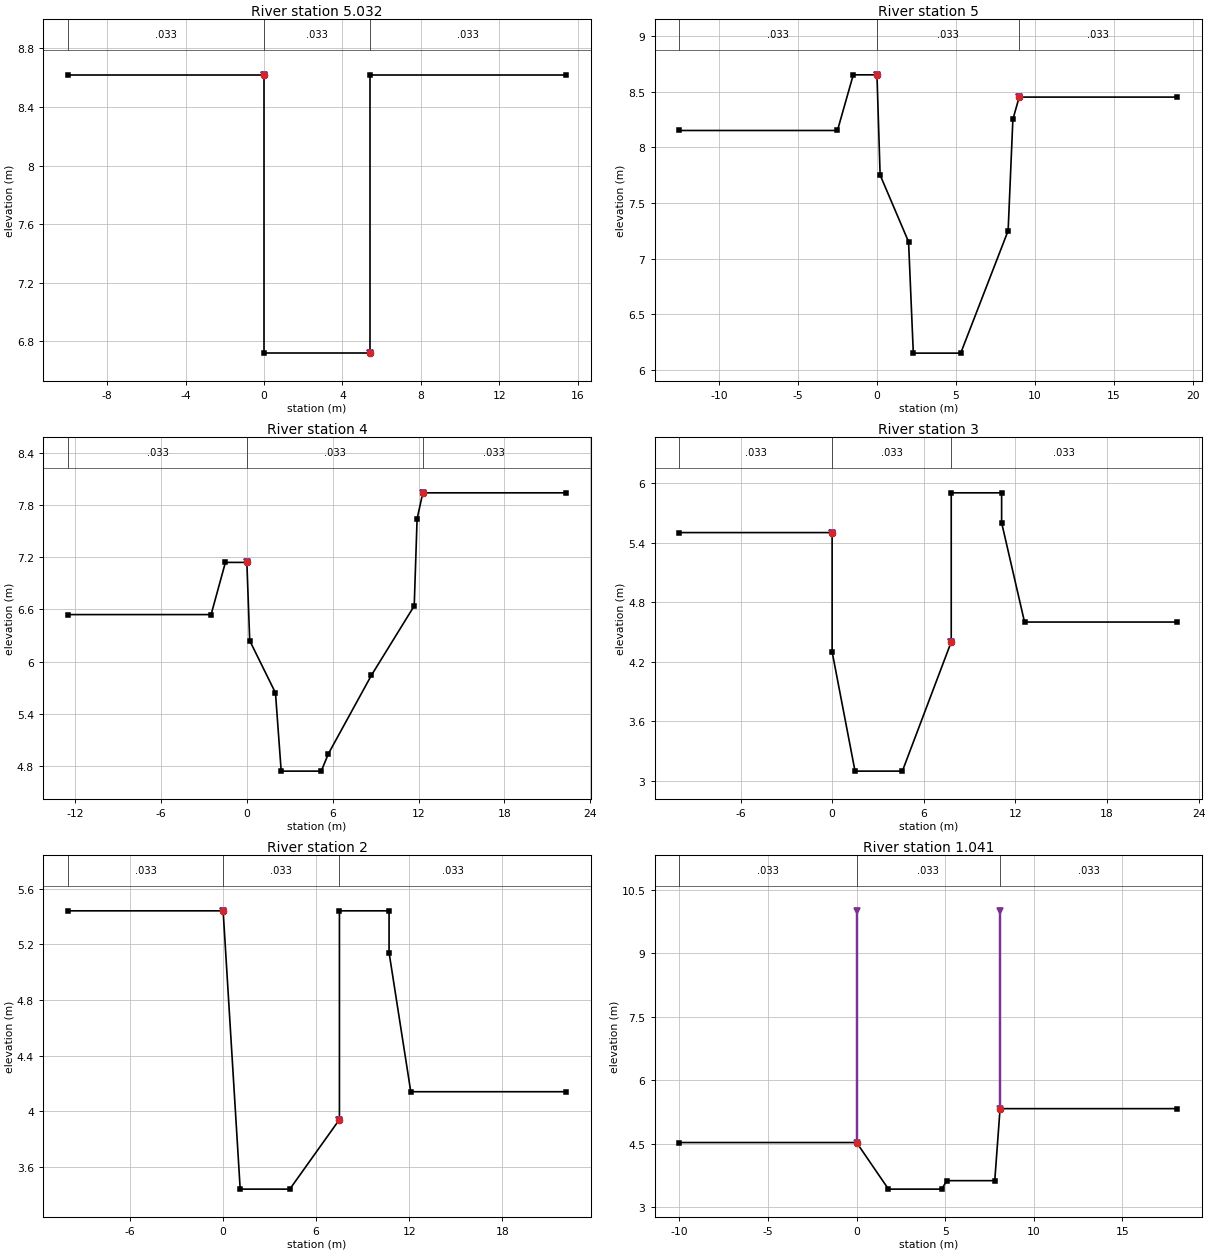
Type RM Length L Ch R = 1 ,5.032   ,32,32,32
#Sta/Elev= 6
     -10    8.62       0    8.62       0    6.72     5.4    6.72     5.4    8.62
    15.4    8.62
#Mann= 3 , 0 , 0
     -10    .033       0       0    .033       0     5.4    .033       0
Levee=-1,0,8.62,-1,5.4,6.72,,
Bank Sta=0,5.4
XS Rating Curve= 0
Exp/Cntr=.3,.1

Type RM Length L Ch R = 1 ,5       ,50,50,50
#Sta/Elev= 12
   -12.5    8.15    -2.5    8.15    -1.5    8.65       0    8.65      .2    7.75
       2    7.15     2.3    6.15     5.3    6.15     8.3    7.25     8.6    8.25
       9    8.45      19    8.45
#Mann= 3 , 0 , 0
   -12.5    .033       0       0    .033       0       9    .033       0
Levee=-1,0,8.65,-1,9,8.45,,
Bank Sta=0,9
XS Rating Curve= 0
Exp/Cntr=.3,.1

Type RM Length L Ch R = 1 ,4       ,50,50,50
#Sta/Elev= 14
   -12.5    6.54    -2.5    6.54    -1.5    7.14       0    7.14      .2    6.24
       2    5.64     2.4    4.74     5.2    4.74     5.7    4.94     8.7    5.84
    11.7    6.64    11.9    7.64    12.3    7.94    22.3    7.94
#Mann= 3 , 0 , 0
   -12.5    .033       0       0    .033       0    12.3    .033       0
Levee=-1,0,7.14,-1,12.3,7.94,,
Bank Sta=0,12.3
XS Rating Curve= 0
Exp/Cntr=.3,.1

Type RM Length L Ch R = 1 ,3       ,50,50,50
#Sta/Elev= 11
     -10     5.5       0     5.5       0     4.3     1.5     3.1     4.6     3.1
     7.8     4.4     7.8     5.9    11.1     5.9    11.1     5.6    12.6     4.6
    22.6     4.6
#Mann= 3 , 0 , 0
     -10    .033       0       0    .033       0     7.8    .033       0
Levee=-1,0,5.5,-1,7.8,4.4,,
Bank Sta=0,7.8
XS Rating Curve= 0
Exp/Cntr=.3,.1

Type RM Length L Ch R = 1 ,2       ,9,9,9
#Sta/Elev= 10
     -10    5.44       0    5.44     1.1    3.44     4.3    3.44     7.5    3.94
     7.5    5.44    10.7    5.44    10.7    5.14    12.1    4.14    22.1    4.14
#Mann= 3 , 0 , 0
     -10    .033       0       0    .033       0     7.5    .033       0
Levee=-1,0,5.44,-1,7.5,3.94,,
Bank Sta=0,7.5
XS Rating Curve= 0
Exp/Cntr=.3,.1

Type RM Length L Ch R = 1 ,1.041   ,41,41,41
#Sta/Elev= 8
     -10    4.53       0    4.53     1.8    3.43     4.8    3.43     5.1    3.63
     7.8    3.63     8.1    5.33    18.1    5.33
#Mann= 3 , 0 , 0
     -10    .033       0       0    .033       0     8.1    .033       0
Levee=-1,0,10,-1,8.1,10,,
Bank Sta=0,8.1
XS Rating Curve= 0
Exp/Cntr=.3,.1

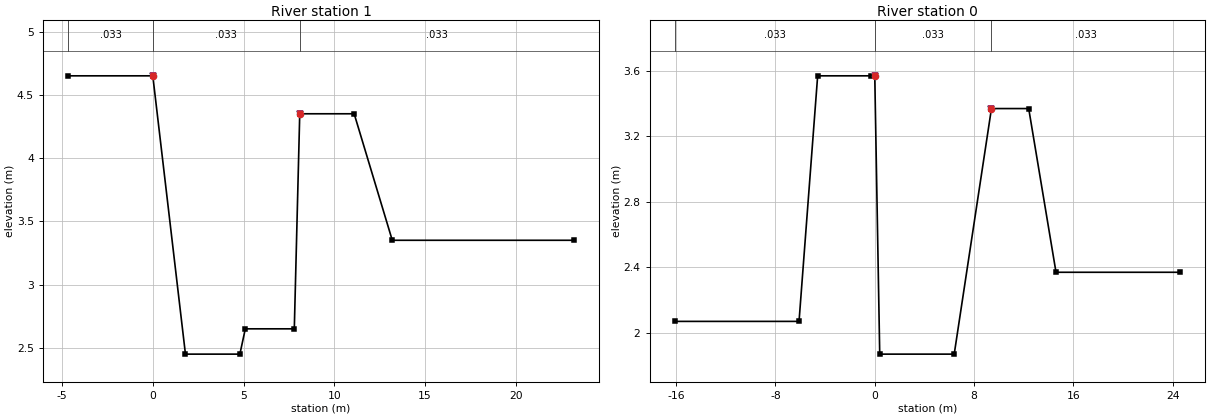
Type RM Length L Ch R = 1 ,1       ,50,50,50
#Sta/Elev= 10
   -4.65    4.65       0    4.65     1.8    2.45     4.8    2.45     5.1    2.65
     7.8    2.65     8.1    4.35    11.1    4.35    13.2    3.35    23.2    3.35
#Mann= 3 , 0 , 0
   -4.65    .033       0       0    .033       0     8.1    .033       0
Levee=-1,0,4.65,-1,8.1,4.35,,
Bank Sta=0,8.1
XS Rating Curve= 0
Exp/Cntr=.3,.1

Type RM Length L Ch R = 1 ,0       ,0,0,0
#Sta/Elev= 11
   -16.1    2.07    -6.1    2.07    -4.6    3.57     -.3    3.57       0    3.57
      .4    1.87     6.4    1.87     9.4    3.37    12.4    3.37    14.6    2.37
    24.6    2.37
#Mann= 3 , 0 , 0
   -16.1    .033       0       0    .033       0     9.4    .033       0
Levee=-1,0,3.57,-1,9.4,3.37,,
Bank Sta=0,9.4
XS Rating Curve= 0
Exp/Cntr=.3,.1

Chan Stop Cuts=-1