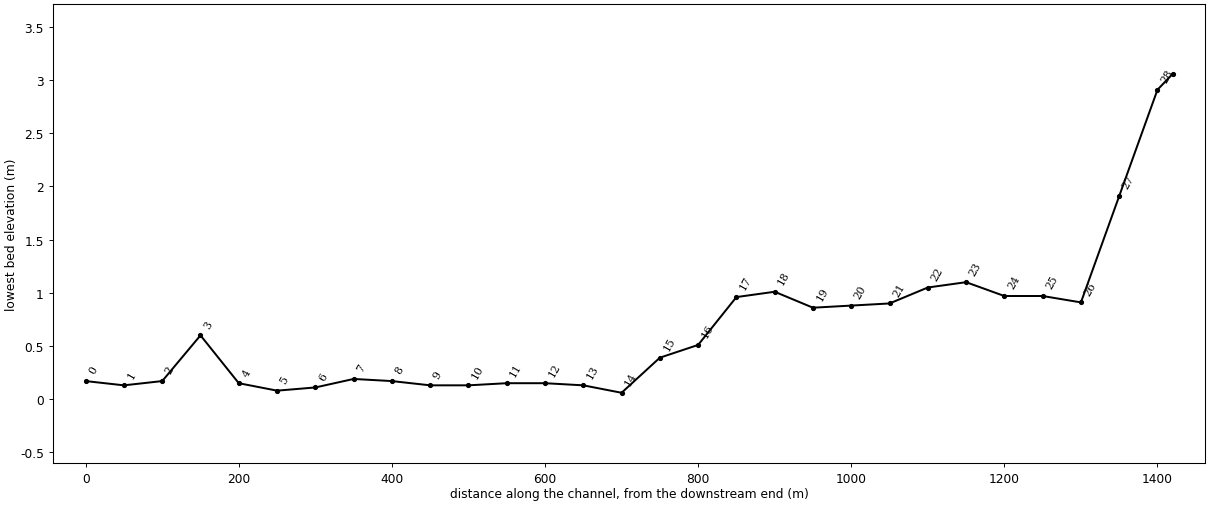
--- OPC.prj (project) ---

Proj Title=OPO
Current Plan=p01
Default Exp/Contr=.3,.1
SI Units
Geom File=g01
Flow File=f01
Plan File=p01
Y Axis Title=Elevation
X Axis Title(PF)=Main Channel Distance
X Axis Title(XS)=Station
BEGIN DESCRIPTION:
           BACK WATER COMPUTATION
      APPLICATION OF HEC-2 BY Samju Construction Engineering
      OPO-STREEM : 30 YR
END DESCRIPTION:
DSS Export Rating Curves= 0
DSS Export Rating Curve Sorted= 0
DSS Export Volume Flow Curves= 0
DXF OffsetX= 0
DXF OffsetY= 0
DXF ScaleX= 1
DXF ScaleY= 10

--- OPC.p01 (plan) ---

Plan Title=Imported Plan 01
Version=Version 3.0.1  Mar 2001
Short Identifier=Imported Pla
Geom File=g01
Flow File=f01
Subcritical Flow
K Sum by GR= 0
Std Step Tol= 0.003
Critical Tol= 0.003
Num of Std Step Trials= 20
Max Error Tol= 0.1
Flow Tol Ratio= 0.001
Split Flow NTrial= 30
Split Flow Tol= 0.02
Split Flow Ratio= 0.02
Log Output Level= 0
Friction Slope Method= 1
Unsteady Friction Slope Method= 2
Parabolic Critical Depth
Global Vel Dist= 0 , 0 , 0
Global Log Level= 0
CheckData=True
Encroach Param=-1 ,0,0, 0
Computation Interval=1HOUR
Output Interval=1HOUR
Run HTab= 0
Run UNet= 0
Run PostProcess= 0
UNET Theta= 1
UNET ZTol= 0.02
UNET ZSATol= 0.1
UNET MxIter= 20
UNET MaxInSteps= 20
UNET DtIC= 0
UNET DtMin= 0
UNET MaxCRTS= 20
UNET WFStab= 2
UNET SFStab= 1
UNET WFX= 1
UNET SFX= 1
UNET Convert EG Bridges=-1
UNET Use Existing IB Tables=-1
Instantaneous Interval=1HOUR
Write IC File= 0
Write Velocity= 0
Write Detailed= 0

--- OPC.f01 (steady flow) ---

Flow Title=Imported Flow 01
Version=Version 3.0.1  Mar 2001
Number of Profiles= 5
Profile Names=10YR,20YR,30YR,50YR,80YR
River Rch & RM=RIVER-1,Reach-1         ,28.02
    60.8      67   70.63   75.21   79.42
River Rch & RM=RIVER-1,Reach-1         ,20
   69.25   76.33   80.48    85.7   90.51
River Rch & RM=RIVER-1,Reach-1         ,10
   76.12   83.93    88.5   94.26   99.56
River Rch & RM=OPO,OPO             ,28.02
    60.8      67   70.63   75.21   79.42
River Rch & RM=OPO,OPO             ,20
   69.25   76.33   80.48    85.7   90.51
River Rch & RM=OPO,OPO             ,10
   76.12   83.93    88.5   94.26   99.56
Boundary for River Rch & Prof#=OPO,OPO             , 1
Up Type= 0
Dn Type= 3
Dn Slope=.007
Boundary for River Rch & Prof#=OPO,OPO             , 2
Up Type= 0
Dn Type= 3
Dn Slope=.007
Boundary for River Rch & Prof#=OPO,OPO             , 3
Up Type= 0
Dn Type= 3
Dn Slope=.007
Boundary for River Rch & Prof#=OPO,OPO             , 4
Up Type= 0
Dn Type= 3
Dn Slope=.007
Boundary for River Rch & Prof#=OPO,OPO             , 5
Up Type= 0
Dn Type= 3
Dn Slope=.007
DSS Import GetInterval= 0
DSS Import GetPeak= 0
DSS Import FillOption= 0

--- OPC.g01 (geometry) ---

Geom Title=Imported Geom 01
Version=Version 3.0.1  Mar 2001

River Reach=OPO             ,OPO
Reach XY= 2
              .5             .95              .5             .05

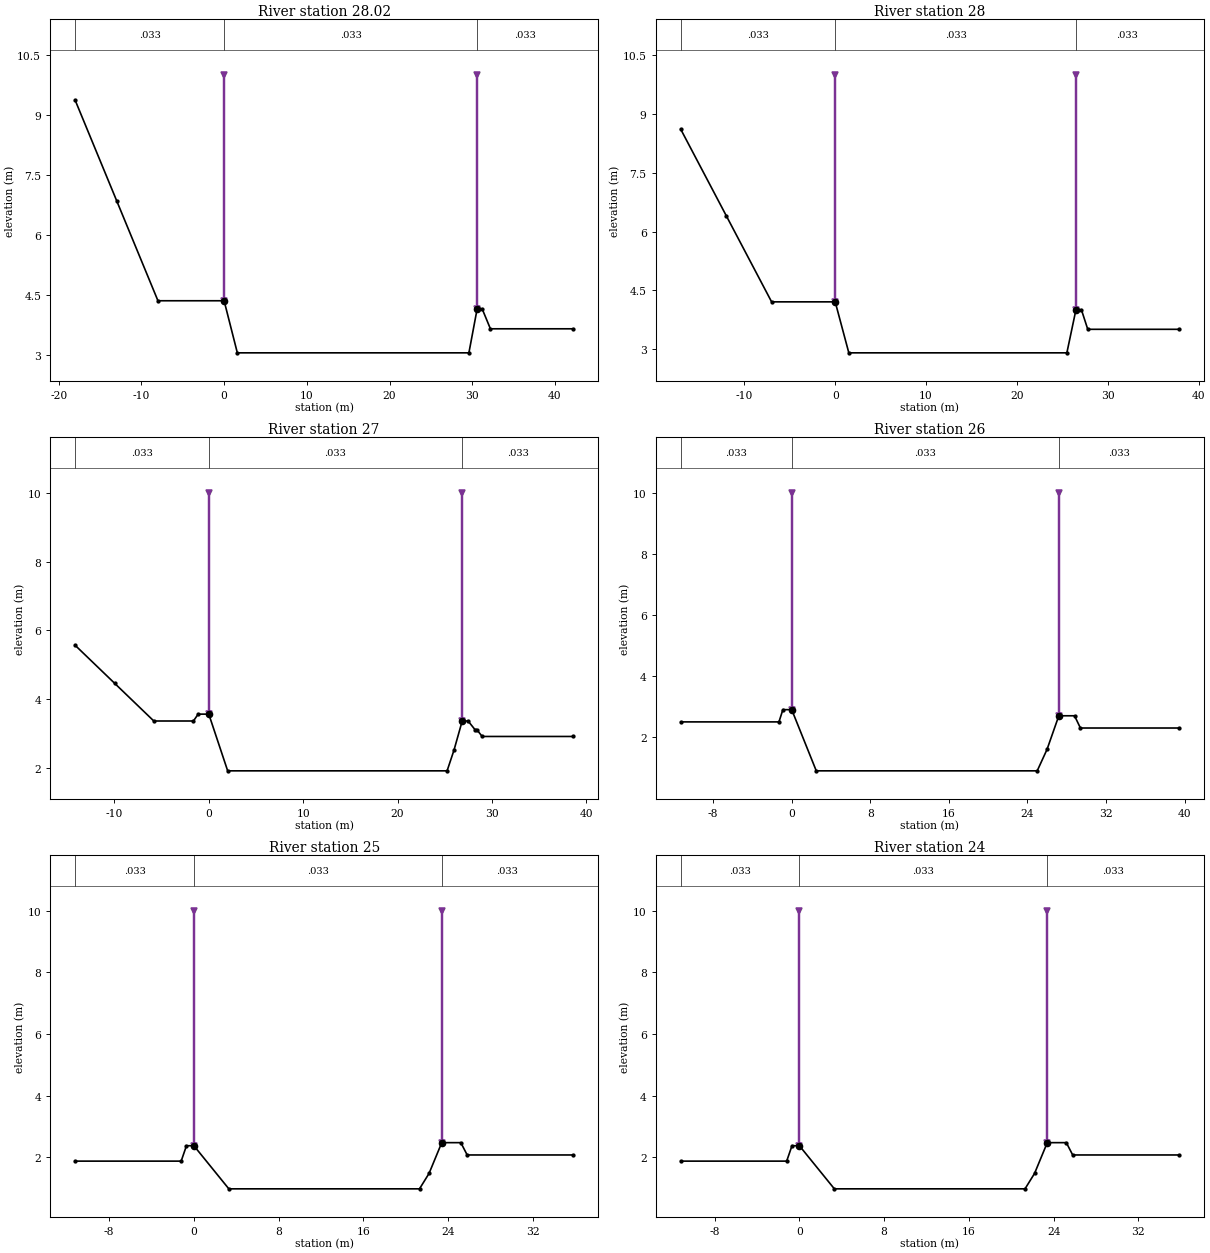
Type RM Length L Ch R = 1 ,28.02   ,20,20,20
#Sta/Elev= 10
     -18    9.36     -13    6.86      -8    4.36       0    4.36     1.6    3.06
    29.6    3.06    30.6    4.16    31.2    4.16    32.2    3.66    42.2    3.66
#Mann= 3 , 0 , 0
     -18    .033       0       0    .033       0    30.6    .033       0
Levee=-1,0,10,-1,30.6,10,,
Bank Sta=0,30.6
XS Rating Curve= 0
Exp/Cntr=.3,.1

Type RM Length L Ch R = 1 ,28      ,50,50,50
#Sta/Elev= 10
     -17    8.61     -12    6.41      -7    4.21       0    4.21     1.5    2.91
    25.5    2.91    26.5    4.01    27.1    4.01    27.8    3.51    37.8    3.51
#Mann= 3 , 0 , 0
     -17    .033       0       0    .033       0    26.5    .033       0
Levee=-1,0,10,-1,26.5,10,,
Bank Sta=0,26.5
XS Rating Curve= 0
Exp/Cntr=.3,.1

Type RM Length L Ch R = 1 ,27      ,50,50,50
#Sta/Elev= 15
  -14.15    5.56  -9.988    4.46  -5.826    3.36  -1.628    3.36  -1.127    3.56
       0    3.56       2    1.91   25.25    1.91  25.977    2.51   26.85    3.36
  27.474    3.36  28.202    3.11  28.391    3.11  28.969    2.91    38.6    2.91
#Mann= 3 , 0 , 0
  -14.15    .033       0       0    .033       0   26.85    .033       0
Levee=-1,0,10,-1,26.85,10,,
Bank Sta=0,26.85
XS Rating Curve= 0
Exp/Cntr=.3,.1

Type RM Length L Ch R = 1 ,26      ,50,50,50
#Sta/Elev= 11
   -11.3    2.51    -1.3    2.51     -.9    2.91       0    2.91     2.5     .91
      25     .91      26    1.61    27.2    2.71    28.8    2.71    29.4    2.31
    39.4    2.31
#Mann= 3 , 0 , 0
   -11.3    .033       0       0    .033       0    27.2    .033       0
Levee=-1,0,10,-1,27.2,10,,
Bank Sta=0,27.2
XS Rating Curve= 0
Exp/Cntr=.3,.1

Type RM Length L Ch R = 1 ,25      ,50,50,50
#Sta/Elev= 11
   -11.2    1.87    -1.2    1.87     -.7    2.37       0    2.37     3.3     .97
    21.3     .97    22.2    1.47    23.4    2.47    25.2    2.47    25.8    2.07
    35.8    2.07
#Mann= 3 , 0 , 0
   -11.2    .033       0       0    .033       0    23.4    .033       0
Levee=-1,0,10,-1,23.4,10,,
Bank Sta=0,23.4
XS Rating Curve= 0
Exp/Cntr=.3,.1

Type RM Length L Ch R = 1 ,24      ,50,50,50
#Sta/Elev= 11
   -11.2    1.87    -1.2    1.87     -.7    2.37       0    2.37     3.3     .97
    21.3     .97    22.2    1.47    23.4    2.47    25.2    2.47    25.8    2.07
    35.8    2.07
#Mann= 3 , 0 , 0
   -11.2    .033       0       0    .033       0    23.4    .033       0
Levee=-1,0,10,-1,23.4,10,,
Bank Sta=0,23.4
XS Rating Curve= 0
Exp/Cntr=.3,.1

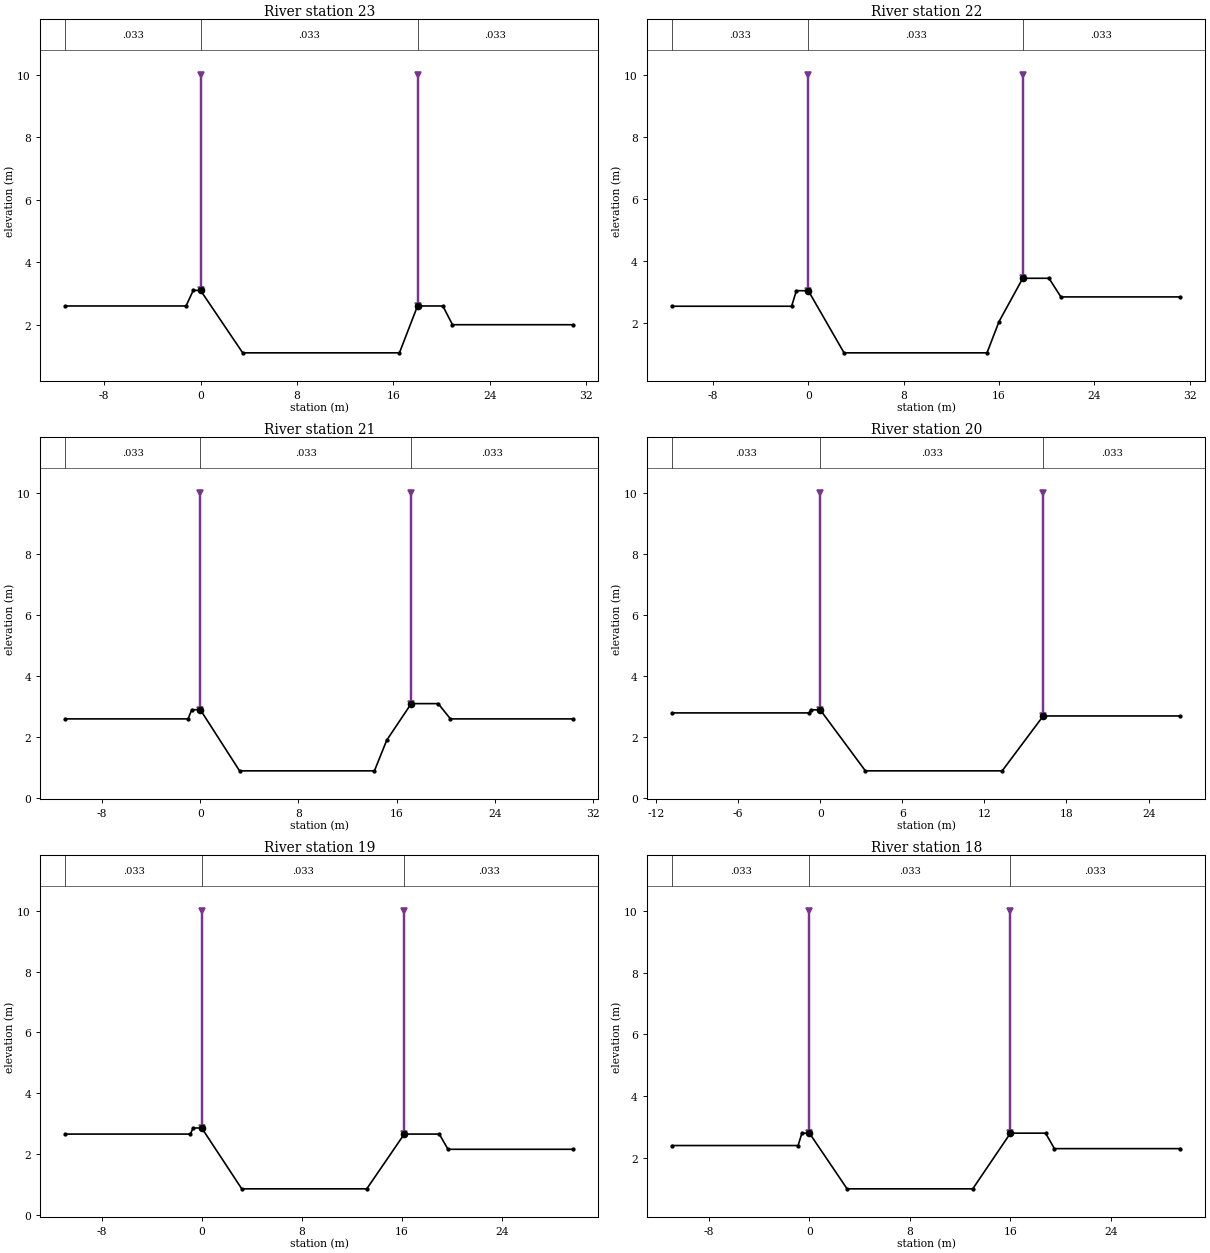
Type RM Length L Ch R = 1 ,23      ,50,50,50
#Sta/Elev= 10
   -11.2     2.6    -1.2     2.6     -.6     3.1       0     3.1     3.5     1.1
    16.5     1.1      18     2.6    20.1     2.6    20.9       2    30.9       2
#Mann= 3 , 0 , 0
   -11.2    .033       0       0    .033       0      18    .033       0
Levee=-1,0,10,-1,18,10,,
Bank Sta=0,18
XS Rating Curve= 0
Exp/Cntr=.3,.1

Type RM Length L Ch R = 1 ,22      ,50,50,50
#Sta/Elev= 11
   -11.4    2.55    -1.4    2.55      -1    3.05       0    3.05       3    1.05
      15    1.05      16    2.05      18    3.45    20.2    3.45    21.2    2.85
    31.2    2.85
#Mann= 3 , 0 , 0
   -11.4    .033       0       0    .033       0      18    .033       0
Levee=-1,0,10,-1,18,10,,
Bank Sta=0,18
XS Rating Curve= 0
Exp/Cntr=.3,.1

Type RM Length L Ch R = 1 ,21      ,50,50,50
#Sta/Elev= 11
     -11     2.6      -1     2.6     -.7     2.9       0     2.9     3.2      .9
    14.2      .9    15.2     1.9    17.2     3.1    19.4     3.1    20.4     2.6
    30.4     2.6
#Mann= 3 , 0 , 0
     -11    .033       0       0    .033       0    17.2    .033       0
Levee=-1,0,10,-1,17.2,10,,
Bank Sta=0,17.2
XS Rating Curve= 0
Exp/Cntr=.3,.1

Type RM Length L Ch R = 1 ,20      ,50,50,50
#Sta/Elev= 8
   -10.8    2.78     -.8    2.78     -.7    2.88       0    2.88     3.3     .88
    13.3     .88    16.3    2.68    26.3    2.68
#Mann= 3 , 0 , 0
   -10.8    .033       0       0    .033       0    16.3    .033       0
Levee=-1,0,10,-1,16.3,10,,
Bank Sta=0,16.3
XS Rating Curve= 0
Exp/Cntr=.3,.1

Type RM Length L Ch R = 1 ,19      ,50,50,50
#Sta/Elev= 10
   -10.9    2.66     -.9    2.66     -.7    2.86       0    2.86     3.2     .86
    13.2     .86    16.2    2.66      19    2.66    19.7    2.16    29.7    2.16
#Mann= 3 , 0 , 0
   -10.9    .033       0       0    .033       0    16.2    .033       0
Levee=-1,0,10,-1,16.2,10,,
Bank Sta=0,16.2
XS Rating Curve= 0
Exp/Cntr=.3,.1

Type RM Length L Ch R = 1 ,18      ,50,50,50
#Sta/Elev= 10
   -10.9    2.41     -.9    2.41     -.6    2.81       0    2.81       3    1.01
      13    1.01      16    2.81    18.8    2.81    19.5    2.31    29.5    2.31
#Mann= 3 , 0 , 0
   -10.9    .033       0       0    .033       0      16    .033       0
Levee=-1,0,10,-1,16,10,,
Bank Sta=0,16
XS Rating Curve= 0
Exp/Cntr=.3,.1

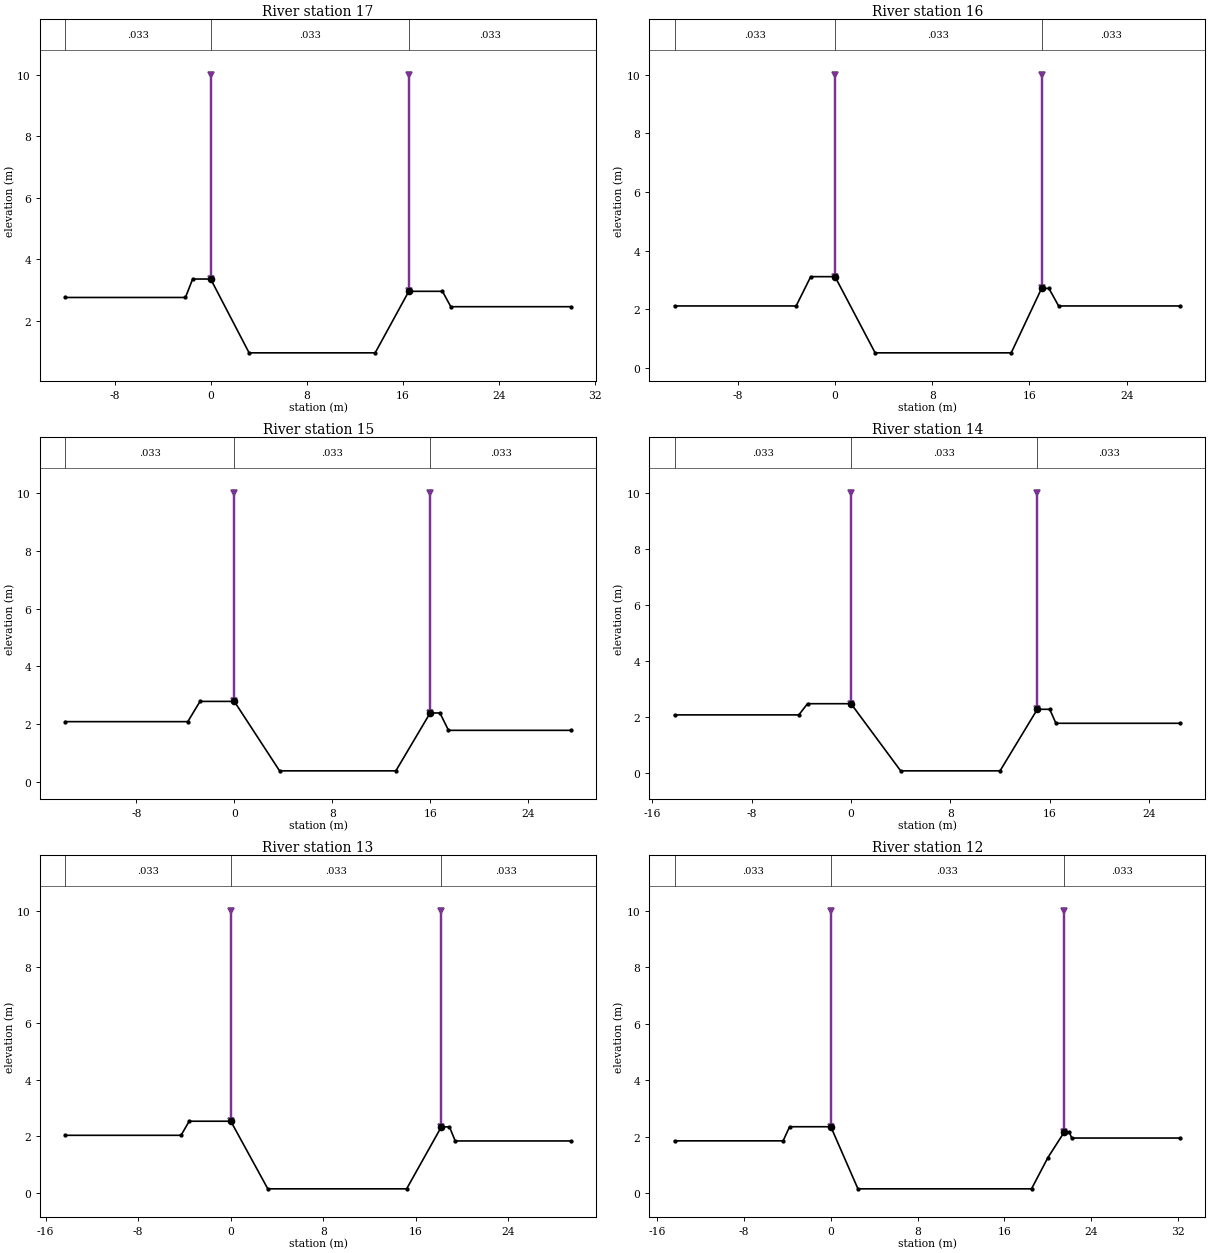
Type RM Length L Ch R = 1 ,17      ,50,50,50
#Sta/Elev= 10
   -12.1    2.76    -2.1    2.76    -1.5    3.36       0    3.36     3.2     .96
    13.7     .96    16.5    2.96    19.3    2.96      20    2.46      30    2.46
#Mann= 3 , 0 , 0
   -12.1    .033       0       0    .033       0    16.5    .033       0
Levee=-1,0,10,-1,16.5,10,,
Bank Sta=0,16.5
XS Rating Curve= 0
Exp/Cntr=.3,.1

Type RM Length L Ch R = 1 ,16      ,50,50,50
#Sta/Elev= 10
   -13.2    2.11    -3.2    2.11      -2    3.11       0    3.11     3.3     .51
    14.5     .51      17    2.71    17.6    2.71    18.4    2.11    28.4    2.11
#Mann= 3 , 0 , 0
   -13.2    .033       0       0    .033       0      17    .033       0
Levee=-1,0,10,-1,17,10,,
Bank Sta=0,17
XS Rating Curve= 0
Exp/Cntr=.3,.1

Type RM Length L Ch R = 1 ,15      ,50,50,50
#Sta/Elev= 10
   -13.8    2.09    -3.8    2.09    -2.8    2.79       0    2.79     3.7     .39
    13.2     .39      16    2.39    16.8    2.39    17.5    1.79    27.5    1.79
#Mann= 3 , 0 , 0
   -13.8    .033       0       0    .033       0      16    .033       0
Levee=-1,0,10,-1,16,10,,
Bank Sta=0,16
XS Rating Curve= 0
Exp/Cntr=.3,.1

Type RM Length L Ch R = 1 ,14      ,50,50,50
#Sta/Elev= 10
   -14.2    2.06    -4.2    2.06    -3.5    2.46       0    2.46       4     .06
      12     .06      15    2.26      16    2.26    16.5    1.76    26.5    1.76
#Mann= 3 , 0 , 0
   -14.2    .033       0       0    .033       0      15    .033       0
Levee=-1,0,10,-1,15,10,,
Bank Sta=0,15
XS Rating Curve= 0
Exp/Cntr=.3,.1

Type RM Length L Ch R = 1 ,13      ,50,50,50
#Sta/Elev= 10
   -14.3    2.03    -4.3    2.03    -3.6    2.53       0    2.53     3.2     .13
    15.2     .13    18.2    2.33    18.9    2.33    19.4    1.83    29.4    1.83
#Mann= 3 , 0 , 0
   -14.3    .033       0       0    .033       0    18.2    .033       0
Levee=-1,0,10,-1,18.2,10,,
Bank Sta=0,18.2
XS Rating Curve= 0
Exp/Cntr=.3,.1

Type RM Length L Ch R = 1 ,12      ,50,50,50
#Sta/Elev= 11
   -14.4    1.85    -4.4    1.85    -3.8    2.35       0    2.35     2.5     .15
    18.5     .15      20    1.25    21.5    2.15      22    2.15    22.2    1.95
    32.2    1.95
#Mann= 3 , 0 , 0
   -14.4    .033       0       0    .033       0    21.5    .033       0
Levee=-1,0,10,-1,21.5,10,,
Bank Sta=0,21.5
XS Rating Curve= 0
Exp/Cntr=.3,.1

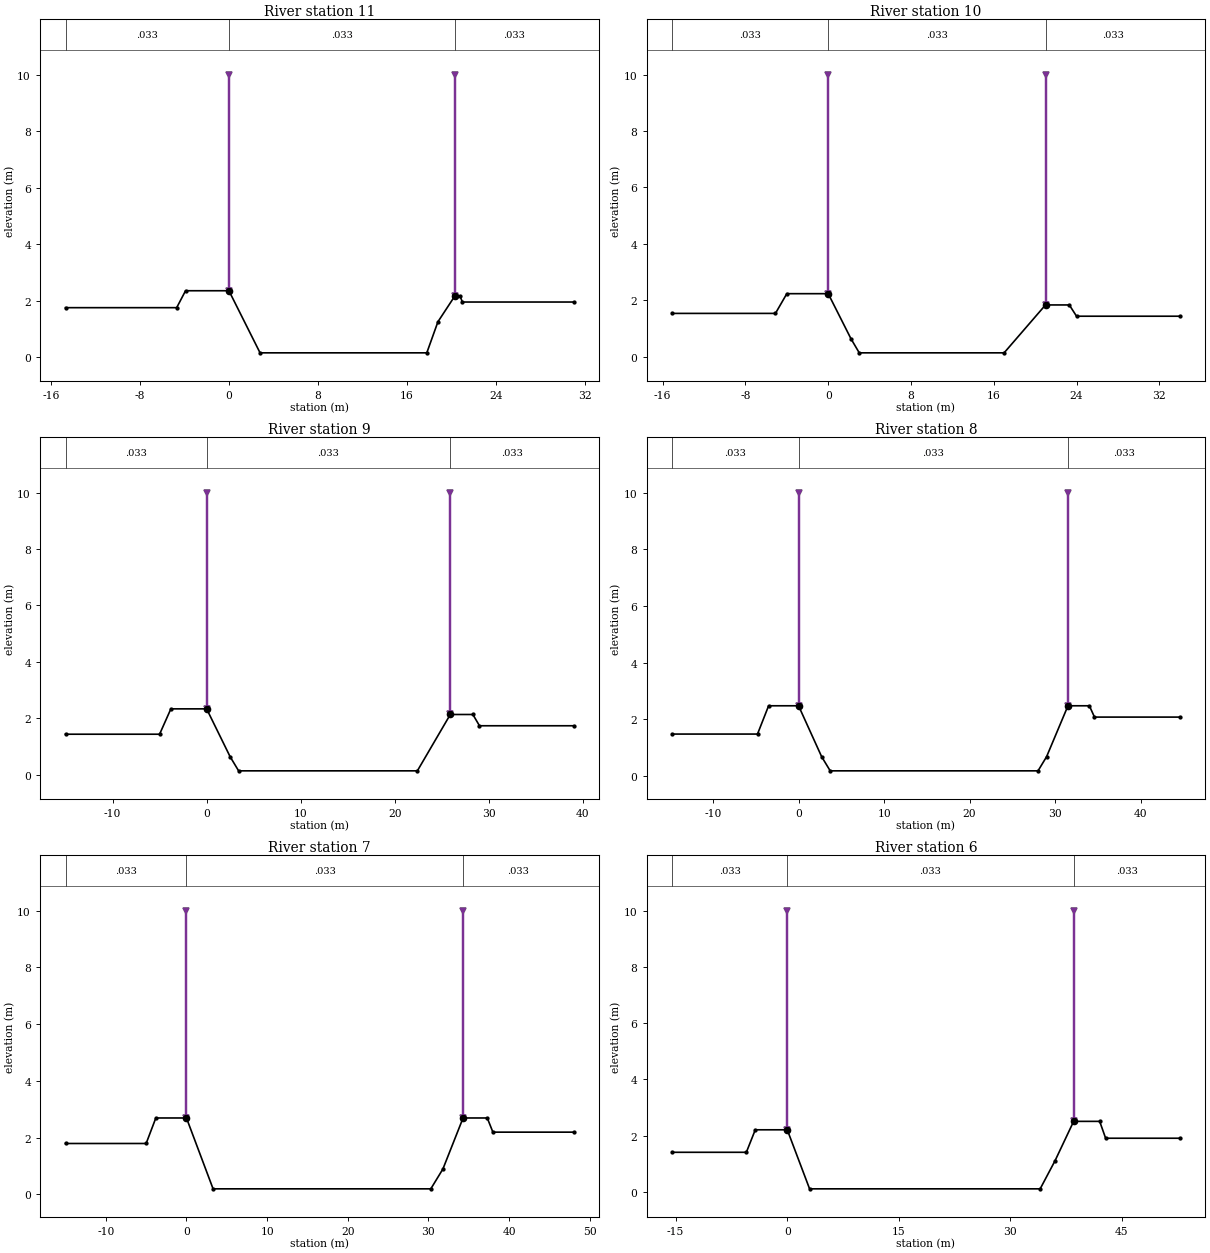
Type RM Length L Ch R = 1 ,11      ,50,50,50
#Sta/Elev= 11
   -14.7    1.75    -4.7    1.75    -3.9    2.35       0    2.35     2.8     .15
    17.8     .15    18.8    1.25    20.3    2.15    20.8    2.15      21    1.95
      31    1.95
#Mann= 3 , 0 , 0
   -14.7    .033       0       0    .033       0    20.3    .033       0
Levee=-1,0,10,-1,20.3,10,,
Bank Sta=0,20.3
XS Rating Curve= 0
Exp/Cntr=.3,.1

Type RM Length L Ch R = 1 ,10      ,50,50,50
#Sta/Elev= 11
   -15.1    1.53    -5.1    1.53      -4    2.23       0    2.23     2.2     .63
       3     .13      17     .13      21    1.83    23.3    1.83      24    1.43
      34    1.43
#Mann= 3 , 0 , 0
   -15.1    .033       0       0    .033       0      21    .033       0
Levee=-1,0,10,-1,21,10,,
Bank Sta=0,21
XS Rating Curve= 0
Exp/Cntr=.3,.1

Type RM Length L Ch R = 1 ,9       ,50,50,50
#Sta/Elev= 11
     -15    1.43      -5    1.43    -3.8    2.33       0    2.33     2.5     .63
     3.4     .13    22.4     .13    25.9    2.13    28.3    2.13      29    1.73
      39    1.73
#Mann= 3 , 0 , 0
     -15    .033       0       0    .033       0    25.9    .033       0
Levee=-1,0,10,-1,25.9,10,,
Bank Sta=0,25.9
XS Rating Curve= 0
Exp/Cntr=.3,.1

Type RM Length L Ch R = 1 ,8       ,50,50,50
#Sta/Elev= 12
   -14.8    1.47    -4.8    1.47    -3.5    2.47       0    2.47     2.7     .67
     3.7     .17      28     .17      29     .67    31.5    2.47      34    2.47
    34.6    2.07    44.6    2.07
#Mann= 3 , 0 , 0
   -14.8    .033       0       0    .033       0    31.5    .033       0
Levee=-1,0,10,-1,31.5,10,,
Bank Sta=0,31.5
XS Rating Curve= 0
Exp/Cntr=.3,.1

Type RM Length L Ch R = 1 ,7       ,50,50,50
#Sta/Elev= 11
     -15    1.79      -5    1.79    -3.8    2.69       0    2.69     3.3     .19
    30.3     .19    31.8     .89    34.3    2.69    37.3    2.69      38    2.19
      48    2.19
#Mann= 3 , 0 , 0
     -15    .033       0       0    .033       0    34.3    .033       0
Levee=-1,0,10,-1,34.3,10,,
Bank Sta=0,34.3
XS Rating Curve= 0
Exp/Cntr=.3,.1

Type RM Length L Ch R = 1 ,6       ,50,50,50
#Sta/Elev= 11
   -15.5    1.41    -5.5    1.41    -4.3    2.21       0    2.21       3     .11
      34     .11      36    1.11    38.5    2.51      42    2.51    42.8    1.91
    52.8    1.91
#Mann= 3 , 0 , 0
   -15.5    .033       0       0    .033       0    38.5    .033       0
Levee=-1,0,10,-1,38.5,10,,
Bank Sta=0,38.5
XS Rating Curve= 0
Exp/Cntr=.3,.1

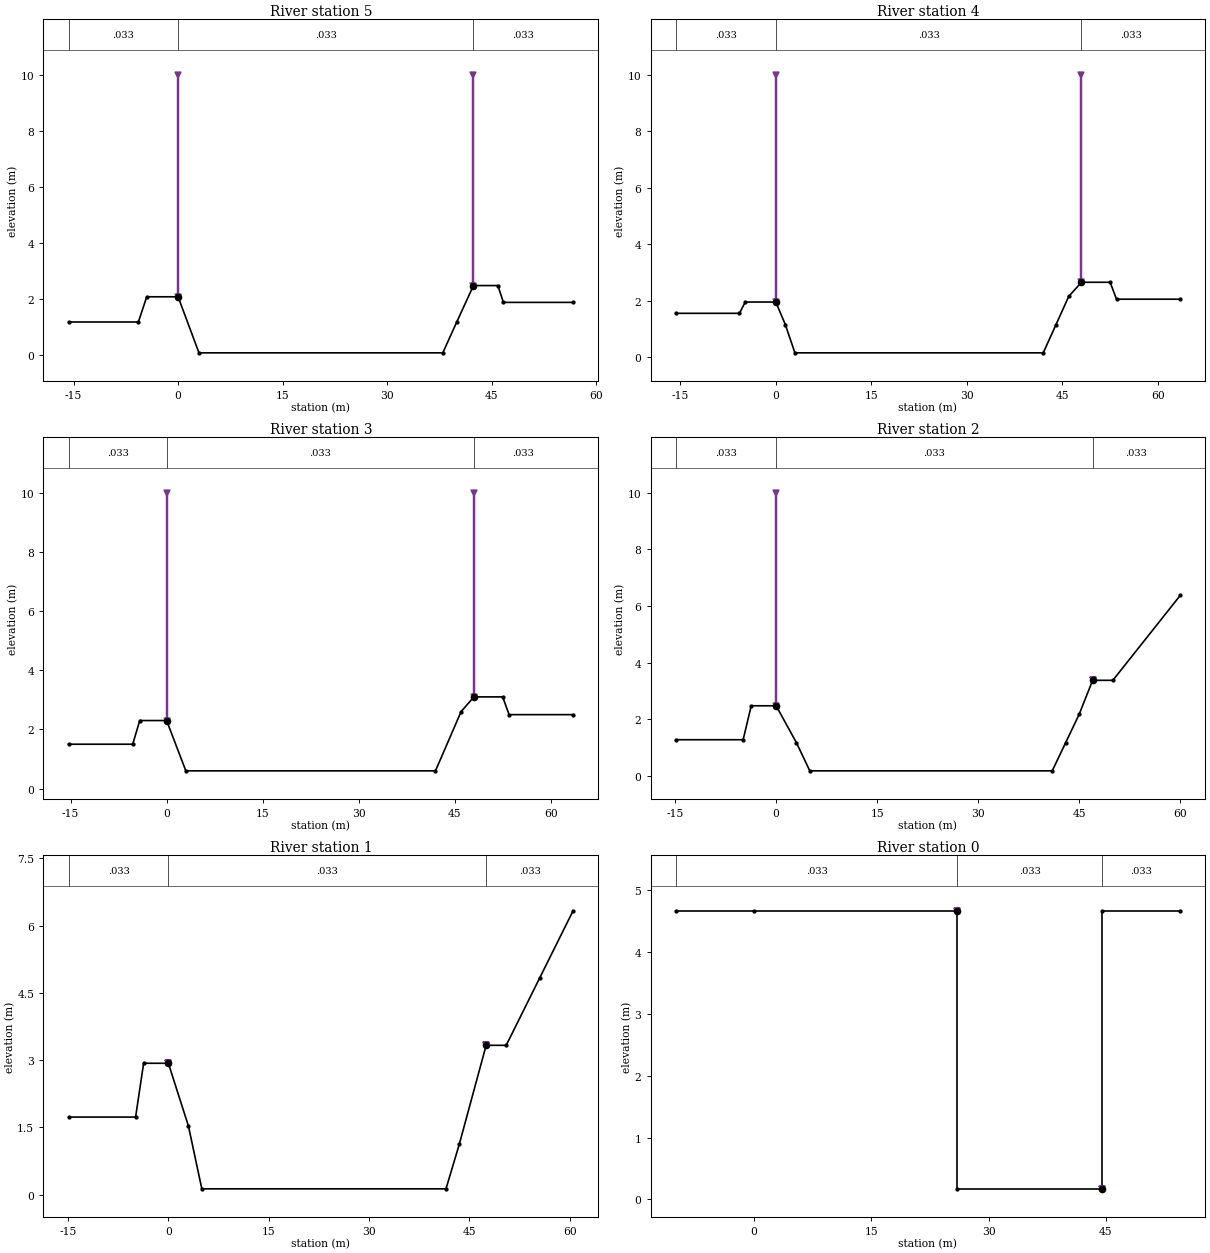
Type RM Length L Ch R = 1 ,5       ,50,50,50
#Sta/Elev= 11
   -15.7    1.18    -5.7    1.18    -4.5    2.08       0    2.08       3     .08
      38     .08      40    1.18    42.4    2.48    45.9    2.48    46.7    1.88
    56.7    1.88
#Mann= 3 , 0 , 0
   -15.7    .033       0       0    .033       0    42.4    .033       0
Levee=-1,0,10,-1,42.4,10,,
Bank Sta=0,42.4
XS Rating Curve= 0
Exp/Cntr=.3,.1

Type RM Length L Ch R = 1 ,4       ,50,50,50
#Sta/Elev= 13
   -15.7    1.55    -5.7    1.55    -4.8    1.95       0    1.95     1.5    1.15
       3     .15      42     .15      44    1.15      46    2.15      48    2.65
    52.5    2.65    53.5    2.05    63.5    2.05
#Mann= 3 , 0 , 0
   -15.7    .033       0       0    .033       0      48    .033       0
Levee=-1,0,10,-1,48,10,,
Bank Sta=0,48
XS Rating Curve= 0
Exp/Cntr=.3,.1

Type RM Length L Ch R = 1 ,3       ,50,50,50
#Sta/Elev= 11
   -15.3     1.5    -5.3     1.5    -4.2     2.3       0     2.3       3      .6
      42      .6      46     2.6      48     3.1    52.5     3.1    53.5     2.5
    63.5     2.5
#Mann= 3 , 0 , 0
   -15.3    .033       0       0    .033       0      48    .033       0
Levee=-1,0,10,-1,48,10,,
Bank Sta=0,48
XS Rating Curve= 0
Exp/Cntr=.3,.1

Type RM Length L Ch R = 1 ,2       ,50,50,50
#Sta/Elev= 12
   -14.9    1.27    -4.9    1.27    -3.7    2.47       0    2.47       3    1.17
       5     .17      41     .17      43    1.17      45    2.17      47    3.37
      50    3.37      60    6.37
#Mann= 3 , 0 , 0
   -14.9    .033       0       0    .033       0      47    .033       0
Levee=-1,0,10,-1,47,3.37,,
Bank Sta=0,47
XS Rating Curve= 0
Exp/Cntr=.3,.1

Type RM Length L Ch R = 1 ,1       ,50,50,50
#Sta/Elev= 12
   -14.9    1.73    -4.9    1.73    -3.7    2.93       0    2.93       3    1.53
       5     .13    41.5     .13    43.5    1.13    47.5    3.33    50.5    3.33
    55.5    4.83    60.5    6.33
#Mann= 3 , 0 , 0
   -14.9    .033       0       0    .033       0    47.5    .033       0
Levee=-1,0,2.93,-1,47.5,3.33,,
Bank Sta=0,47.5
XS Rating Curve= 0
Exp/Cntr=.3,.1

Type RM Length L Ch R = 1 ,0       ,0,0,0
#Sta/Elev= 7
     -10    4.67       0    4.67      26    4.67      26     .17    44.5     .17
    44.5    4.67    54.5    4.67
#Mann= 3 , 0 , 0
     -10    .033       0      26    .033       0    44.5    .033       0
Levee=-1,26,4.67,-1,44.5,.17,,
Bank Sta=26,44.5
XS Rating Curve= 0
Exp/Cntr=.3,.1

Chan Stop Cuts=-1