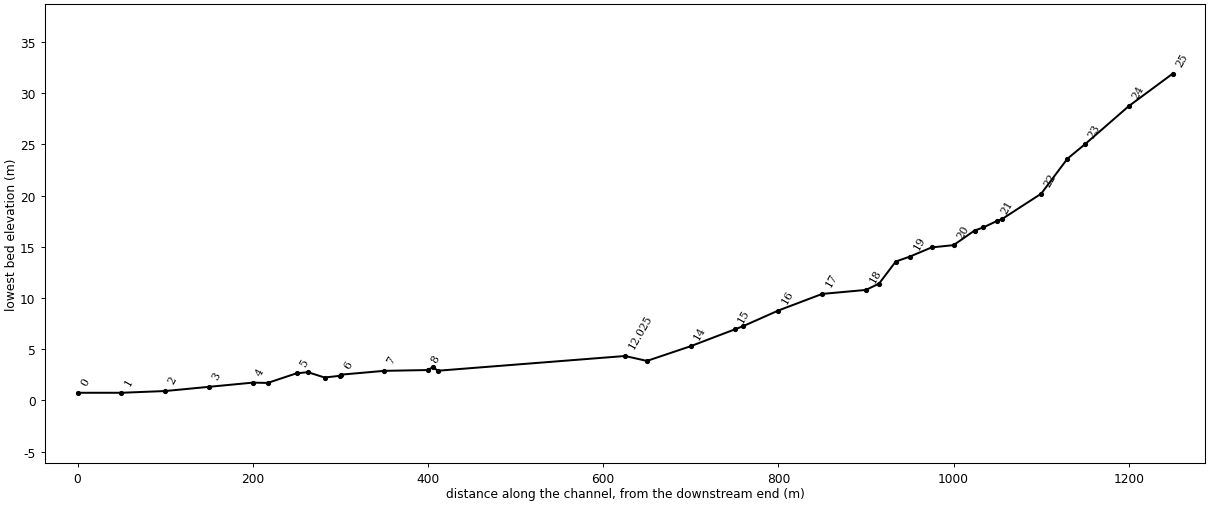
--- SJC.prj (project) ---

Proj Title=SUJUNG
Current Plan=p01
Default Exp/Contr=.3,.1
SI Units
Geom File=g01
Flow File=f01
Plan File=p01
Y Axis Title=Elevation
X Axis Title(PF)=Main Channel Distance
X Axis Title(XS)=Station
BEGIN DESCRIPTION:
           BACK WATER COMPUTATION
      APPLICATION OF HEC-2 BY Samju Construction Engineering
      SUJUNG-STREEM : 30 YR
END DESCRIPTION:
DSS Export Rating Curves= 0
DSS Export Rating Curve Sorted= 0
DSS Export Volume Flow Curves= 0
DXF OffsetX= 0
DXF OffsetY= 0
DXF ScaleX= 1
DXF ScaleY= 10

--- SJC.p01 (plan) ---

Plan Title=Imported Plan 01
Version=Version 3.0.1  Mar 2001
Short Identifier=Imported Pla
Geom File=g01
Flow File=f01
Subcritical Flow
K Sum by GR= 0
Std Step Tol= 0.003
Critical Tol= 0.003
Num of Std Step Trials= 20
Max Error Tol= 0.1
Flow Tol Ratio= 0.001
Split Flow NTrial= 30
Split Flow Tol= 0.02
Split Flow Ratio= 0.02
Log Output Level= 0
Friction Slope Method= 1
Unsteady Friction Slope Method= 2
Parabolic Critical Depth
Global Vel Dist= 0 , 0 , 0
Global Log Level= 0
CheckData=True
Encroach Param=-1 ,0,0, 0
Computation Interval=1HOUR
Output Interval=1HOUR
Run HTab= 0
Run UNet= 0
Run PostProcess= 0
UNET Theta= 1
UNET ZTol= 0.02
UNET ZSATol= 0.1
UNET MxIter= 20
UNET MaxInSteps= 20
UNET DtIC= 0
UNET DtMin= 0
UNET MaxCRTS= 20
UNET WFStab= 2
UNET SFStab= 1
UNET WFX= 1
UNET SFX= 1
UNET Convert EG Bridges=-1
UNET Use Existing IB Tables=-1
Instantaneous Interval=1HOUR
Write IC File= 0
Write Velocity= 0
Write Detailed= 0

--- SJC.f01 (steady flow) ---

Flow Title=Imported Flow 01
Version=Version 3.0.1  Mar 2001
Number of Profiles= 5
Profile Names=10YR,20YR,30YR,50YR,80YR
River Rch & RM=RIVER-1,Reach-1         ,25
    6.19    6.82    7.18    7.65    8.07
River Rch & RM=SOOJUNG,SOOJUNG         ,25
    6.19    6.82    7.18    7.65    8.07
Boundary for River Rch & Prof#=SOOJUNG,SOOJUNG         , 1
Up Type= 0
Dn Type= 3
Dn Slope=.025
Boundary for River Rch & Prof#=SOOJUNG,SOOJUNG         , 2
Up Type= 0
Dn Type= 3
Dn Slope=.025
Boundary for River Rch & Prof#=SOOJUNG,SOOJUNG         , 3
Up Type= 0
Dn Type= 3
Dn Slope=.025
Boundary for River Rch & Prof#=SOOJUNG,SOOJUNG         , 4
Up Type= 0
Dn Type= 3
Dn Slope=.025
Boundary for River Rch & Prof#=SOOJUNG,SOOJUNG         , 5
Up Type= 0
Dn Type= 3
Dn Slope=.025
DSS Import GetInterval= 0
DSS Import GetPeak= 0
DSS Import FillOption= 0

--- SJC.g01 (geometry) ---

Geom Title=Imported Geom 01
Version=Version 3.0.1  Mar 2001

River Reach=SOOJUNG         ,SOOJUNG
Reach XY= 2
              .5             .95              .5             .05

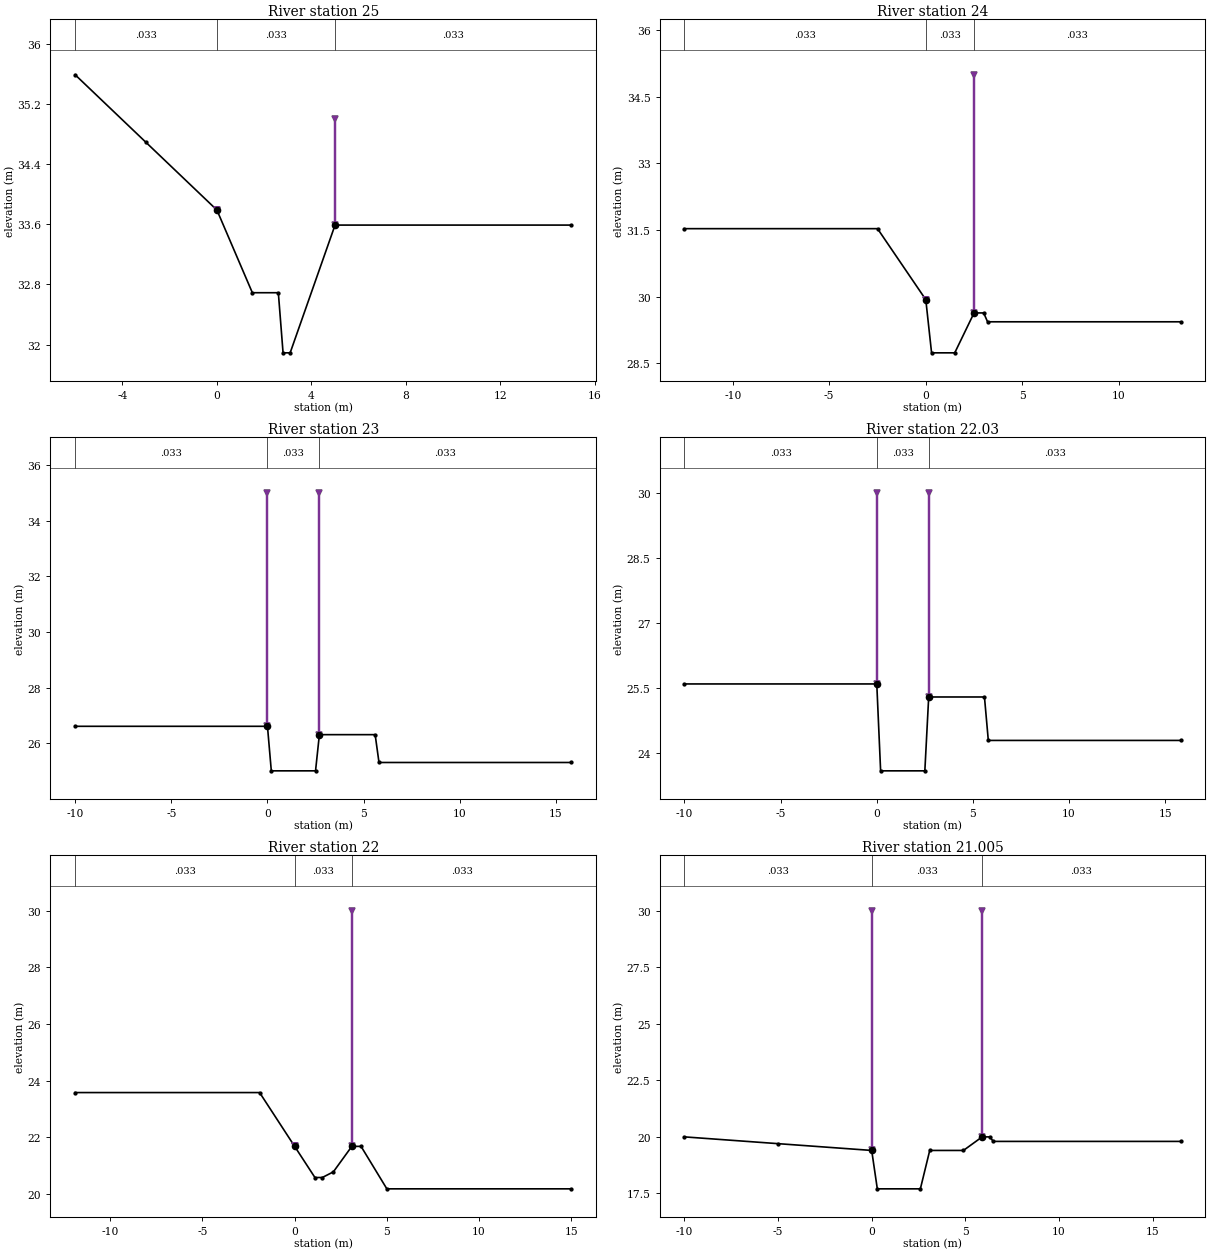
Type RM Length L Ch R = 1 ,25      ,50,50,50
#Sta/Elev= 9
      -6   35.59      -3   34.69       0   33.79     1.5   32.69     2.6   32.69
     2.8   31.89     3.1   31.89       5   33.59      15   33.59
#Mann= 3 , 0 , 0
      -6    .033       0       0    .033       0       5    .033       0
Levee=-1,0,33.79,-1,5,35,,
Bank Sta=0,5
XS Rating Curve= 0
Exp/Cntr=.3,.1

Type RM Length L Ch R = 1 ,24      ,50,50,50
#Sta/Elev= 9
   -12.5   31.53    -2.5   31.53       0   29.93      .3   28.73     1.5   28.73
     2.5   29.63       3   29.63     3.2   29.43    13.2   29.43
#Mann= 3 , 0 , 0
   -12.5    .033       0       0    .033       0     2.5    .033       0
Levee=-1,0,29.93,-1,2.5,35,,
Bank Sta=0,2.5
XS Rating Curve= 0
Exp/Cntr=.3,.1

Type RM Length L Ch R = 1 ,23      ,20,20,20
#Sta/Elev= 8
     -10   26.61       0   26.61      .2   25.01     2.5   25.01     2.7   26.31
     5.6   26.31     5.8   25.31    15.8   25.31
#Mann= 3 , 0 , 0
     -10    .033       0       0    .033       0     2.7    .033       0
Levee=-1,0,35,-1,2.7,35,,
Bank Sta=0,2.7
XS Rating Curve= 0
Exp/Cntr=.3,.1

Type RM Length L Ch R = 1 ,22.03   ,30,30,30
#Sta/Elev= 8
     -10    25.6       0    25.6      .2    23.6     2.5    23.6     2.7    25.3
     5.6    25.3     5.8    24.3    15.8    24.3
#Mann= 3 , 0 , 0
     -10    .033       0       0    .033       0     2.7    .033       0
Levee=-1,0,30,-1,2.7,30,,
Bank Sta=0,2.7
XS Rating Curve= 0
Exp/Cntr=.3,.1

Type RM Length L Ch R = 1 ,22      ,45,45,45
#Sta/Elev= 10
   -11.9   23.58    -1.9   23.58       0   21.68     1.1   20.58     1.5   20.58
     2.1   20.78     3.1   21.68     3.6   21.68       5   20.18      15   20.18
#Mann= 3 , 0 , 0
   -11.9    .033       0       0    .033       0     3.1    .033       0
Levee=-1,0,21.68,-1,3.1,30,,
Bank Sta=0,3.1
XS Rating Curve= 0
Exp/Cntr=.3,.1

Type RM Length L Ch R = 1 ,21.005  ,5,5,5
#Sta/Elev= 11
     -10   19.99      -5   19.69       0   19.39      .3   17.69     2.6   17.69
     3.1   19.39     4.9   19.39     5.9   19.99     6.3   19.99     6.5   19.79
    16.5   19.79
#Mann= 3 , 0 , 0
     -10    .033       0       0    .033       0     5.9    .033       0
Levee=-1,0,30,-1,5.9,30,,
Bank Sta=0,5.9
XS Rating Curve= 0
Exp/Cntr=.3,.1

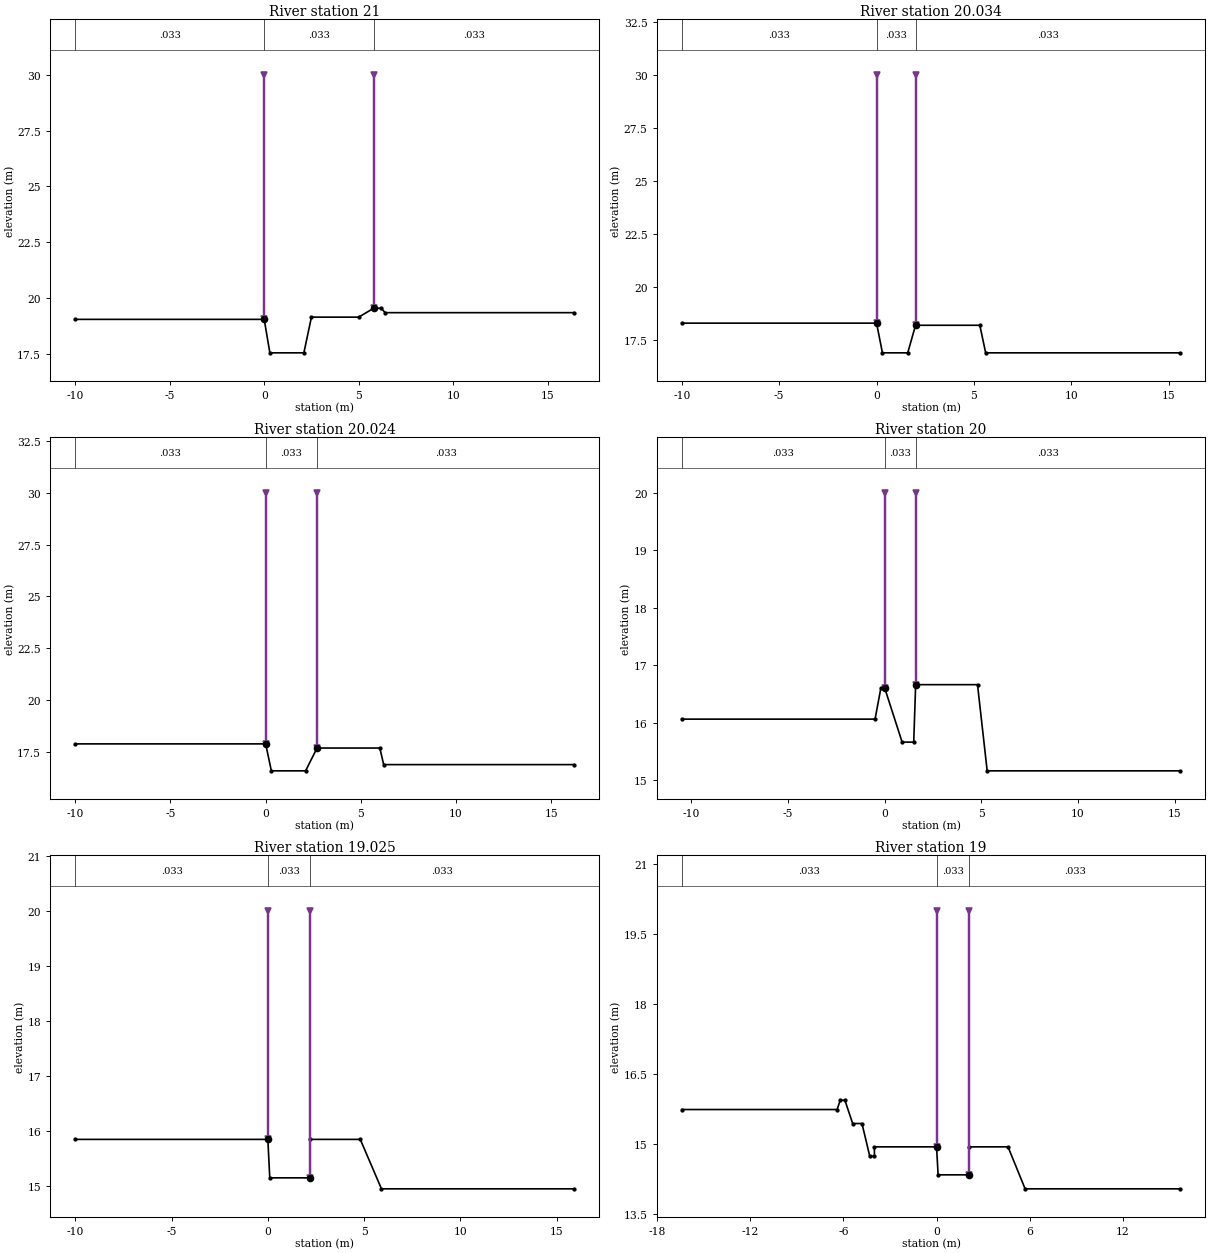
Type RM Length L Ch R = 1 ,21      ,16,16,16
#Sta/Elev= 10
     -10   19.04       0   19.04      .3   17.54     2.1   17.54     2.5   19.14
       5   19.14     5.8   19.54     6.2   19.54     6.4   19.34    16.4   19.34
#Mann= 3 , 0 , 0
     -10    .033       0       0    .033       0     5.8    .033       0
Levee=-1,0,30,-1,5.8,30,,
Bank Sta=0,5.8
XS Rating Curve= 0
Exp/Cntr=.3,.1

Type RM Length L Ch R = 1 ,20.034  ,10,10,10
#Sta/Elev= 8
     -10   18.29       0   18.29      .3   16.89     1.6   16.89       2   18.19
     5.3   18.19     5.6   16.89    15.6   16.89
#Mann= 3 , 0 , 0
     -10    .033       0       0    .033       0       2    .033       0
Levee=-1,0,30,-1,2,30,,
Bank Sta=0,2
XS Rating Curve= 0
Exp/Cntr=.3,.1

Type RM Length L Ch R = 1 ,20.024  ,24,24,24
#Sta/Elev= 8
     -10   17.89       0   17.89      .3   16.59     2.1   16.59     2.7   17.69
       6   17.69     6.2   16.89    16.2   16.89
#Mann= 3 , 0 , 0
     -10    .033       0       0    .033       0     2.7    .033       0
Levee=-1,0,30,-1,2.7,30,,
Bank Sta=0,2.7
XS Rating Curve= 0
Exp/Cntr=.3,.1

Type RM Length L Ch R = 1 ,20      ,25,25,25
#Sta/Elev= 10
   -10.5   16.06     -.5   16.06     -.2    16.6       0    16.6      .9   15.66
     1.5   15.66     1.6   16.66     4.8   16.66     5.3   15.16    15.3   15.16
#Mann= 3 , 0 , 0
   -10.5    .033       0       0    .033       0     1.6    .033       0
Levee=-1,0,20,-1,1.6,20,,
Bank Sta=0,1.6
XS Rating Curve= 0
Exp/Cntr=.3,.1

Type RM Length L Ch R = 1 ,19.025  ,25,25,25
#Sta/Elev= 8
     -10   15.84       0   15.84      .1   15.14     2.2   15.14     2.2   15.84
     4.8   15.84     5.9   14.94    15.9   14.94
#Mann= 3 , 0 , 0
     -10    .033       0       0    .033       0     2.2    .033       0
Levee=-1,0,20,-1,2.2,20,,
Bank Sta=0,2.2
XS Rating Curve= 0
Exp/Cntr=.3,.1

Type RM Length L Ch R = 1 ,19      ,16,16,16
#Sta/Elev= 16
   -16.4   15.74    -6.4   15.74    -6.2   15.94    -5.9   15.94    -5.4   15.44
    -4.8   15.44    -4.3   14.74      -4   14.74      -4   14.94       0   14.94
      .1   14.34     2.1   14.34     2.1   14.94     4.6   14.94     5.7   14.04
    15.7   14.04
#Mann= 3 , 0 , 0
   -16.4    .033       0       0    .033       0     2.1    .033       0
Levee=-1,0,20,-1,2.1,20,,
Bank Sta=0,2.1
XS Rating Curve= 0
Exp/Cntr=.3,.1

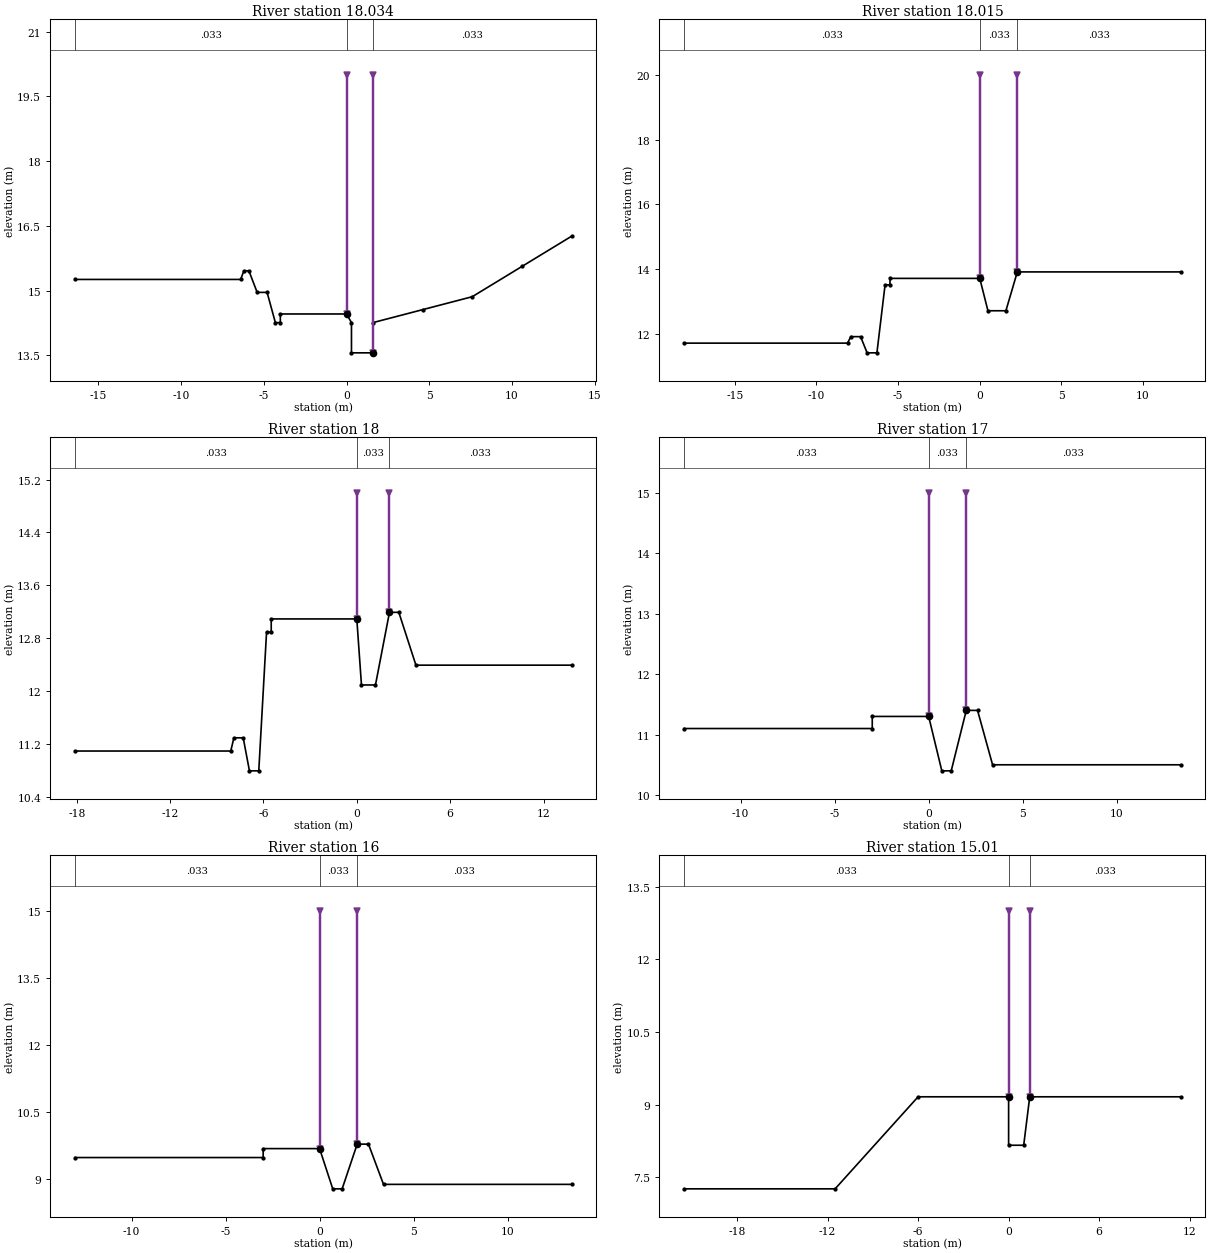
Type RM Length L Ch R = 1 ,18.034  ,19,19,19
#Sta/Elev= 18
   -16.4   15.26    -6.4   15.26    -6.2   15.46    -5.9   15.46    -5.4   14.96
    -4.8   14.96    -4.3   14.26      -4   14.26      -4   14.46       0   14.46
      .3   14.26      .3   13.56     1.6   13.56     1.6   14.26     4.6   14.56
     7.6   14.86    10.6   15.56    13.6   16.26
#Mann= 3 , 0 , 0
   -16.4    .033       0       0    .033       0     1.6    .033       0
Levee=-1,0,20,-1,1.6,20,,
Bank Sta=0,1.6
XS Rating Curve= 0
Exp/Cntr=.3,.1

Type RM Length L Ch R = 1 ,18.015  ,15,15,15
#Sta/Elev= 14
   -18.1   11.71    -8.1   11.71    -7.9   11.91    -7.3   11.91    -6.9   11.41
    -6.3   11.41    -5.8   13.51    -5.5   13.51    -5.5   13.71       0   13.71
      .5   12.71     1.6   12.71     2.3   13.91    12.3   13.91
#Mann= 3 , 0 , 0
   -18.1    .033       0       0    .033       0     2.3    .033       0
Levee=-1,0,20,-1,2.3,20,,
Bank Sta=0,2.3
XS Rating Curve= 0
Exp/Cntr=.3,.1

Type RM Length L Ch R = 1 ,18      ,50,50,50
#Sta/Elev= 16
   -18.1   11.09    -8.1   11.09    -7.9   11.29    -7.3   11.29    -6.9   10.79
    -6.3   10.79    -5.8   12.89    -5.5   12.89    -5.5   13.09       0   13.09
      .3   12.09     1.2   12.09     2.1   13.19     2.7   13.19     3.8   12.39
    13.8   12.39
#Mann= 3 , 0 , 0
   -18.1    .033       0       0    .033       0     2.1    .033       0
Levee=-1,0,15,-1,2.1,15,,
Bank Sta=0,2.1
XS Rating Curve= 0
Exp/Cntr=.3,.1

Type RM Length L Ch R = 1 ,17      ,50,50,50
#Sta/Elev= 10
     -13    11.1      -3    11.1      -3    11.3       0    11.3      .7    10.4
     1.2    10.4       2    11.4     2.6    11.4     3.4    10.5    13.4    10.5
#Mann= 3 , 0 , 0
     -13    .033       0       0    .033       0       2    .033       0
Levee=-1,0,15,-1,2,15,,
Bank Sta=0,2
XS Rating Curve= 0
Exp/Cntr=.3,.1

Type RM Length L Ch R = 1 ,16      ,40,40,40
#Sta/Elev= 10
     -13    9.48      -3    9.48      -3    9.68       0    9.68      .7    8.78
     1.2    8.78       2    9.78     2.6    9.78     3.4    8.88    13.4    8.88
#Mann= 3 , 0 , 0
     -13    .033       0       0    .033       0       2    .033       0
Levee=-1,0,15,-1,2,15,,
Bank Sta=0,2
XS Rating Curve= 0
Exp/Cntr=.3,.1

Type RM Length L Ch R = 1 ,15.01   ,10,10,10
#Sta/Elev= 8
   -21.5    7.26   -11.5    7.26      -6    9.16       0    9.16       0    8.16
       1    8.16     1.4    9.16    11.4    9.16
#Mann= 3 , 0 , 0
   -21.5    .033       0       0    .033       0     1.4    .033       0
Levee=-1,0,13,-1,1.4,13,,
Bank Sta=0,1.4
XS Rating Curve= 0
Exp/Cntr=.3,.1

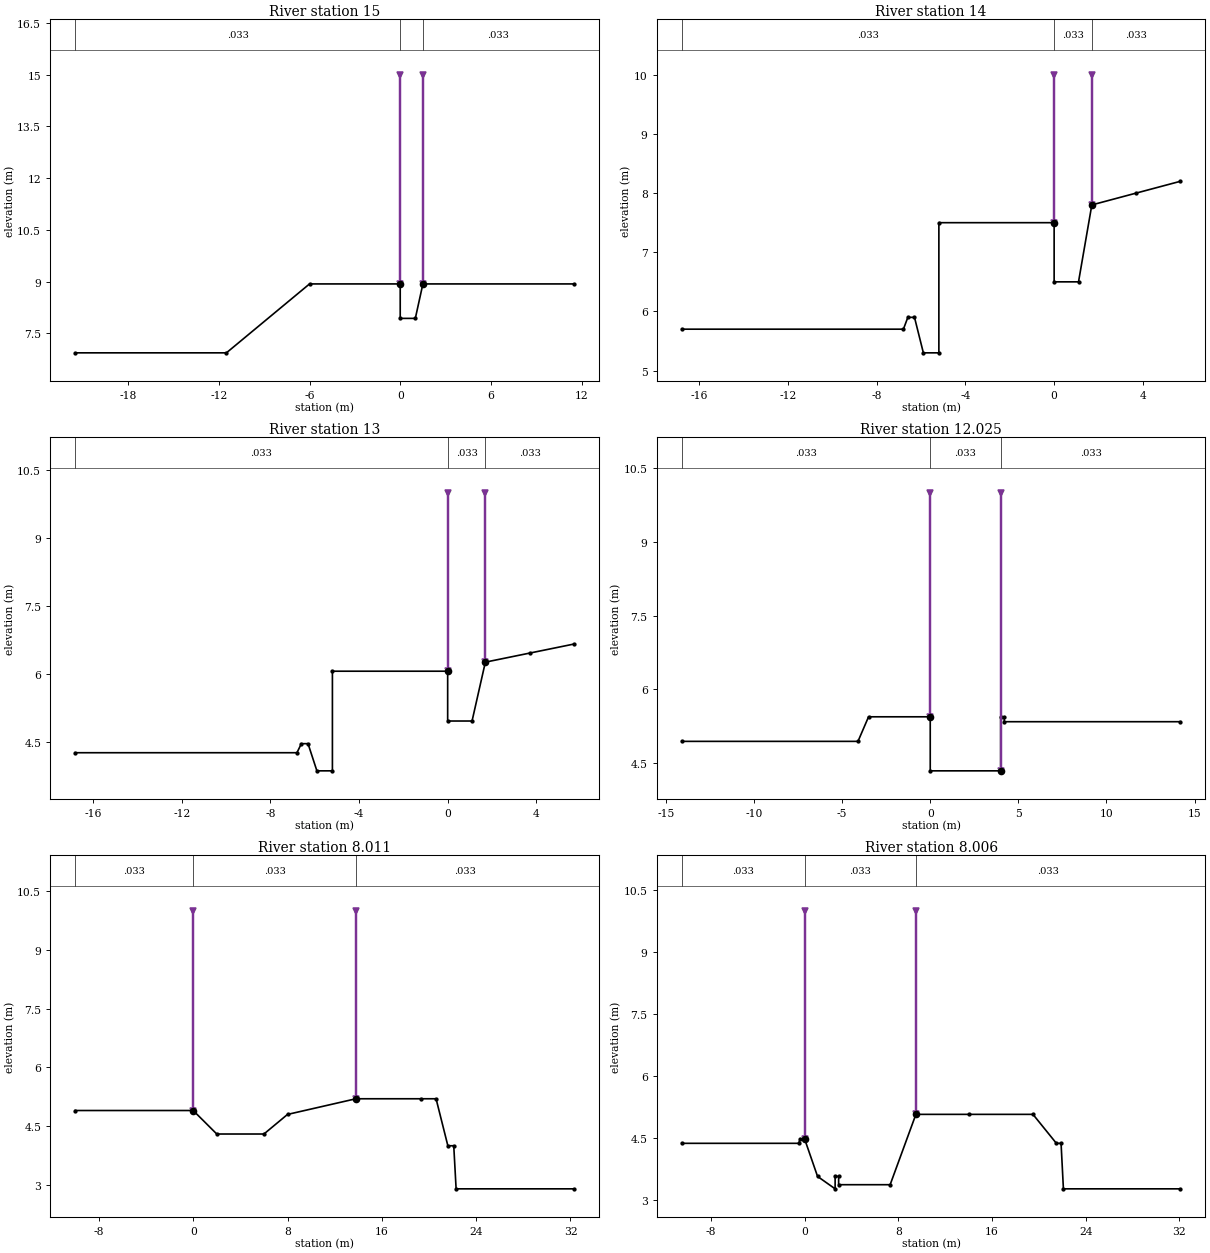
Type RM Length L Ch R = 1 ,15      ,50,50,50
#Sta/Elev= 8
   -21.5    6.93   -11.5    6.93      -6    8.93       0    8.93       0    7.93
       1    7.93     1.5    8.93    11.5    8.93
#Mann= 3 , 0 , 0
   -21.5    .033       0       0    .033       0     1.5    .033       0
Levee=-1,0,15,-1,1.5,15,,
Bank Sta=0,1.5
XS Rating Curve= 0
Exp/Cntr=.3,.1

Type RM Length L Ch R = 1 ,14      ,50,50,50
#Sta/Elev= 13
   -16.8     5.7    -6.8     5.7    -6.6     5.9    -6.3     5.9    -5.9     5.3
    -5.2     5.3    -5.2     7.5       0     7.5       0     6.5     1.1     6.5
     1.7     7.8     3.7       8     5.7     8.2
#Mann= 3 , 0 , 0
   -16.8    .033       0       0    .033       0     1.7    .033       0
Levee=-1,0,10,-1,1.7,10,,
Bank Sta=0,1.7
XS Rating Curve= 0
Exp/Cntr=.3,.1

Type RM Length L Ch R = 1 ,13      ,25,25,25
#Sta/Elev= 13
   -16.8    4.26    -6.8    4.26    -6.6    4.46    -6.3    4.46    -5.9    3.86
    -5.2    3.86    -5.2    6.06       0    6.06       0    4.96     1.1    4.96
     1.7    6.26     3.7    6.46     5.7    6.66
#Mann= 3 , 0 , 0
   -16.8    .033       0       0    .033       0     1.7    .033       0
Levee=-1,0,10,-1,1.7,10,,
Bank Sta=0,1.7
XS Rating Curve= 0
Exp/Cntr=.3,.1

Type RM Length L Ch R = 1 ,12.025  ,214,214,214
#Sta/Elev= 10
   -14.1    4.94    -4.1    4.94    -3.5    5.44       0    5.44       0    4.34
       4    4.34       4    5.44     4.2    5.44     4.2    5.34    14.2    5.34
#Mann= 3 , 0 , 0
   -14.1    .033       0       0    .033       0       4    .033       0
Levee=-1,0,10,-1,4,10,,
Bank Sta=0,4
XS Rating Curve= 0
Exp/Cntr=.3,.1

Type RM Length L Ch R = 1 ,8.011   ,5,5,5
#Sta/Elev= 12
     -10     4.9       0     4.9       2     4.3       6     4.3       8     4.8
    13.8     5.2    19.3     5.2    20.6     5.2    21.6       4    22.1       4
    22.3     2.9    32.3     2.9
#Mann= 3 , 0 , 0
     -10    .033       0       0    .033       0    13.8    .033       0
Levee=-1,0,10,-1,13.8,10,,
Bank Sta=0,13.8
XS Rating Curve= 0
Exp/Cntr=.3,.1

Type RM Length L Ch R = 1 ,8.006   ,6,6,6
#Sta/Elev= 17
   -10.5    4.38     -.5    4.38     -.4    4.48       0    4.48     1.1    3.58
     2.6    3.28     2.6    3.58     2.9    3.58     2.9    3.38     7.3    3.38
     9.5    5.08      14    5.08    19.5    5.08    21.5    4.38    21.9    4.38
    22.1    3.28    32.1    3.28
#Mann= 3 , 0 , 0
   -10.5    .033       0       0    .033       0     9.5    .033       0
Levee=-1,0,10,-1,9.5,10,,
Bank Sta=0,9.5
XS Rating Curve= 0
Exp/Cntr=.3,.1

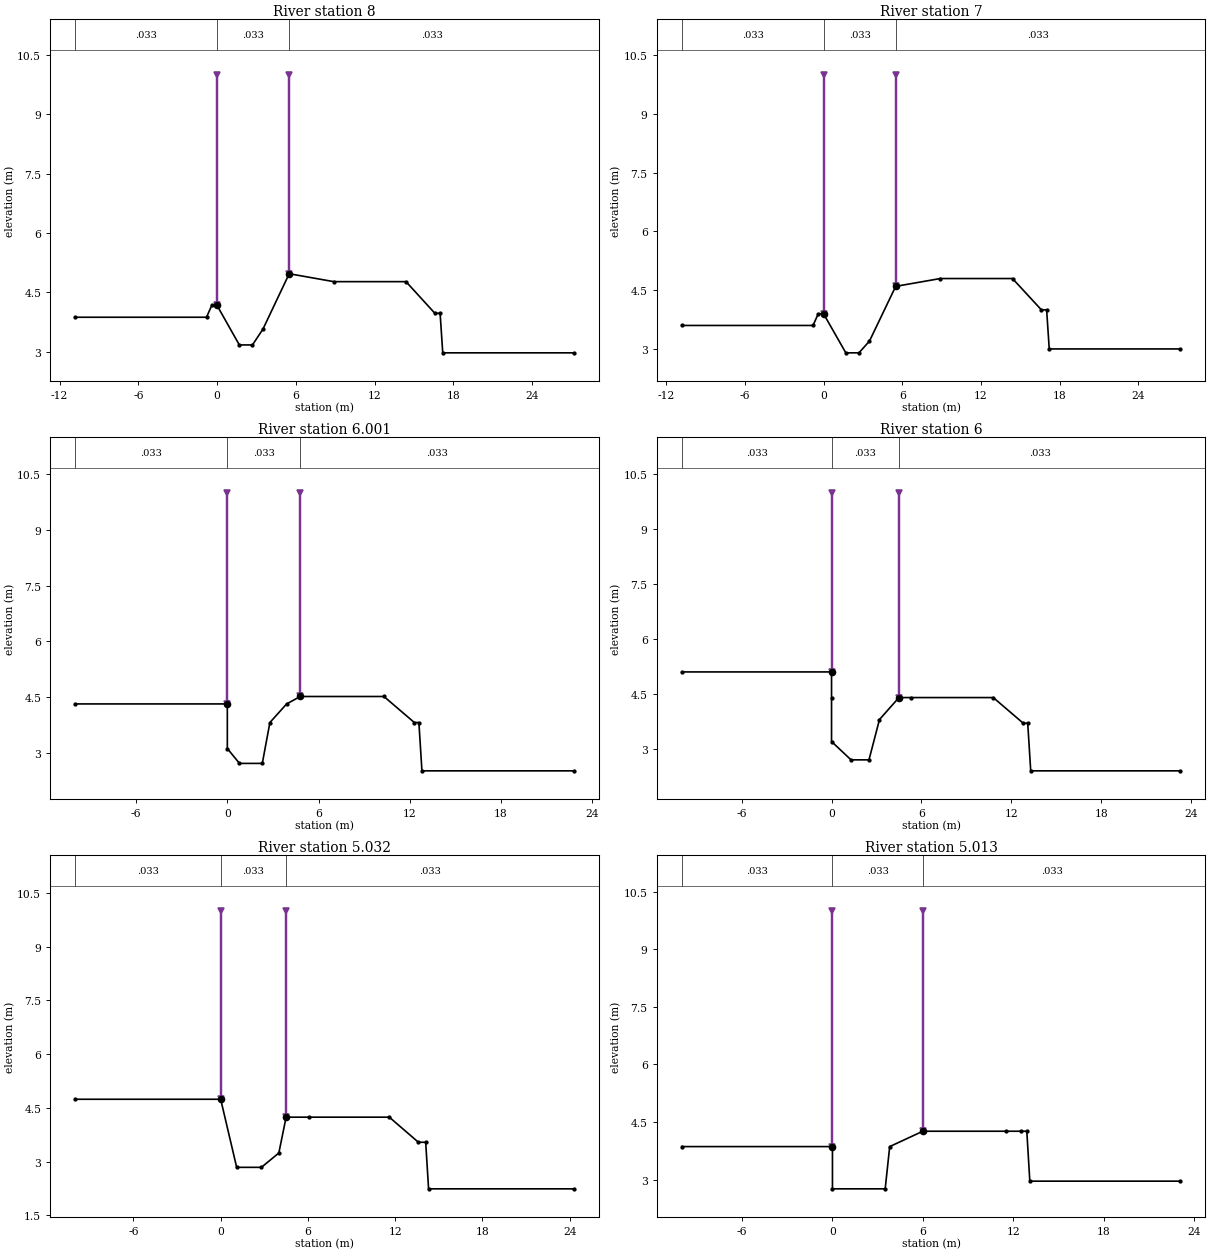
Type RM Length L Ch R = 1 ,8       ,50,50,50
#Sta/Elev= 14
   -10.8    3.87     -.8    3.87     -.4    4.17       0    4.17     1.7    3.17
     2.7    3.17     3.5    3.57     5.5    4.97     8.9    4.77    14.4    4.77
    16.6    3.97      17    3.97    17.2    2.97    27.2    2.97
#Mann= 3 , 0 , 0
   -10.8    .033       0       0    .033       0     5.5    .033       0
Levee=-1,0,10,-1,5.5,10,,
Bank Sta=0,5.5
XS Rating Curve= 0
Exp/Cntr=.3,.1

Type RM Length L Ch R = 1 ,7       ,49,49,49
#Sta/Elev= 14
   -10.8    3.59     -.8    3.59     -.4    3.89       0    3.89     1.7    2.89
     2.7    2.89     3.5    3.19     5.5    4.59     8.9    4.79    14.4    4.79
    16.6    3.99      17    3.99    17.2    2.99    27.2    2.99
#Mann= 3 , 0 , 0
   -10.8    .033       0       0    .033       0     5.5    .033       0
Levee=-1,0,10,-1,5.5,10,,
Bank Sta=0,5.5
XS Rating Curve= 0
Exp/Cntr=.3,.1

Type RM Length L Ch R = 1 ,6.001   ,1,1,1
#Sta/Elev= 13
     -10    4.32       0    4.32       0    3.12      .8    2.72     2.3    2.72
     2.8    3.82     3.9    4.32     4.8    4.52    10.3    4.52    12.3    3.82
    12.6    3.82    12.8    2.52    22.8    2.52
#Mann= 3 , 0 , 0
     -10    .033       0       0    .033       0     4.8    .033       0
Levee=-1,0,10,-1,4.8,10,,
Bank Sta=0,4.8
XS Rating Curve= 0
Exp/Cntr=.3,.1

Type RM Length L Ch R = 1 ,6       ,18,18,18
#Sta/Elev= 14
     -10    5.11       0    5.11       0    4.41       0    3.21     1.3    2.71
     2.5    2.71     3.2    3.81     4.5    4.41     5.3    4.41    10.8    4.41
    12.8    3.71    13.1    3.71    13.3    2.41    23.3    2.41
#Mann= 3 , 0 , 0
     -10    .033       0       0    .033       0     4.5    .033       0
Levee=-1,0,10,-1,4.5,10,,
Bank Sta=0,4.5
XS Rating Curve= 0
Exp/Cntr=.3,.1

Type RM Length L Ch R = 1 ,5.032   ,19,19,19
#Sta/Elev= 12
     -10    4.74       0    4.74     1.1    2.84     2.8    2.84       4    3.24
     4.5    4.24     6.1    4.24    11.6    4.24    13.6    3.54    14.1    3.54
    14.3    2.24    24.3    2.24
#Mann= 3 , 0 , 0
     -10    .033       0       0    .033       0     4.5    .033       0
Levee=-1,0,10,-1,4.5,10,,
Bank Sta=0,4.5
XS Rating Curve= 0
Exp/Cntr=.3,.1

Type RM Length L Ch R = 1 ,5.013   ,13,13,13
#Sta/Elev= 11
     -10    3.86       0    3.86       0    2.76     3.5    2.76     3.8    3.86
       6    4.26    11.5    4.26    12.5    4.26    12.9    4.26    13.1    2.96
    23.1    2.96
#Mann= 3 , 0 , 0
     -10    .033       0       0    .033       0       6    .033       0
Levee=-1,0,10,-1,6,10,,
Bank Sta=0,6
XS Rating Curve= 0
Exp/Cntr=.3,.1

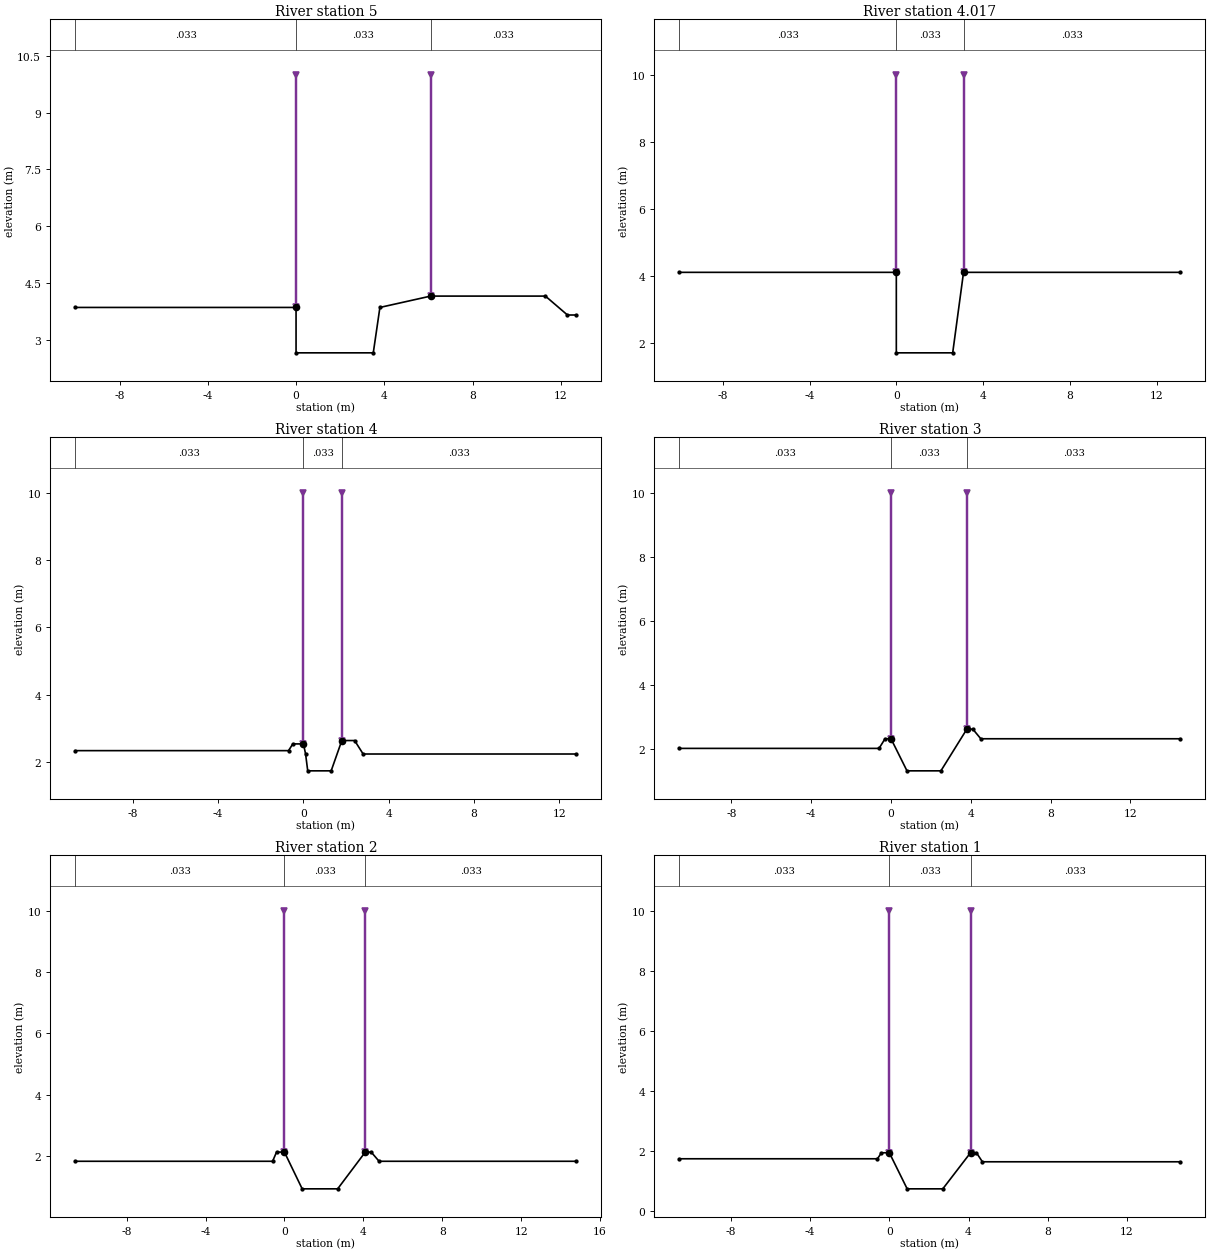
Type RM Length L Ch R = 1 ,5       ,33,33,33
#Sta/Elev= 9
     -10    3.85       0    3.85       0    2.65     3.5    2.65     3.8    3.85
     6.1    4.15    11.3    4.15    12.3    3.65    12.7    3.65
#Mann= 3 , 0 , 0
     -10    .033       0       0    .033       0     6.1    .033       0
Levee=-1,0,10,-1,6.1,10,,
Bank Sta=0,6.1
XS Rating Curve= 0
Exp/Cntr=.3,.1

Type RM Length L Ch R = 1 ,4.017   ,17,17,17
#Sta/Elev= 6
     -10    4.11       0    4.11       0    1.71     2.6    1.71     3.1    4.11
    13.1    4.11
#Mann= 3 , 0 , 0
     -10    .033       0       0    .033       0     3.1    .033       0
Levee=-1,0,10,-1,3.1,10,,
Bank Sta=0,3.1
XS Rating Curve= 0
Exp/Cntr=.3,.1

Type RM Length L Ch R = 1 ,4       ,50,50,50
#Sta/Elev= 11
   -10.7    2.34     -.7    2.34     -.5    2.54       0    2.54      .1    2.24
      .2    1.74     1.3    1.74     1.8    2.64     2.4    2.64     2.8    2.24
    12.8    2.24
#Mann= 3 , 0 , 0
   -10.7    .033       0       0    .033       0     1.8    .033       0
Levee=-1,0,10,-1,1.8,10,,
Bank Sta=0,1.8
XS Rating Curve= 0
Exp/Cntr=.3,.1

Type RM Length L Ch R = 1 ,3       ,50,50,50
#Sta/Elev= 10
   -10.6    2.03     -.6    2.03     -.3    2.33       0    2.33      .8    1.33
     2.5    1.33     3.8    2.63     4.1    2.63     4.5    2.33    14.5    2.33
#Mann= 3 , 0 , 0
   -10.6    .033       0       0    .033       0     3.8    .033       0
Levee=-1,0,10,-1,3.8,10,,
Bank Sta=0,3.8
XS Rating Curve= 0
Exp/Cntr=.3,.1

Type RM Length L Ch R = 1 ,2       ,50,50,50
#Sta/Elev= 10
   -10.6    1.82     -.6    1.82     -.4    2.12       0    2.12      .9     .92
     2.7     .92     4.1    2.12     4.4    2.12     4.8    1.82    14.8    1.82
#Mann= 3 , 0 , 0
   -10.6    .033       0       0    .033       0     4.1    .033       0
Levee=-1,0,10,-1,4.1,10,,
Bank Sta=0,4.1
XS Rating Curve= 0
Exp/Cntr=.3,.1

Type RM Length L Ch R = 1 ,1       ,50,50,50
#Sta/Elev= 10
   -10.6    1.75     -.6    1.75     -.4    1.95       0    1.95      .9     .75
     2.7     .75     4.1    1.95     4.4    1.95     4.7    1.65    14.7    1.65
#Mann= 3 , 0 , 0
   -10.6    .033       0       0    .033       0     4.1    .033       0
Levee=-1,0,10,-1,4.1,10,,
Bank Sta=0,4.1
XS Rating Curve= 0
Exp/Cntr=.3,.1

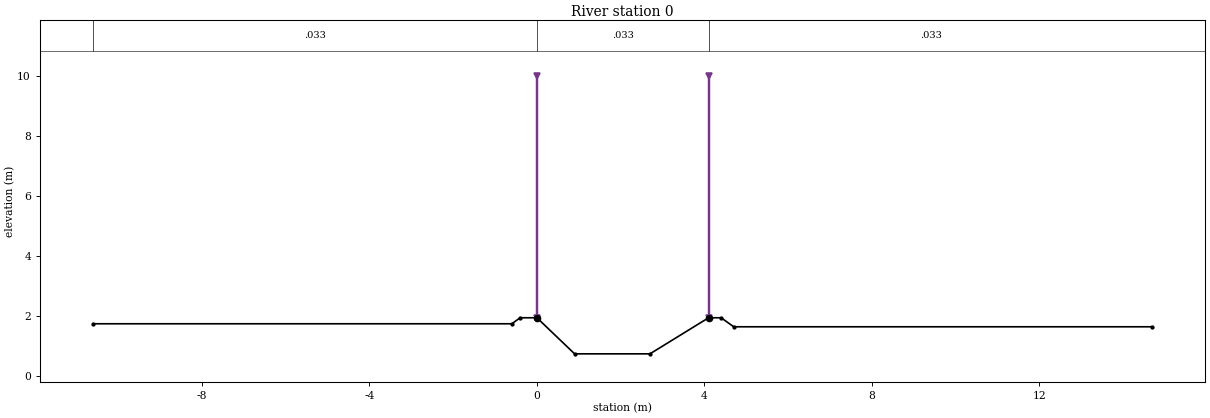
Type RM Length L Ch R = 1 ,0       ,0,0,0
#Sta/Elev= 10
   -10.6    1.75     -.6    1.75     -.4    1.95       0    1.95      .9     .75
     2.7     .75     4.1    1.95     4.4    1.95     4.7    1.65    14.7    1.65
#Mann= 3 , 0 , 0
   -10.6    .033       0       0    .033       0     4.1    .033       0
Levee=-1,0,10,-1,4.1,10,,
Bank Sta=0,4.1
XS Rating Curve= 0
Exp/Cntr=.3,.1

Chan Stop Cuts=-1