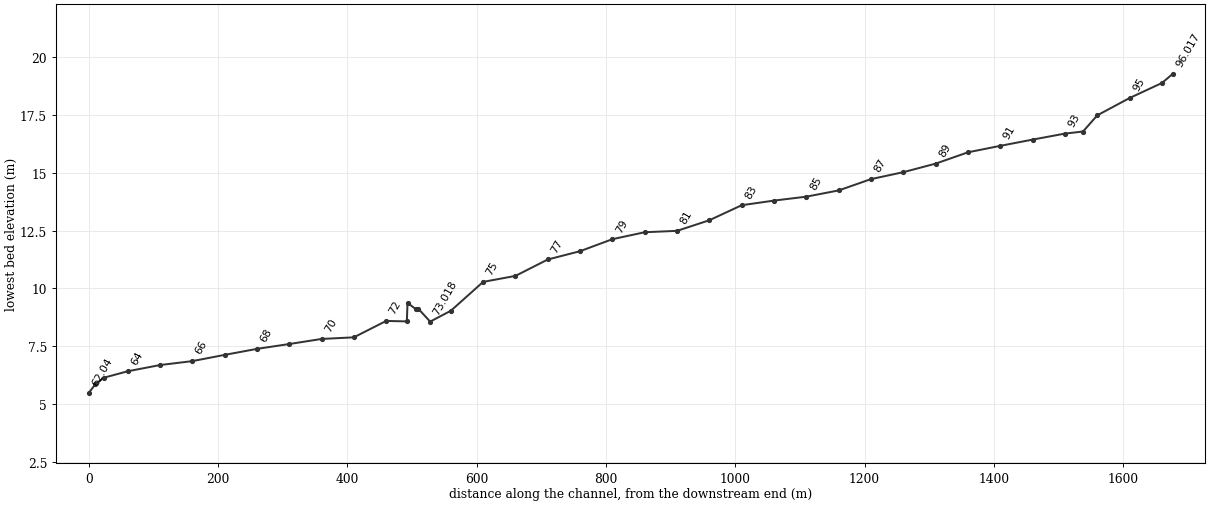
--- dsc.prj (project) ---

Proj Title=dongsan
Current Plan=p01
Default Exp/Contr=.3,.1
SI Units
Geom File=g01
Flow File=f01
Plan File=p01
Y Axis Title=Elevation
X Axis Title(PF)=Main Channel Distance
X Axis Title(XS)=Station
BEGIN DESCRIPTION:
           BACK WATER COMPUTATION
      APPLICATION OF HEC-2 BY Samju Construction Engineering
      dongsan-ch: 10,20,30,50,80 yr
END DESCRIPTION:
DSS Export Rating Curves= 0
DSS Export Rating Curve Sorted= 0
DSS Export Volume Flow Curves= 0
DXF OffsetX= 0
DXF OffsetY= 0
DXF ScaleX= 1
DXF ScaleY= 10

--- dsc.p01 (plan) ---

Plan Title=Imported Plan 01
Version=Version 3.0.1  Mar 2001
Short Identifier=Imported Pla
Geom File=g01
Flow File=f01
Subcritical Flow
K Sum by GR= 0
Std Step Tol= 0.003
Critical Tol= 0.003
Num of Std Step Trials= 20
Max Error Tol= 0.1
Flow Tol Ratio= 0.001
Split Flow NTrial= 30
Split Flow Tol= 0.02
Split Flow Ratio= 0.02
Log Output Level= 0
Friction Slope Method= 1
Unsteady Friction Slope Method= 2
Parabolic Critical Depth
Global Vel Dist= 0 , 0 , 0
Global Log Level= 0
CheckData=True
Encroach Param=-1 ,0,0, 0
Computation Interval=1HOUR
Output Interval=1HOUR
Run HTab= 0
Run UNet= 0
Run PostProcess= 0
UNET Theta= 1
UNET ZTol= 0.02
UNET ZSATol= 0.1
UNET MxIter= 20
UNET MaxInSteps= 20
UNET DtIC= 0
UNET DtMin= 0
UNET MaxCRTS= 20
UNET WFStab= 2
UNET SFStab= 1
UNET WFX= 1
UNET SFX= 1
UNET Convert EG Bridges=-1
UNET Use Existing IB Tables=-1
Instantaneous Interval=1HOUR
Write IC File= 0
Write Velocity= 0
Write Detailed= 0

--- dsc.f01 (steady flow) ---

Flow Title=Imported Flow 01
Version=Version 3.0.1  Mar 2001
Number of Profiles= 5
Profile Names=10yr,20yr,30yr,50yr,80yr
River Rch & RM=RIVER-1,Reach-1         ,96.017
    39.3   43.31   45.65    48.6   51.31
River Rch & RM=RIVER-1,Reach-1         ,61
   48.84   53.85   56.78   60.47   63.87
River Rch & RM=RIVER-1,Reach-1         ,44
   64.94   71.66   75.58   80.53   85.08
River Rch & RM=RIVER-1,Reach-1         ,13
   69.44   76.65   80.87   86.18   91.07
River Rch & RM=DONGSAN,DONGSAN         ,96.017
    39.3   43.31   45.65    48.6   51.31
River Rch & RM=DONGSAN,DONGSAN         ,61
   48.84   53.85   56.78   60.47   63.87
River Rch & RM=DONGSAN,DONGSAN         ,44
   64.94   71.66   75.58   80.53   85.08
River Rch & RM=DONGSAN,DONGSAN         ,13
   69.44   76.65   80.87   86.18   91.07
Boundary for River Rch & Prof#=DONGSAN,DONGSAN         , 1
Up Type= 0
Dn Type= 3
Dn Slope=.004
Boundary for River Rch & Prof#=DONGSAN,DONGSAN         , 2
Up Type= 0
Dn Type= 3
Dn Slope=.004
Boundary for River Rch & Prof#=DONGSAN,DONGSAN         , 3
Up Type= 0
Dn Type= 3
Dn Slope=.004
Boundary for River Rch & Prof#=DONGSAN,DONGSAN         , 4
Up Type= 0
Dn Type= 3
Dn Slope=.004
Boundary for River Rch & Prof#=DONGSAN,DONGSAN         , 5
Up Type= 0
Dn Type= 3
Dn Slope=.004
DSS Import GetInterval= 0
DSS Import GetPeak= 0
DSS Import FillOption= 0

--- dsc.g01 (geometry) ---

Geom Title=Imported Geom 01
Version=Version 3.0.1  Mar 2001

River Reach=DONGSAN         ,DONGSAN
Reach XY= 2
              .5             .95              .5             .05

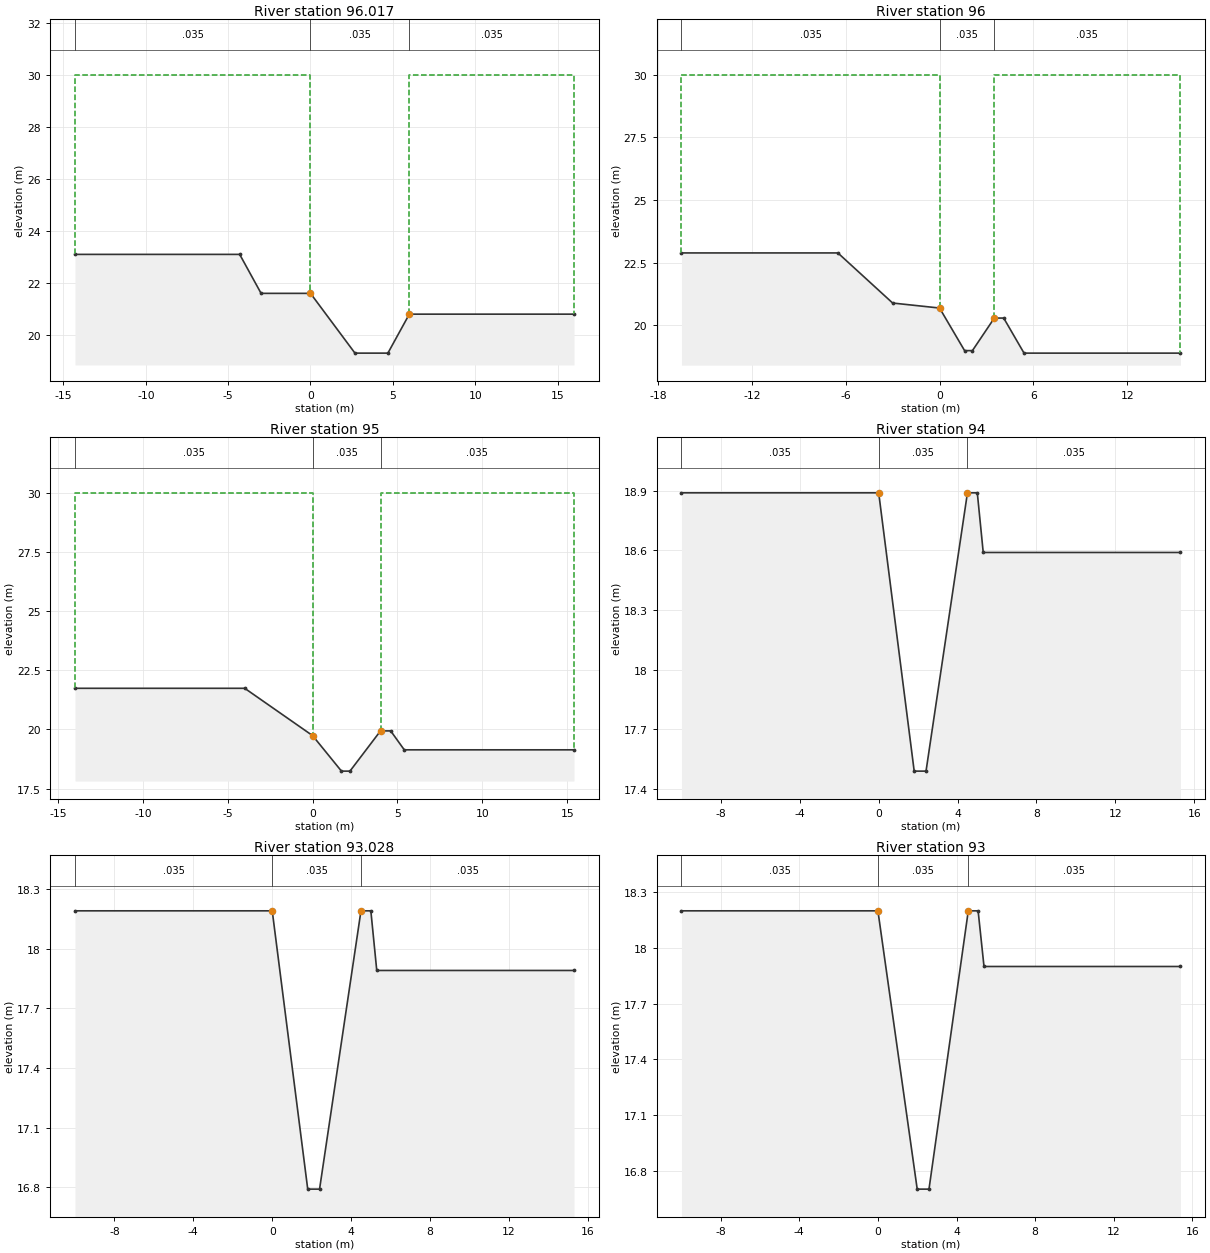
Type RM Length L Ch R = 1 ,96.017  ,17,17,17
#Sta/Elev= 8
   -14.3   23.09    -4.3   23.09      -3   21.59       0   21.59     2.7   19.29
     4.7   19.29       6   20.79      16   20.79
#Mann= 3 , 0 , 0
   -14.3    .035       0       0    .035       0       6    .035       0
#XS Ineff= 2 , 0
               0      30       6              30
Permanent Ineff=
       F       F
#Block Obstruct= 2 , 0
                               6
Bank Sta=0,6
XS Rating Curve= 0
Exp/Cntr=.3,.1

Type RM Length L Ch R = 1 ,96      ,50,50,50
#Sta/Elev= 10
   -16.5   22.89    -6.5   22.89      -3   20.89       0   20.69     1.6   18.99
     2.1   18.99     3.5   20.29     4.1   20.29     5.4   18.89    15.4   18.89
#Mann= 3 , 0 , 0
   -16.5    .035       0       0    .035       0     3.5    .035       0
#XS Ineff= 2 , 0
               0      30     3.5              30
Permanent Ineff=
       F       F
#Block Obstruct= 2 , 0
                             3.5
Bank Sta=0,3.5
XS Rating Curve= 0
Exp/Cntr=.3,.1

Type RM Length L Ch R = 1 ,95      ,50,50,50
#Sta/Elev= 9
     -14   21.74      -4   21.74       0   19.74     1.7   18.24     2.2   18.24
       4   19.94     4.6   19.94     5.4   19.14    15.4   19.14
#Mann= 3 , 0 , 0
     -14    .035       0       0    .035       0       4    .035       0
#XS Ineff= 2 , 0
               0      30       4              30
Permanent Ineff=
       F       F
#Block Obstruct= 2 , 0
                               4
Bank Sta=0,4
XS Rating Curve= 0
Exp/Cntr=.3,.1

Type RM Length L Ch R = 1 ,94      ,22,22,22
#Sta/Elev= 8
     -10   18.89       0   18.89     1.8   17.49     2.4   17.49     4.5   18.89
       5   18.89     5.3   18.59    15.3   18.59
#Mann= 3 , 0 , 0
     -10    .035       0       0    .035       0     4.5    .035       0
#XS Ineff= 2 , 0
               0      30     4.5              30
Permanent Ineff=
       F       F
#Block Obstruct= 2 , 0
                             4.5
Bank Sta=0,4.5
XS Rating Curve= 0
Exp/Cntr=.3,.1

Type RM Length L Ch R = 1 ,93.028  ,28,28,28
#Sta/Elev= 8
     -10   18.19       0   18.19     1.8   16.79     2.4   16.79     4.5   18.19
       5   18.19     5.3   17.89    15.3   17.89
#Mann= 3 , 0 , 0
     -10    .035       0       0    .035       0     4.5    .035       0
#XS Ineff= 2 , 0
               0      30     4.5              30
Permanent Ineff=
       F       F
#Block Obstruct= 2 , 0
                             4.5
Bank Sta=0,4.5
XS Rating Curve= 0
Exp/Cntr=.3,.1

Type RM Length L Ch R = 1 ,93      ,50,50,50
#Sta/Elev= 8
     -10    18.2       0    18.2       2    16.7     2.6    16.7     4.6    18.2
     5.1    18.2     5.4    17.9    15.4    17.9
#Mann= 3 , 0 , 0
     -10    .035       0       0    .035       0     4.6    .035       0
#XS Ineff= 2 , 0
               0      30     4.6              30
Permanent Ineff=
       F       F
#Block Obstruct= 2 , 0
                             4.6
Bank Sta=0,4.6
XS Rating Curve= 0
Exp/Cntr=.3,.1

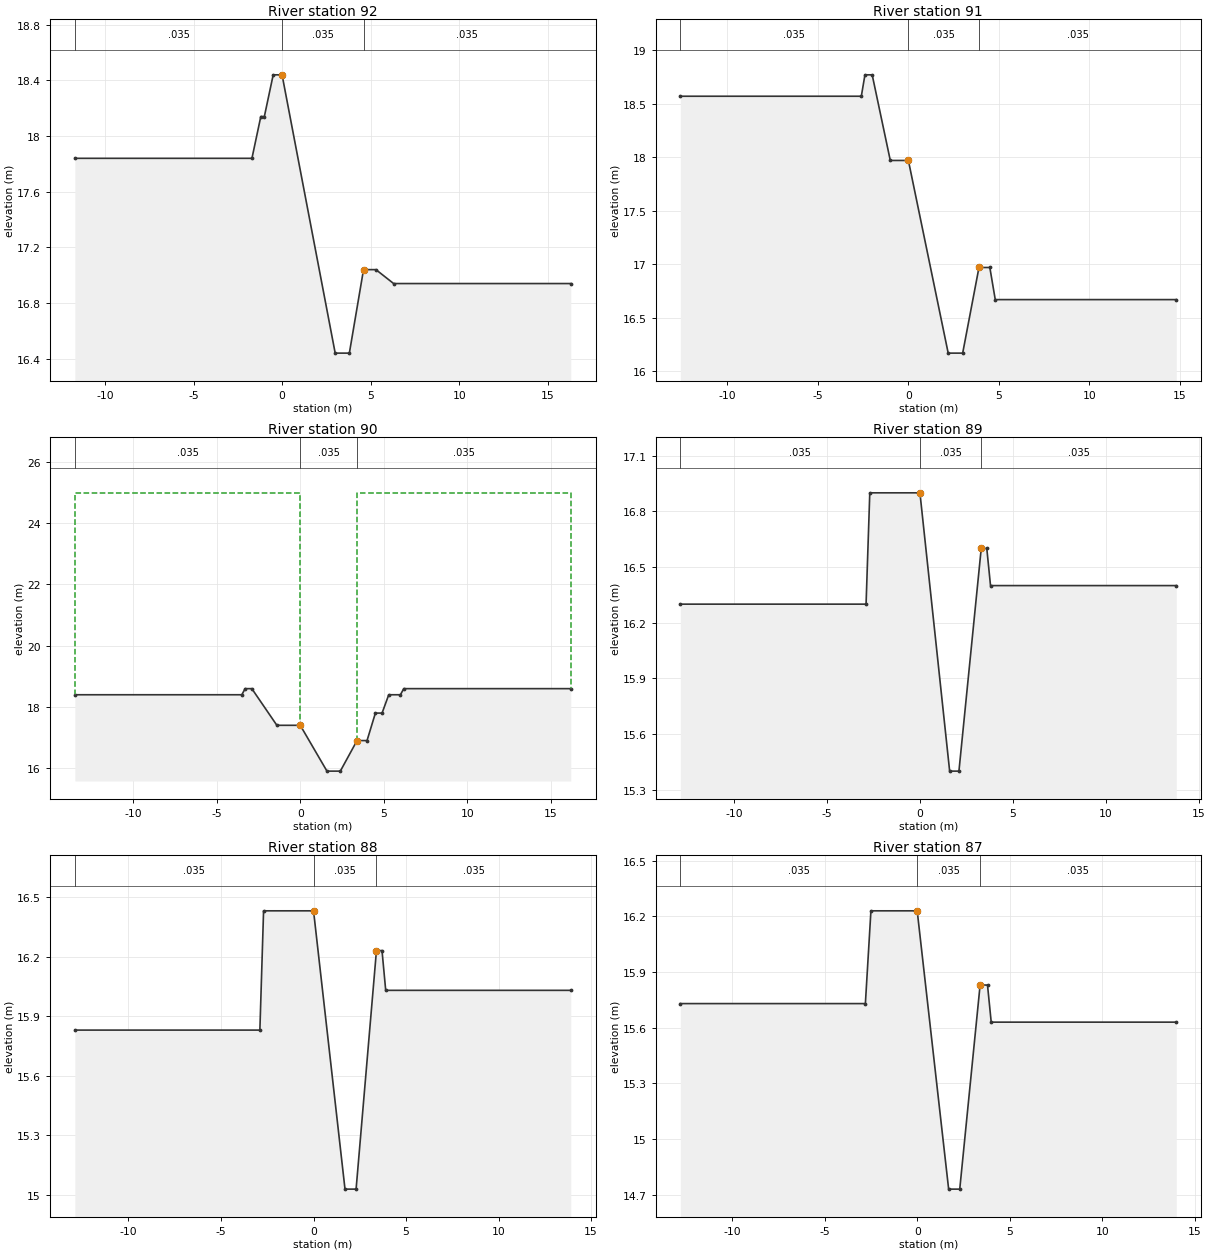
Type RM Length L Ch R = 1 ,92      ,50,50,50
#Sta/Elev= 12
   -11.7   17.84    -1.7   17.84    -1.2   18.14      -1   18.14     -.5   18.44
       0   18.44       3   16.44     3.8   16.44     4.6   17.04     5.3   17.04
     6.3   16.94    16.3   16.94
#Mann= 3 , 0 , 0
   -11.7    .035       0       0    .035       0     4.6    .035       0
#XS Ineff= 2 , 0
               0      30     4.6              30
Permanent Ineff=
       F       F
#Block Obstruct= 2 , 0
                             4.6
Bank Sta=0,4.6
XS Rating Curve= 0
Exp/Cntr=.3,.1

Type RM Length L Ch R = 1 ,91      ,50,50,50
#Sta/Elev= 12
   -12.6   18.57    -2.6   18.57    -2.4   18.77      -2   18.77      -1   17.97
       0   17.97     2.2   16.17       3   16.17     3.9   16.97     4.5   16.97
     4.8   16.67    14.8   16.67
#Mann= 3 , 0 , 0
   -12.6    .035       0       0    .035       0     3.9    .035       0
#XS Ineff= 2 , 0
               0      30     3.9              30
Permanent Ineff=
       F       F
#Block Obstruct= 2 , 0
                             3.9
Bank Sta=0,3.9
XS Rating Curve= 0
Exp/Cntr=.3,.1

Type RM Length L Ch R = 1 ,90      ,50,50,50
#Sta/Elev= 16
   -13.5   18.39    -3.5   18.39    -3.3   18.59    -2.9   18.59    -1.4   17.39
       0   17.39     1.6   15.89     2.4   15.89     3.4   16.89       4   16.89
     4.5   17.79     4.9   17.79     5.3   18.39       6   18.39     6.2   18.59
    16.2   18.59
#Mann= 3 , 0 , 0
   -13.5    .035       0       0    .035       0     3.4    .035       0
#XS Ineff= 2 , 0
               0      25     3.4              25
Permanent Ineff=
       F       F
#Block Obstruct= 2 , 0
                             3.4
Bank Sta=0,3.4
XS Rating Curve= 0
Exp/Cntr=.3,.1

Type RM Length L Ch R = 1 ,89      ,50,50,50
#Sta/Elev= 10
   -12.9    16.3    -2.9    16.3    -2.7    16.9       0    16.9     1.6    15.4
     2.1    15.4     3.3    16.6     3.6    16.6     3.8    16.4    13.8    16.4
#Mann= 3 , 0 , 0
   -12.9    .035       0       0    .035       0     3.3    .035       0
#XS Ineff= 2 , 0
               0      25     3.3              25
Permanent Ineff=
       F       F
#Block Obstruct= 2 , 0
                             3.3
Bank Sta=0,3.3
XS Rating Curve= 0
Exp/Cntr=.3,.1

Type RM Length L Ch R = 1 ,88      ,50,50,50
#Sta/Elev= 10
   -12.9   15.83    -2.9   15.83    -2.7   16.43       0   16.43     1.7   15.03
     2.3   15.03     3.4   16.23     3.7   16.23     3.9   16.03    13.9   16.03
#Mann= 3 , 0 , 0
   -12.9    .035       0       0    .035       0     3.4    .035       0
#XS Ineff= 2 , 0
               0      25     3.4              25
Permanent Ineff=
       F       F
#Block Obstruct= 2 , 0
                             3.4
Bank Sta=0,3.4
XS Rating Curve= 0
Exp/Cntr=.3,.1

Type RM Length L Ch R = 1 ,87      ,50,50,50
#Sta/Elev= 10
   -12.8   15.73    -2.8   15.73    -2.5   16.23       0   16.23     1.7   14.73
     2.3   14.73     3.4   15.83     3.8   15.83       4   15.63      14   15.63
#Mann= 3 , 0 , 0
   -12.8    .035       0       0    .035       0     3.4    .035       0
#XS Ineff= 2 , 0
               0      25     3.4              25
Permanent Ineff=
       F       F
#Block Obstruct= 2 , 0
                             3.4
Bank Sta=0,3.4
XS Rating Curve= 0
Exp/Cntr=.3,.1

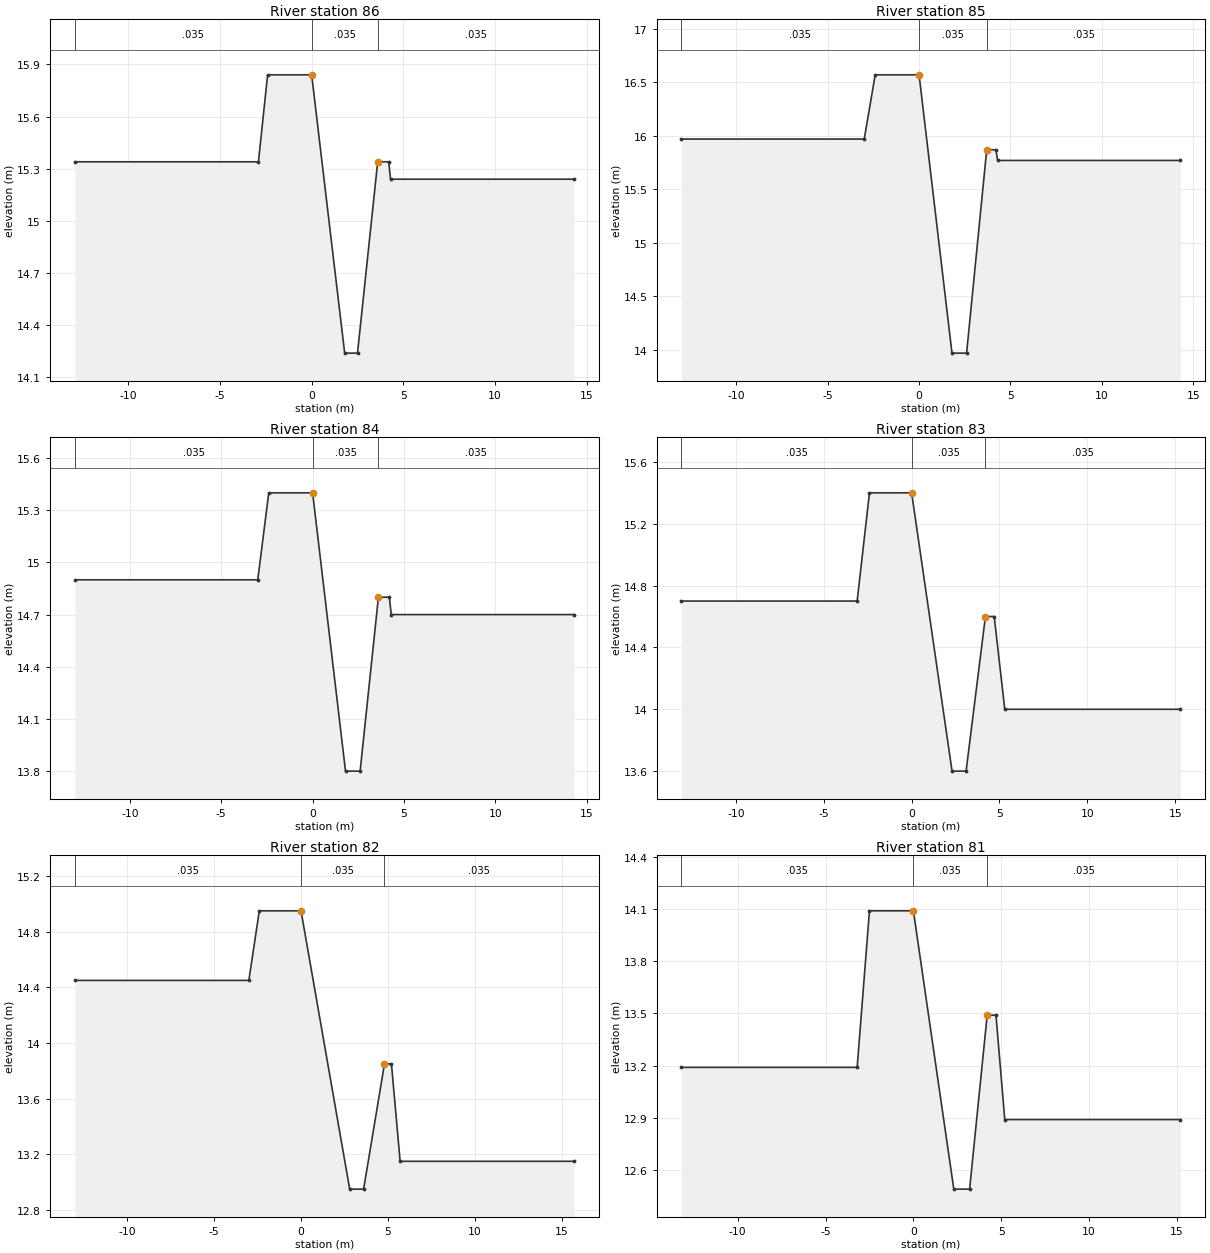
Type RM Length L Ch R = 1 ,86      ,50,50,50
#Sta/Elev= 10
   -12.9   15.34    -2.9   15.34    -2.4   15.84       0   15.84     1.8   14.24
     2.5   14.24     3.6   15.34     4.2   15.34     4.3   15.24    14.3   15.24
#Mann= 3 , 0 , 0
   -12.9    .035       0       0    .035       0     3.6    .035       0
#XS Ineff= 2 , 0
               0      25     3.6              25
Permanent Ineff=
       F       F
#Block Obstruct= 2 , 0
                             3.6
Bank Sta=0,3.6
XS Rating Curve= 0
Exp/Cntr=.3,.1

Type RM Length L Ch R = 1 ,85      ,50,50,50
#Sta/Elev= 10
     -13   15.97      -3   15.97    -2.4   16.57       0   16.57     1.8   13.97
     2.6   13.97     3.7   15.87     4.2   15.87     4.3   15.77    14.3   15.77
#Mann= 3 , 0 , 0
     -13    .035       0       0    .035       0     3.7    .035       0
#XS Ineff= 2 , 0
               0      25     3.7              25
Permanent Ineff=
       F       F
#Block Obstruct= 2 , 0
                             3.7
Bank Sta=0,3.7
XS Rating Curve= 0
Exp/Cntr=.3,.1

Type RM Length L Ch R = 1 ,84      ,50,50,50
#Sta/Elev= 10
     -13    14.9      -3    14.9    -2.4    15.4       0    15.4     1.8    13.8
     2.6    13.8     3.6    14.8     4.2    14.8     4.3    14.7    14.3    14.7
#Mann= 3 , 0 , 0
     -13    .035       0       0    .035       0     3.6    .035       0
#XS Ineff= 2 , 0
               0      25     3.6              25
Permanent Ineff=
       F       F
#Block Obstruct= 2 , 0
                             3.6
Bank Sta=0,3.6
XS Rating Curve= 0
Exp/Cntr=.3,.1

Type RM Length L Ch R = 1 ,83      ,50,50,50
#Sta/Elev= 10
   -13.1    14.7    -3.1    14.7    -2.4    15.4       0    15.4     2.3    13.6
     3.1    13.6     4.2    14.6     4.7    14.6     5.3      14    15.3      14
#Mann= 3 , 0 , 0
   -13.1    .035       0       0    .035       0     4.2    .035       0
#XS Ineff= 2 , 0
               0      25     4.2              25
Permanent Ineff=
       F       F
#Block Obstruct= 2 , 0
                             4.2
Bank Sta=0,4.2
XS Rating Curve= 0
Exp/Cntr=.3,.1

Type RM Length L Ch R = 1 ,82      ,50,50,50
#Sta/Elev= 10
     -13   14.45      -3   14.45    -2.4   14.95       0   14.95     2.8   12.95
     3.6   12.95     4.8   13.85     5.2   13.85     5.7   13.15    15.7   13.15
#Mann= 3 , 0 , 0
     -13    .035       0       0    .035       0     4.8    .035       0
#XS Ineff= 2 , 0
               0      25     4.8              25
Permanent Ineff=
       F       F
#Block Obstruct= 2 , 0
                             4.8
Bank Sta=0,4.8
XS Rating Curve= 0
Exp/Cntr=.3,.1

Type RM Length L Ch R = 1 ,81      ,50,50,50
#Sta/Elev= 10
   -13.2   13.19    -3.2   13.19    -2.5   14.09       0   14.09     2.3   12.49
     3.2   12.49     4.2   13.49     4.7   13.49     5.2   12.89    15.2   12.89
#Mann= 3 , 0 , 0
   -13.2    .035       0       0    .035       0     4.2    .035       0
#XS Ineff= 2 , 0
               0      25     4.2              25
Permanent Ineff=
       F       F
#Block Obstruct= 2 , 0
                             4.2
Bank Sta=0,4.2
XS Rating Curve= 0
Exp/Cntr=.3,.1

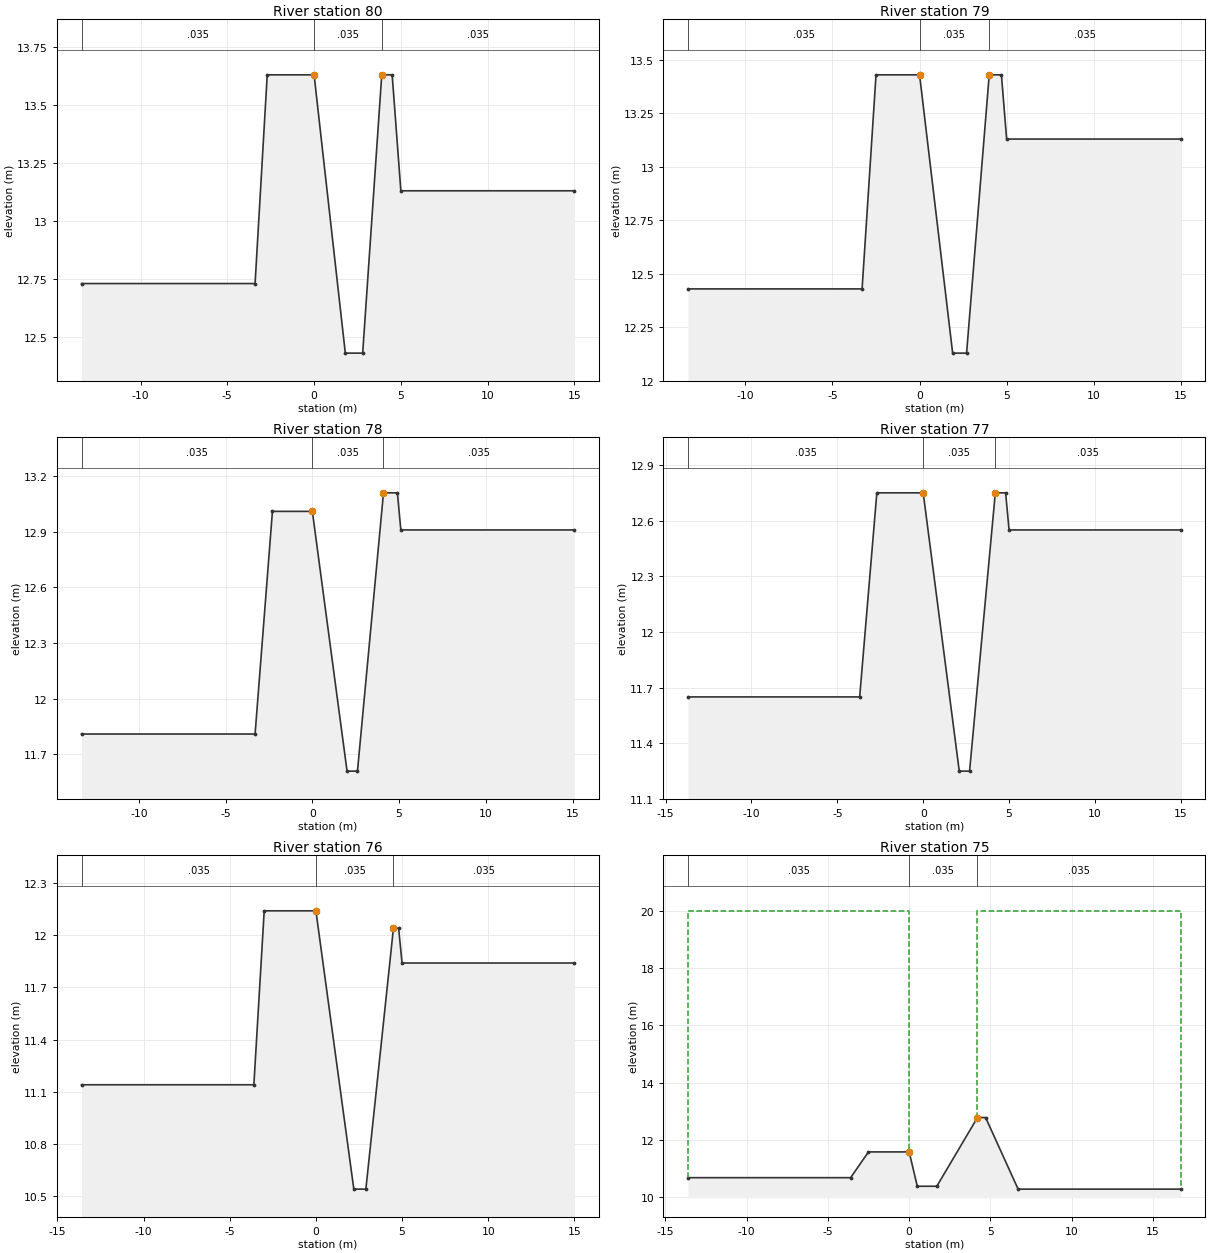
Type RM Length L Ch R = 1 ,80      ,50,50,50
#Sta/Elev= 10
   -13.4   12.73    -3.4   12.73    -2.7   13.63       0   13.63     1.8   12.43
     2.8   12.43     3.9   13.63     4.5   13.63       5   13.13      15   13.13
#Mann= 3 , 0 , 0
   -13.4    .035       0       0    .035       0     3.9    .035       0
#XS Ineff= 2 , 0
               0      25     3.9              25
Permanent Ineff=
       F       F
#Block Obstruct= 2 , 0
                             3.9
Bank Sta=0,3.9
XS Rating Curve= 0
Exp/Cntr=.3,.1

Type RM Length L Ch R = 1 ,79      ,50,50,50
#Sta/Elev= 10
   -13.3   12.43    -3.3   12.43    -2.5   13.43       0   13.43     1.9   12.13
     2.7   12.13       4   13.43     4.7   13.43       5   13.13      15   13.13
#Mann= 3 , 0 , 0
   -13.3    .035       0       0    .035       0       4    .035       0
#XS Ineff= 2 , 0
               0      20       4              20
Permanent Ineff=
       F       F
#Block Obstruct= 2 , 0
                             4.1
Bank Sta=0,4
XS Rating Curve= 0
Exp/Cntr=.3,.1

Type RM Length L Ch R = 1 ,78      ,50,50,50
#Sta/Elev= 10
   -13.3   11.81    -3.3   11.81    -2.3   13.01       0   13.01       2   11.61
     2.6   11.61     4.1   13.11     4.9   13.11     5.1   12.91    15.1   12.91
#Mann= 3 , 0 , 0
   -13.3    .035       0       0    .035       0     4.1    .035       0
#XS Ineff= 2 , 0
               0      20     4.1              20
Permanent Ineff=
       F       F
#Block Obstruct= 2 , 0
                             4.1
Bank Sta=0,4.1
XS Rating Curve= 0
Exp/Cntr=.3,.1

Type RM Length L Ch R = 1 ,77      ,50,50,50
#Sta/Elev= 10
   -13.7   11.65    -3.7   11.65    -2.7   12.75       0   12.75     2.1   11.25
     2.7   11.25     4.2   12.75     4.8   12.75       5   12.55      15   12.55
#Mann= 3 , 0 , 0
   -13.7    .035       0       0    .035       0     4.2    .035       0
#XS Ineff= 2 , 0
               0      20     4.2              20
Permanent Ineff=
       F       F
#Block Obstruct= 2 , 0
                             4.2
Bank Sta=0,4.2
XS Rating Curve= 0
Exp/Cntr=.3,.1

Type RM Length L Ch R = 1 ,76      ,50,50,50
#Sta/Elev= 10
   -13.6   11.14    -3.6   11.14      -3   12.14       0   12.14     2.2   10.54
     2.9   10.54     4.5   12.04     4.8   12.04       5   11.84      15   11.84
#Mann= 3 , 0 , 0
   -13.6    .035       0       0    .035       0     4.5    .035       0
#XS Ineff= 2 , 0
               0      20     4.5              20
Permanent Ineff=
       F       F
#Block Obstruct= 2 , 0
                             4.5
Bank Sta=0,4.5
XS Rating Curve= 0
Exp/Cntr=.3,.1

Type RM Length L Ch R = 1 ,75      ,50,50,50
#Sta/Elev= 10
   -13.6   10.68    -3.6   10.68    -2.5   11.58       0   11.58      .5   10.38
     1.7   10.38     4.2   12.78     4.7   12.78     6.7   10.28    16.7   10.28
#Mann= 3 , 0 , 0
   -13.6    .035       0       0    .035       0     4.2    .035       0
#XS Ineff= 2 , 0
               0      20     4.2              20
Permanent Ineff=
       F       F
#Block Obstruct= 2 , 0
                             4.2
Bank Sta=0,4.2
XS Rating Curve= 0
Exp/Cntr=.3,.1

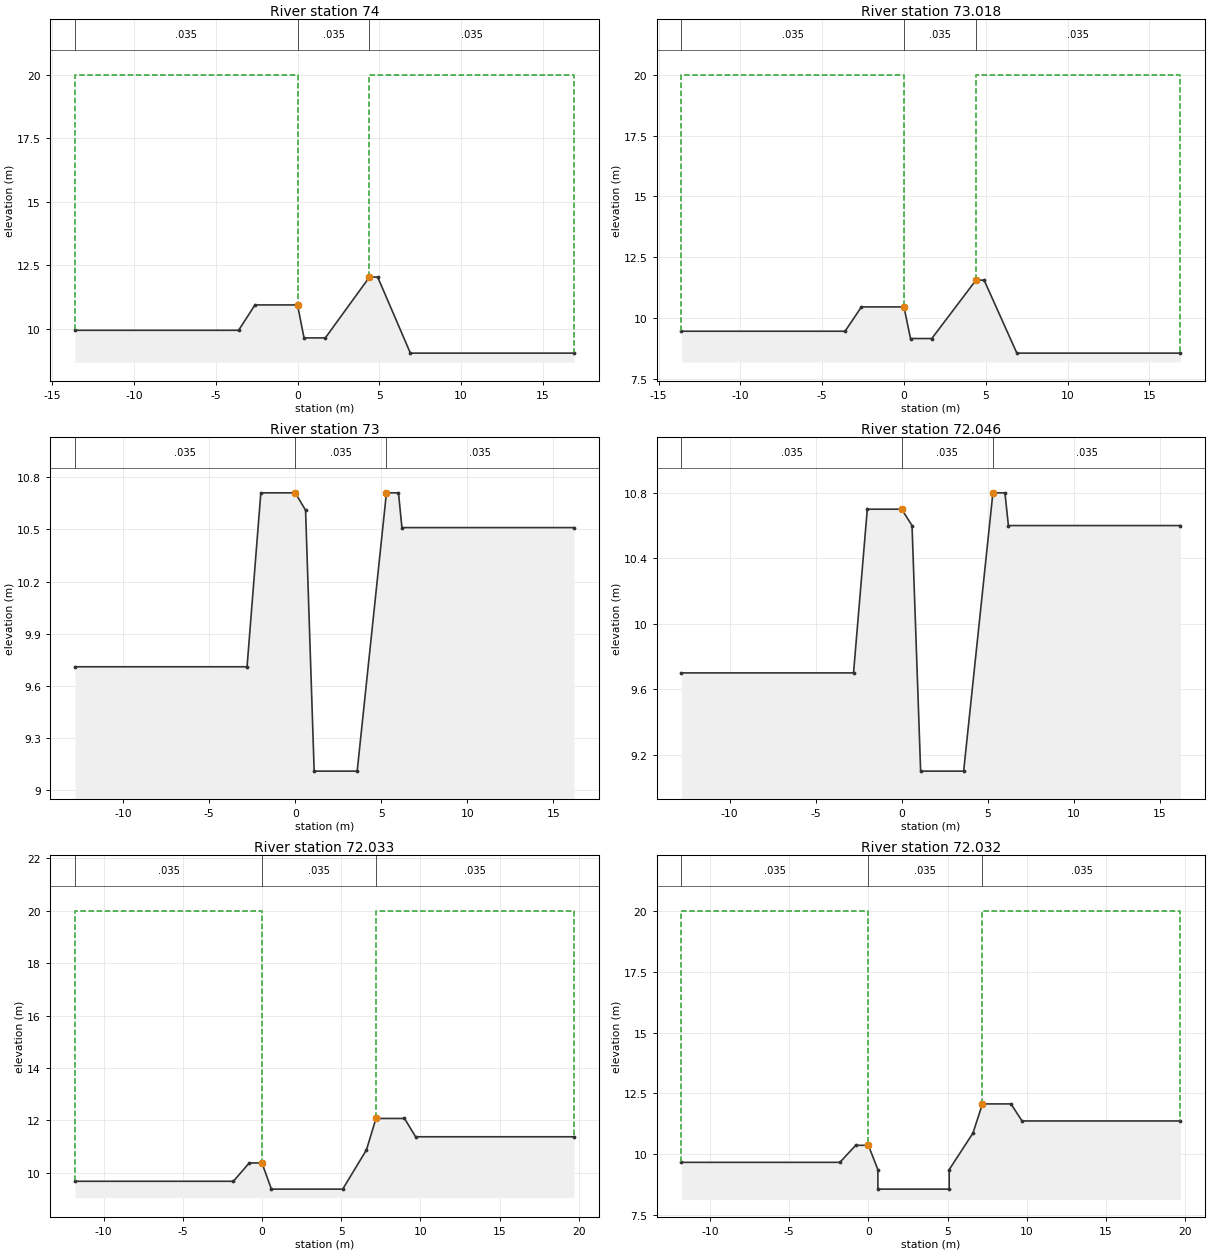
Type RM Length L Ch R = 1 ,74      ,32,32,32
#Sta/Elev= 10
   -13.6    9.93    -3.6    9.93    -2.6   10.93       0   10.93      .4    9.63
     1.7    9.63     4.4   12.03     4.9   12.03     6.9    9.03    16.9    9.03
#Mann= 3 , 0 , 0
   -13.6    .035       0       0    .035       0     4.4    .035       0
#XS Ineff= 2 , 0
               0      20     4.4              20
Permanent Ineff=
       F       F
#Block Obstruct= 2 , 0
                             4.4
Bank Sta=0,4.4
XS Rating Curve= 0
Exp/Cntr=.3,.1

Type RM Length L Ch R = 1 ,73.018  ,18,18,18
#Sta/Elev= 10
   -13.6    9.46    -3.6    9.46    -2.6   10.46       0   10.46      .4    9.16
     1.7    9.16     4.4   11.56     4.9   11.56     6.9    8.56    16.9    8.56
#Mann= 3 , 0 , 0
   -13.6    .035       0       0    .035       0     4.4    .035       0
#XS Ineff= 2 , 0
               0      20     4.4              20
Permanent Ineff=
       F       F
#Block Obstruct= 2 , 0
                             4.4
Bank Sta=0,4.4
XS Rating Curve= 0
Exp/Cntr=.3,.1

Type RM Length L Ch R = 1 ,73      ,4,4,4
#Sta/Elev= 11
   -12.8    9.71    -2.8    9.71      -2   10.71       0   10.71      .6   10.61
     1.1    9.11     3.6    9.11     5.3   10.71       6   10.71     6.2   10.51
    16.2   10.51
#Mann= 3 , 0 , 0
   -12.8    .035       0       0    .035       0     5.3    .035       0
#XS Ineff= 2 , 0
               0      20     5.3              20
Permanent Ineff=
       F       F
#Block Obstruct= 2 , 0
                             5.3
Bank Sta=0,5.3
XS Rating Curve= 0
Exp/Cntr=.3,.1

Type RM Length L Ch R = 1 ,72.046  ,13,13,13
#Sta/Elev= 11
   -12.8     9.7    -2.8     9.7      -2    10.7       0    10.7      .6    10.6
     1.1     9.1     3.6     9.1     5.3    10.8       6    10.8     6.2    10.6
    16.2    10.6
#Mann= 3 , 0 , 0
   -12.8    .035       0       0    .035       0     5.3    .035       0
#XS Ineff= 2 , 0
               0      20     5.3              20
Permanent Ineff=
       F       F
#Block Obstruct= 2 , 0
                             5.3
Bank Sta=0,5.3
XS Rating Curve= 0
Exp/Cntr=.3,.1

Type RM Length L Ch R = 1 ,72.033  ,1,1,1
#Sta/Elev= 11
   -11.8    9.67    -1.8    9.67     -.8   10.37       0   10.37      .6    9.37
     5.1    9.37     6.6   10.87     7.2   12.07       9   12.07     9.7   11.37
    19.7   11.37
#Mann= 3 , 0 , 0
   -11.8    .035       0       0    .035       0     7.2    .035       0
#XS Ineff= 2 , 0
               0      20     7.2              20
Permanent Ineff=
       F       F
#Block Obstruct= 2 , 0
                             7.2
Bank Sta=0,7.2
XS Rating Curve= 0
Exp/Cntr=.3,.1

Type RM Length L Ch R = 1 ,72.032  ,32,32,32
#Sta/Elev= 13
   -11.8    9.67    -1.8    9.67     -.8   10.37       0   10.37      .6    9.37
      .6    8.57     5.1    8.57     5.1    9.37     6.6   10.87     7.2   12.07
       9   12.07     9.7   11.37    19.7   11.37
#Mann= 3 , 0 , 0
   -11.8    .035       0       0    .035       0     7.2    .035       0
#XS Ineff= 2 , 0
               0      20     7.2              20
Permanent Ineff=
       F       F
#Block Obstruct= 2 , 0
                             7.2
Bank Sta=0,7.2
XS Rating Curve= 0
Exp/Cntr=.3,.1

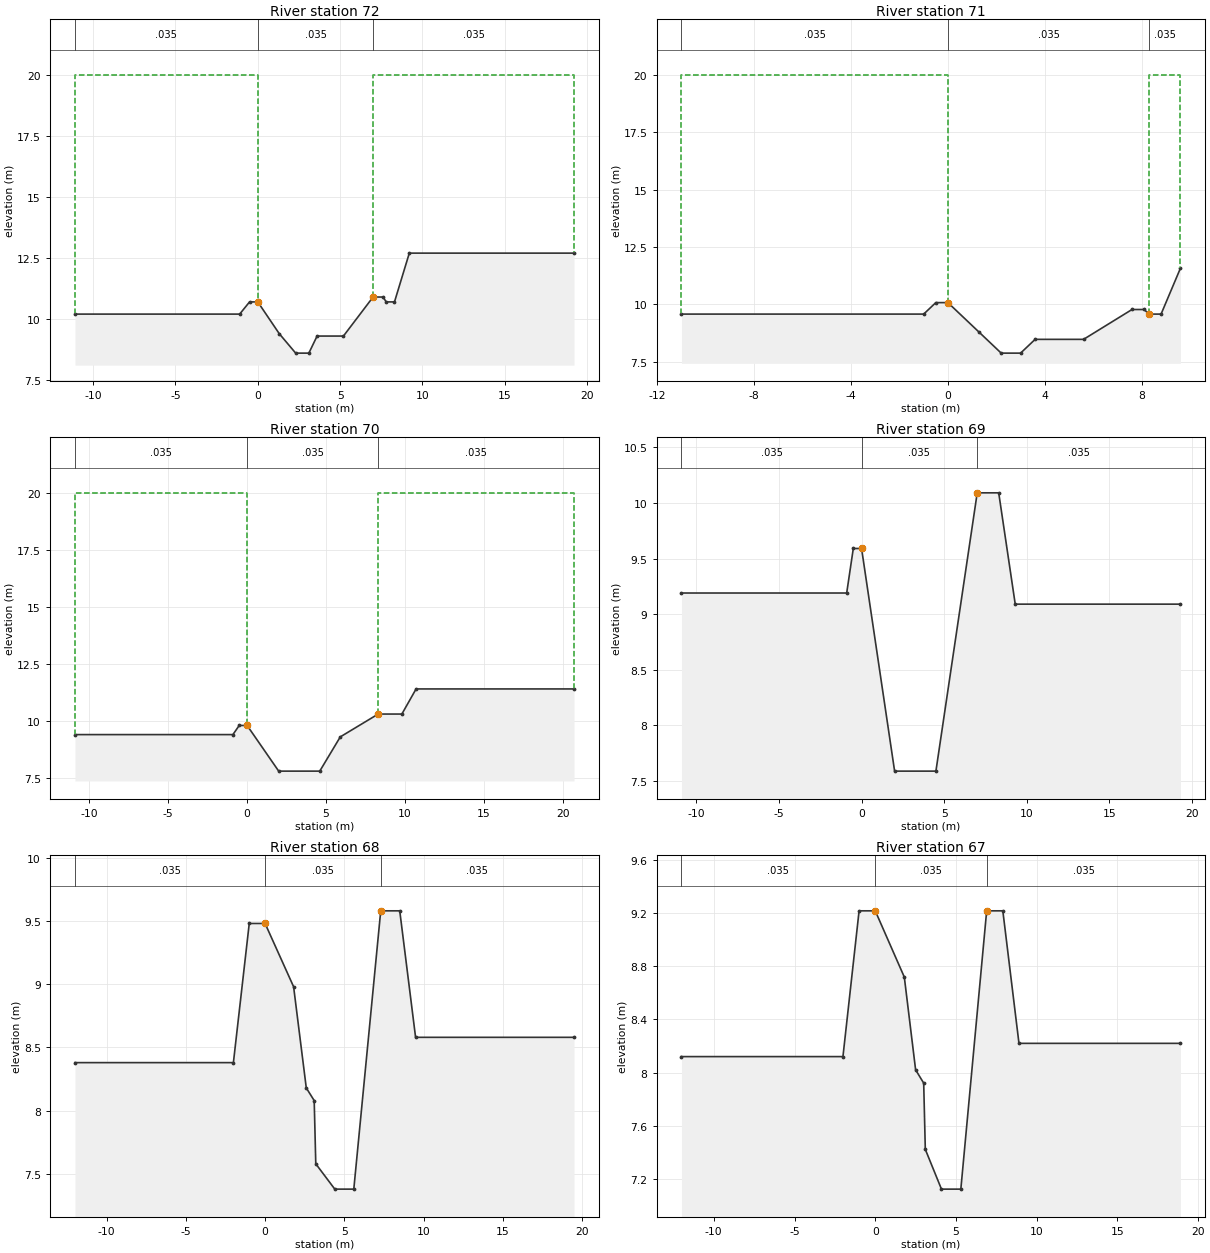
Type RM Length L Ch R = 1 ,72      ,50,50,50
#Sta/Elev= 15
   -11.1   10.19    -1.1   10.19     -.5   10.69       0   10.69     1.3    9.39
     2.3    8.59     3.1    8.59     3.6    9.29     5.2    9.29       7   10.89
     7.6   10.89     7.8   10.69     8.3   10.69     9.2   12.69    19.2   12.69
#Mann= 3 , 0 , 0
   -11.1    .035       0       0    .035       0       7    .035       0
#XS Ineff= 2 , 0
               0      20       7              20
Permanent Ineff=
       F       F
#Block Obstruct= 2 , 0
                               7
Bank Sta=0,7
XS Rating Curve= 0
Exp/Cntr=.3,.1

Type RM Length L Ch R = 1 ,71      ,50,50,50
#Sta/Elev= 14
     -11    9.58      -1    9.58     -.5   10.08       0   10.08     1.3    8.78
     2.2    7.88       3    7.88     3.6    8.48     5.6    8.48     7.6    9.78
     8.1    9.78     8.3    9.58     8.8    9.58     9.6   11.58
#Mann= 3 , 0 , 0
     -11    .035       0       0    .035       0     8.3    .035       0
#XS Ineff= 2 , 0
               0      20     8.3              20
Permanent Ineff=
       F       F
#Block Obstruct= 2 , 0
                             8.3
Bank Sta=0,8.3
XS Rating Curve= 0
Exp/Cntr=.3,.1

Type RM Length L Ch R = 1 ,70      ,50,50,50
#Sta/Elev= 11
   -10.9    9.41     -.9    9.41     -.5    9.81       0    9.81       2    7.81
     4.6    7.81     5.9    9.31     8.3   10.31     9.8   10.31    10.7   11.41
    20.7   11.41
#Mann= 3 , 0 , 0
   -10.9    .035       0       0    .035       0     8.3    .035       0
#XS Ineff= 2 , 0
               0      20     8.3              20
Permanent Ineff=
       F       F
#Block Obstruct= 2 , 0
                             8.3
Bank Sta=0,8.3
XS Rating Curve= 0
Exp/Cntr=.3,.1

Type RM Length L Ch R = 1 ,69      ,50,50,50
#Sta/Elev= 10
   -10.9    9.19     -.9    9.19     -.5    9.59       0    9.59       2    7.59
     4.5    7.59       7   10.09     8.3   10.09     9.3    9.09    19.3    9.09
#Mann= 3 , 0 , 0
   -10.9    .035       0       0    .035       0       7    .035       0
#XS Ineff= 2 , 0
               0      20       7              20
Permanent Ineff=
       F       F
#Block Obstruct= 2 , 0
                               7
Bank Sta=0,7
XS Rating Curve= 0
Exp/Cntr=.3,.1

Type RM Length L Ch R = 1 ,68      ,50,50,50
#Sta/Elev= 14
     -12    8.38      -2    8.38      -1    9.48       0    9.48     1.8    8.98
     2.6    8.18     3.1    8.08     3.2    7.58     4.4    7.38     5.6    7.38
     7.3    9.58     8.5    9.58     9.5    8.58    19.5    8.58
#Mann= 3 , 0 , 0
     -12    .035       0       0    .035       0     7.3    .035       0
#XS Ineff= 2 , 0
               0      20     7.3              20
Permanent Ineff=
       F       F
#Block Obstruct= 2 , 0
                             7.3
Bank Sta=0,7.3
XS Rating Curve= 0
Exp/Cntr=.3,.1

Type RM Length L Ch R = 1 ,67      ,50,50,50
#Sta/Elev= 14
     -12    8.12      -2    8.12      -1    9.22       0    9.22     1.8    8.72
     2.5    8.02       3    7.92     3.1    7.42     4.1    7.12     5.3    7.12
     6.9    9.22     7.9    9.22     8.9    8.22    18.9    8.22
#Mann= 3 , 0 , 0
     -12    .035       0       0    .035       0     6.9    .035       0
#XS Ineff= 2 , 0
               0      20     6.9              20
Permanent Ineff=
       F       F
#Block Obstruct= 2 , 0
                             6.9
Bank Sta=0,6.9
XS Rating Curve= 0
Exp/Cntr=.3,.1

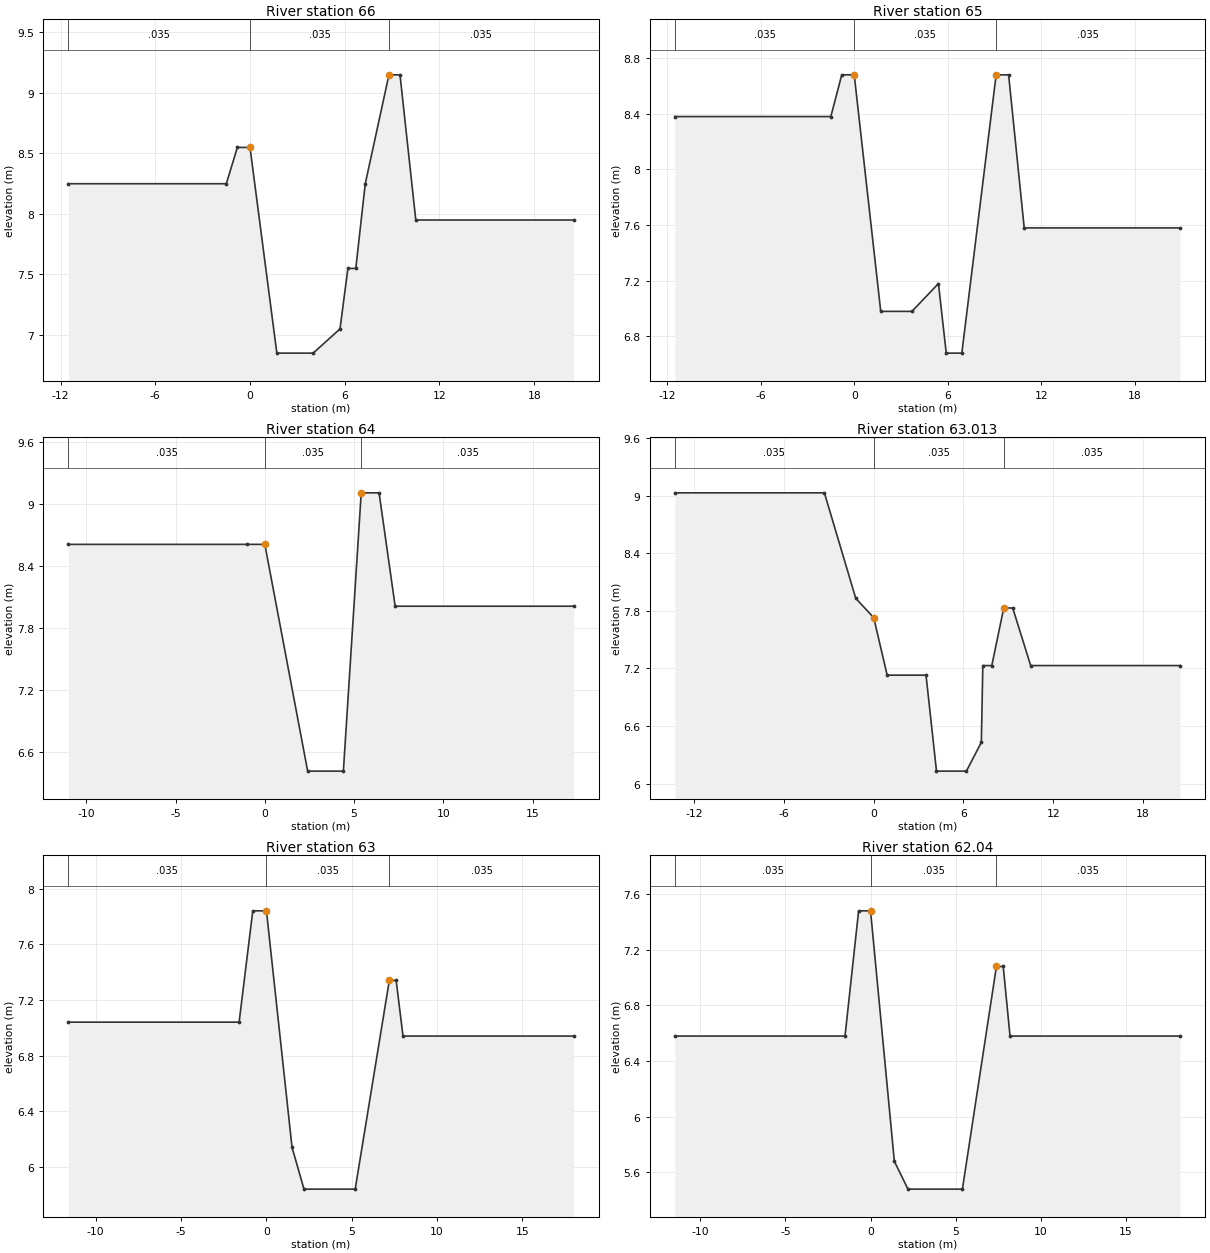
Type RM Length L Ch R = 1 ,66      ,50,50,50
#Sta/Elev= 14
   -11.5    8.25    -1.5    8.25     -.8    8.55       0    8.55     1.7    6.85
       4    6.85     5.7    7.05     6.2    7.55     6.7    7.55     7.3    8.25
     8.8    9.15     9.5    9.15    10.5    7.95    20.5    7.95
#Mann= 3 , 0 , 0
   -11.5    .035       0       0    .035       0     8.8    .035       0
#XS Ineff= 2 , 0
               0      20     8.8              20
Permanent Ineff=
       F       F
#Block Obstruct= 2 , 0
                             8.8
Bank Sta=0,8.8
XS Rating Curve= 0
Exp/Cntr=.3,.1

Type RM Length L Ch R = 1 ,65      ,50,50,50
#Sta/Elev= 13
   -11.5    8.38    -1.5    8.38     -.8    8.68       0    8.68     1.7    6.98
     3.7    6.98     5.4    7.18     5.9    6.68     6.9    6.68     9.1    8.68
     9.9    8.68    10.9    7.58    20.9    7.58
#Mann= 3 , 0 , 0
   -11.5    .035       0       0    .035       0     9.1    .035       0
#XS Ineff= 2 , 0
               0      20     9.1              20
Permanent Ineff=
       F       F
#Block Obstruct= 2 , 0
                             9.1
Bank Sta=0,9.1
XS Rating Curve= 0
Exp/Cntr=.3,.1

Type RM Length L Ch R = 1 ,64      ,37,37,37
#Sta/Elev= 9
     -11    8.61      -1    8.61       0    8.61     2.4    6.41     4.4    6.41
     5.4    9.11     6.4    9.11     7.3    8.01    17.3    8.01
#Mann= 3 , 0 , 0
     -11    .035       0       0    .035       0     5.4    .035       0
#XS Ineff= 2 , 0
               0      20     5.4              20
Permanent Ineff=
       F       F
#Block Obstruct= 2 , 0
                             5.4
Bank Sta=0,5.4
XS Rating Curve= 0
Exp/Cntr=.3,.1

Type RM Length L Ch R = 1 ,63.013  ,13,13,13
#Sta/Elev= 15
   -13.3    9.03    -3.3    9.03    -1.2    7.93       0    7.73      .9    7.13
     3.5    7.13     4.2    6.13     6.2    6.13     7.2    6.43     7.3    7.23
     7.9    7.23     8.7    7.83     9.3    7.83    10.5    7.23    20.5    7.23
#Mann= 3 , 0 , 0
   -13.3    .035       0       0    .035       0     8.7    .035       0
#XS Ineff= 2 , 0
               0      20     8.7              20
Permanent Ineff=
       F       F
#Block Obstruct= 2 , 0
                             8.7
Bank Sta=0,8.7
XS Rating Curve= 0
Exp/Cntr=.3,.1

Type RM Length L Ch R = 1 ,63      ,10,10,10
#Sta/Elev= 11
   -11.6    7.04    -1.6    7.04     -.8    7.84       0    7.84     1.5    6.14
     2.2    5.84     5.2    5.84     7.2    7.34     7.6    7.34       8    6.94
      18    6.94
#Mann= 3 , 0 , 0
   -11.6    .035       0       0    .035       0     7.2    .035       0
#XS Ineff= 2 , 0
               0      20     7.2              20
Permanent Ineff=
       F       F
#Block Obstruct= 2 , 0
                             7.2
Bank Sta=0,7.2
XS Rating Curve= 0
Exp/Cntr=.3,.1

Type RM Length L Ch R = 1 ,62.04   ,15,15,15
#Sta/Elev= 11
   -11.5    6.58    -1.5    6.58     -.7    7.48       0    7.48     1.4    5.68
     2.2    5.48     5.4    5.48     7.4    7.08     7.8    7.08     8.2    6.58
    18.2    6.58
#Mann= 3 , 0 , 0
   -11.5    .035       0       0    .035       0     7.4    .035       0
#XS Ineff= 2 , 0
               0      20     7.4              20
Permanent Ineff=
       F       F
#Block Obstruct= 2 , 0
                             7.4
Bank Sta=0,7.4
XS Rating Curve= 0
Exp/Cntr=.3,.1