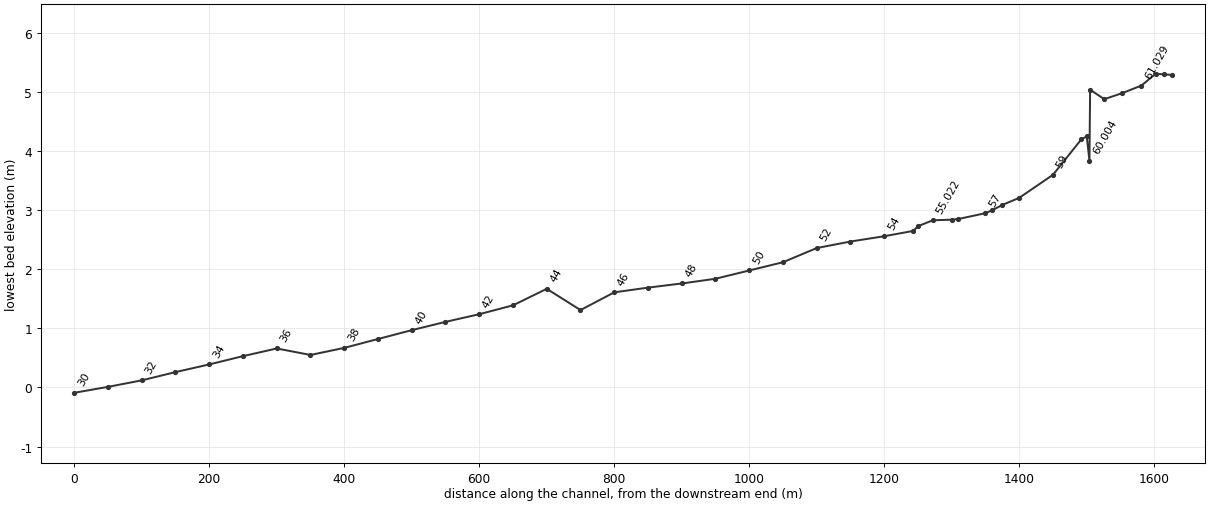
HEC-RAS study dsc.prj: dongsan

--- dsc.g01 (geometry) --- (continued)

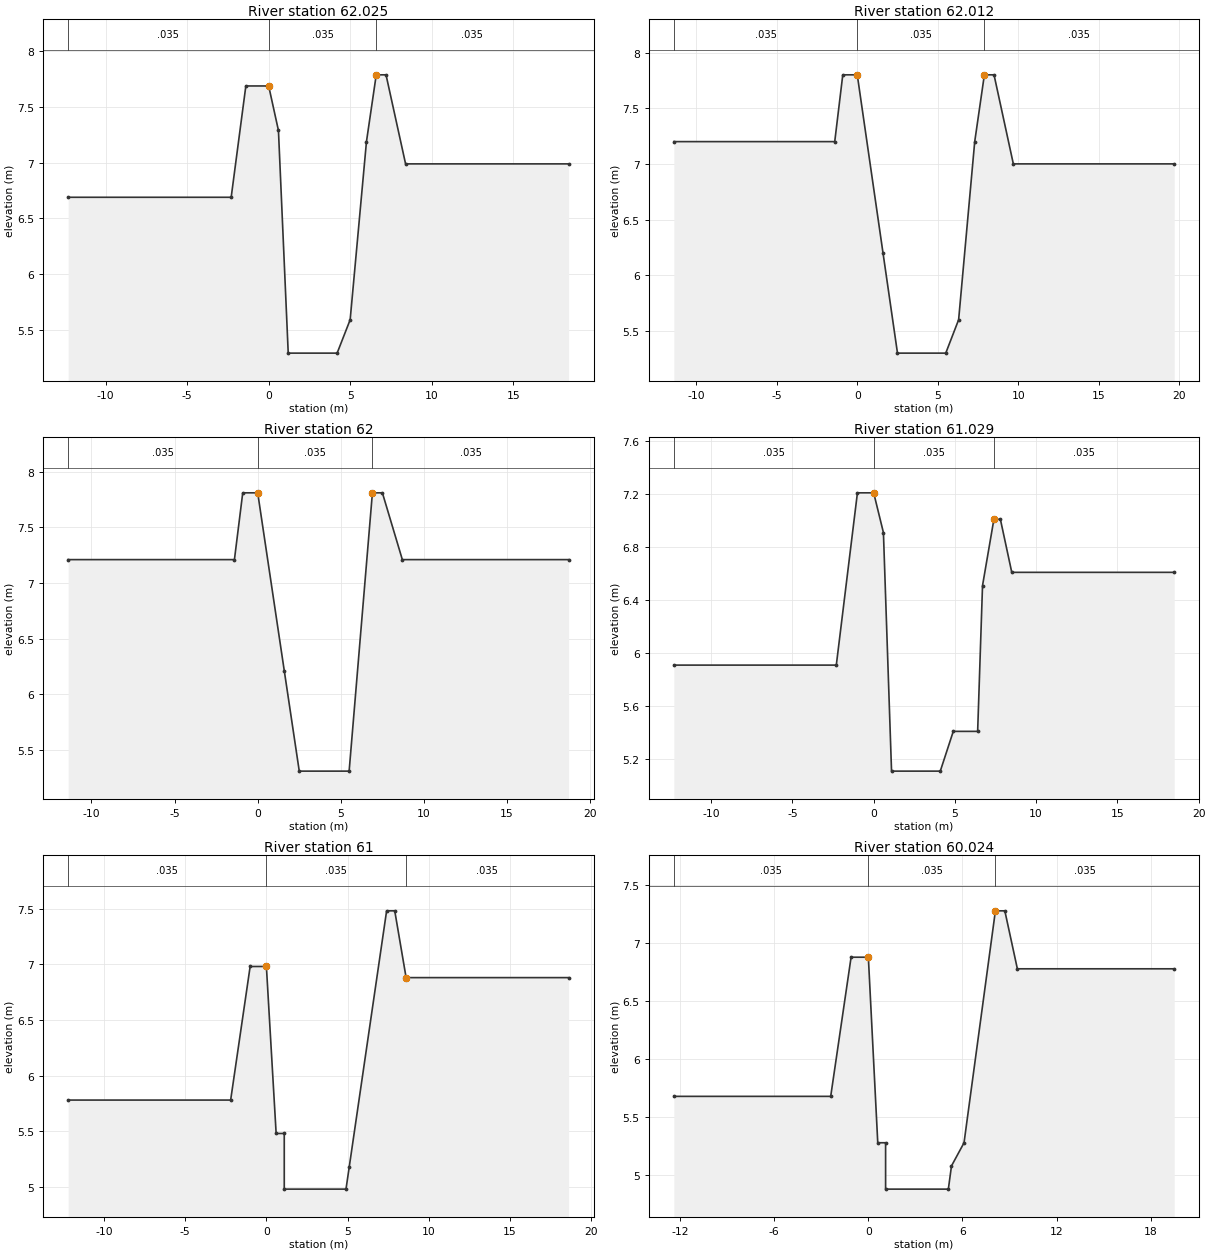
Type RM Length L Ch R = 1 ,62.025  ,13,13,13
#Sta/Elev= 13
   -12.3    6.69    -2.3    6.69    -1.4    7.69       0    7.69      .6    7.29
     1.2    5.29     4.2    5.29       5    5.59       6    7.19     6.6    7.79
     7.2    7.79     8.4    6.99    18.4    6.99
#Mann= 3 , 0 , 0
   -12.3    .035       0       0    .035       0     6.6    .035       0
#XS Ineff= 2 , 0
               0      20     6.6              20
Permanent Ineff=
       F       F
#Block Obstruct= 2 , 0
                             6.6
Bank Sta=0,6.6
XS Rating Curve= 0
Exp/Cntr=.3,.1

Type RM Length L Ch R = 1 ,62.012  ,12,12,12
#Sta/Elev= 13
   -11.4     7.2    -1.4     7.2     -.9     7.8       0     7.8     1.6     6.2
     2.5     5.3     5.5     5.3     6.3     5.6     7.3     7.2     7.9     7.8
     8.5     7.8     9.7       7    19.7       7
#Mann= 3 , 0 , 0
   -11.4    .035       0       0    .035       0     7.9    .035       0
#XS Ineff= 2 , 0
               0      20     7.9              20
Permanent Ineff=
       F       F
#Block Obstruct= 2 , 0
                             7.9
Bank Sta=0,7.9
XS Rating Curve= 0
Exp/Cntr=.3,.1

Type RM Length L Ch R = 1 ,62      ,21,21,21
#Sta/Elev= 11
   -11.4    7.21    -1.4    7.21     -.9    7.81       0    7.81     1.6    6.21
     2.5    5.31     5.5    5.31     6.9    7.81     7.5    7.81     8.7    7.21
    18.7    7.21
#Mann= 3 , 0 , 0
   -11.4    .035       0       0    .035       0     6.9    .035       0
#XS Ineff= 2 , 0
               0      20     6.9              20
Permanent Ineff=
       F       F
#Block Obstruct= 2 , 0
                             6.9
Bank Sta=0,6.9
XS Rating Curve= 0
Exp/Cntr=.3,.1

Type RM Length L Ch R = 1 ,61.029  ,29,29,29
#Sta/Elev= 14
   -12.3    5.91    -2.3    5.91      -1    7.21       0    7.21      .6    6.91
     1.1    5.11     4.1    5.11     4.9    5.41     6.4    5.41     6.7    6.51
     7.4    7.01     7.8    7.01     8.5    6.61    18.5    6.61
#Mann= 3 , 0 , 0
   -12.3    .035       0       0    .035       0     7.4    .035       0
#XS Ineff= 2 , 0
               0      20     7.4              20
Permanent Ineff=
       F       F
#Block Obstruct= 2 , 0
                             7.4
Bank Sta=0,7.4
XS Rating Curve= 0
Exp/Cntr=.3,.1

Type RM Length L Ch R = 1 ,61      ,26,26,26
#Sta/Elev= 13
   -12.2    5.78    -2.2    5.78      -1    6.98       0    6.98      .6    5.48
     1.1    5.48     1.1    4.98     4.9    4.98     5.1    5.18     7.4    7.48
     7.9    7.48     8.6    6.88    18.6    6.88
#Mann= 3 , 0 , 0
   -12.2    .035       0       0    .035       0     8.6    .035       0
#XS Ineff= 2 , 0
               0      20     8.6              20
Permanent Ineff=
       F       F
#Block Obstruct= 2 , 0
                             8.6
Bank Sta=0,8.6
XS Rating Curve= 0
Exp/Cntr=.3,.1

Type RM Length L Ch R = 1 ,60.024  ,21,21,21
#Sta/Elev= 14
   -12.4    5.68    -2.4    5.68    -1.1    6.88       0    6.88      .6    5.28
     1.1    5.28     1.1    4.88     5.1    4.88     5.3    5.08     6.1    5.28
     8.1    7.28     8.7    7.28     9.5    6.78    19.5    6.78
#Mann= 3 , 0 , 0
   -12.4    .035       0       0    .035       0     8.1    .035       0
#XS Ineff= 2 , 0
               0      20     8.1              20
Permanent Ineff=
       F       F
#Block Obstruct= 2 , 0
                             8.1
Bank Sta=0,8.1
XS Rating Curve= 0
Exp/Cntr=.3,.1

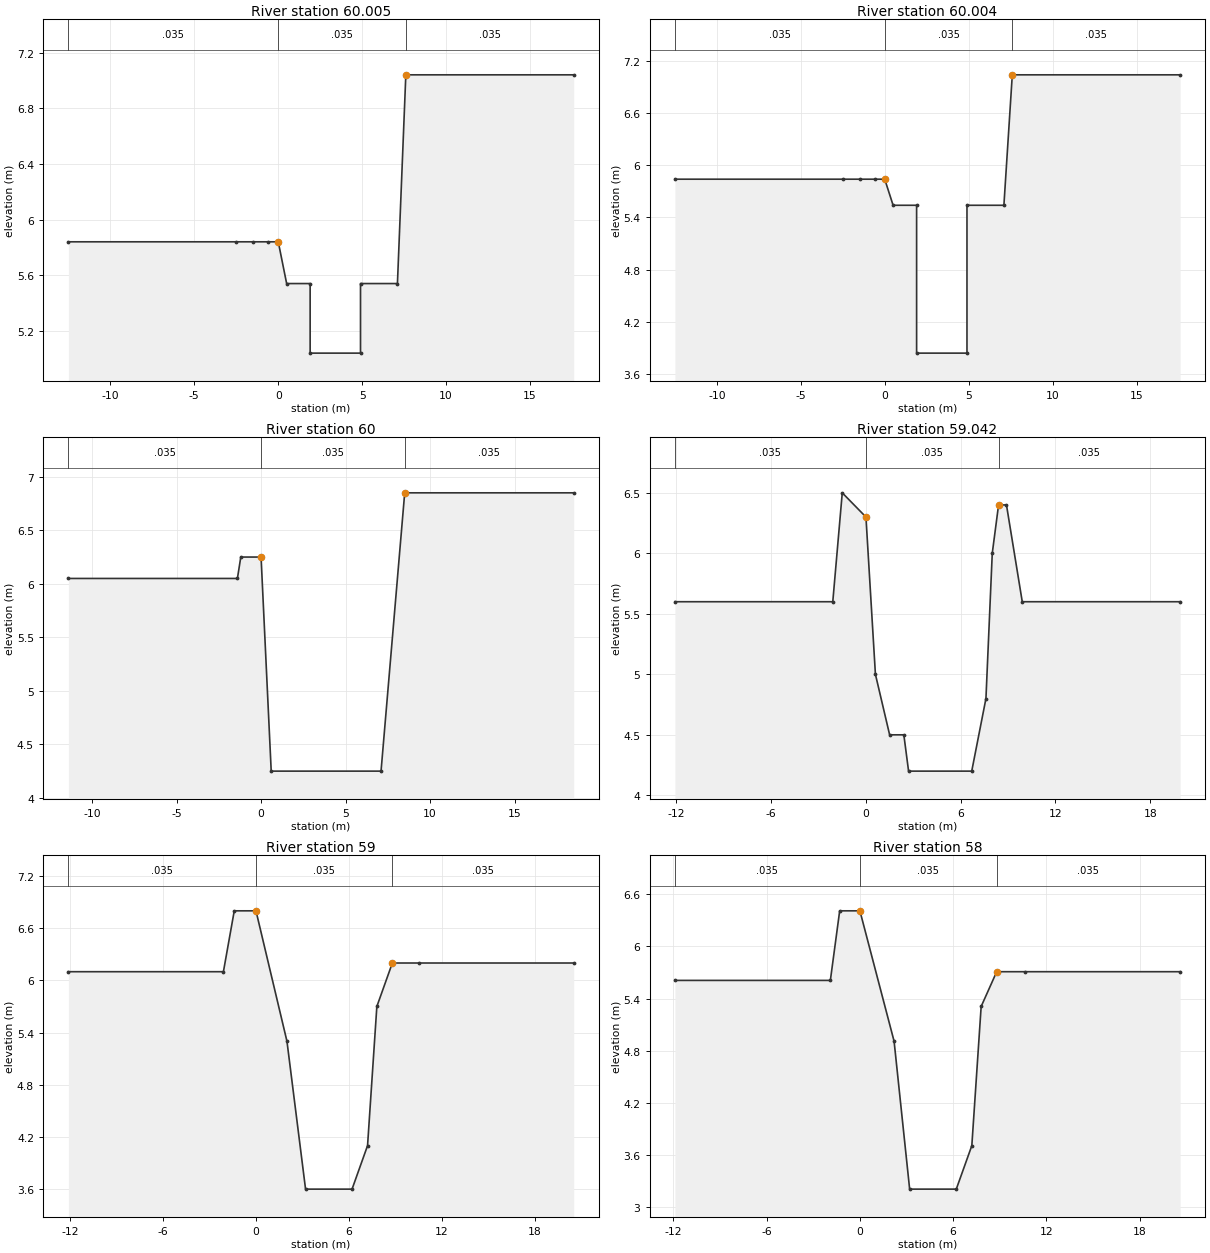
Type RM Length L Ch R = 1 ,60.005  ,1,1,1
#Sta/Elev= 13
   -12.5    5.84    -2.5    5.84    -1.5    5.84     -.6    5.84       0    5.84
      .5    5.54     1.9    5.54     1.9    5.04     4.9    5.04     4.9    5.54
     7.1    5.54     7.6    7.04    17.6    7.04
#Mann= 3 , 0 , 0
   -12.5    .035       0       0    .035       0     7.6    .035       0
#XS Ineff= 2 , 0
               0      20     7.6              20
Permanent Ineff=
       F       F
#Block Obstruct= 2 , 0
                             7.6
Bank Sta=0,7.6
XS Rating Curve= 0
Exp/Cntr=.3,.1

Type RM Length L Ch R = 1 ,60.004  ,4,4,4
#Sta/Elev= 13
   -12.5    5.84    -2.5    5.84    -1.5    5.84     -.6    5.84       0    5.84
      .5    5.54     1.9    5.54     1.9    3.84     4.9    3.84     4.9    5.54
     7.1    5.54     7.6    7.04    17.6    7.04
#Mann= 3 , 0 , 0
   -12.5    .035       0       0    .035       0     7.6    .035       0
#XS Ineff= 2 , 0
               0      20     7.6              20
Permanent Ineff=
       F       F
#Block Obstruct= 2 , 0
                             7.6
Bank Sta=0,7.6
XS Rating Curve= 0
Exp/Cntr=.3,.1

Type RM Length L Ch R = 1 ,60      ,8,8,8
#Sta/Elev= 8
   -11.4    6.05    -1.4    6.05    -1.2    6.25       0    6.25      .6    4.25
     7.1    4.25     8.5    6.85    18.5    6.85
#Mann= 3 , 0 , 0
   -11.4    .035       0       0    .035       0     8.5    .035       0
#XS Ineff= 2 , 0
               0      20     8.5              20
Permanent Ineff=
       F       F
#Block Obstruct= 2 , 0
                             8.5
Bank Sta=0,8.5
XS Rating Curve= 0
Exp/Cntr=.3,.1

Type RM Length L Ch R = 1 ,59.042  ,42,42,42
#Sta/Elev= 15
   -12.1     5.6    -2.1     5.6    -1.5     6.5       0     6.3      .6       5
     1.5     4.5     2.4     4.5     2.7     4.2     6.7     4.2     7.6     4.8
       8       6     8.4     6.4     8.9     6.4     9.9     5.6    19.9     5.6
#Mann= 3 , 0 , 0
   -12.1    .035       0       0    .035       0     8.4    .035       0
#XS Ineff= 2 , 0
               0      20     8.4              20
Permanent Ineff=
       F       F
#Block Obstruct= 2 , 0
                             8.4
Bank Sta=0,8.4
XS Rating Curve= 0
Exp/Cntr=.3,.1

Type RM Length L Ch R = 1 ,59      ,50,50,50
#Sta/Elev= 12
   -12.1     6.1    -2.1     6.1    -1.4     6.8       0     6.8       2     5.3
     3.2     3.6     6.2     3.6     7.2     4.1     7.8     5.7     8.8     6.2
    10.5     6.2    20.5     6.2
#Mann= 3 , 0 , 0
   -12.1    .035       0       0    .035       0     8.8    .035       0
#XS Ineff= 2 , 0
               0      20     8.8              20
Permanent Ineff=
       F       F
#Block Obstruct= 2 , 0
                             8.8
Bank Sta=0,8.8
XS Rating Curve= 0
Exp/Cntr=.3,.1

Type RM Length L Ch R = 1 ,58      ,25,25,25
#Sta/Elev= 12
   -11.9    5.61    -1.9    5.61    -1.3    6.41       0    6.41     2.2    4.91
     3.2    3.21     6.2    3.21     7.2    3.71     7.8    5.31     8.8    5.71
    10.6    5.71    20.6    5.71
#Mann= 3 , 0 , 0
   -11.9    .035       0       0    .035       0     8.8    .035       0
#XS Ineff= 2 , 0
               0      20     8.8              20
Permanent Ineff=
       F       F
#Block Obstruct= 2 , 0
                             8.8
Bank Sta=0,8.8
XS Rating Curve= 0
Exp/Cntr=.3,.1

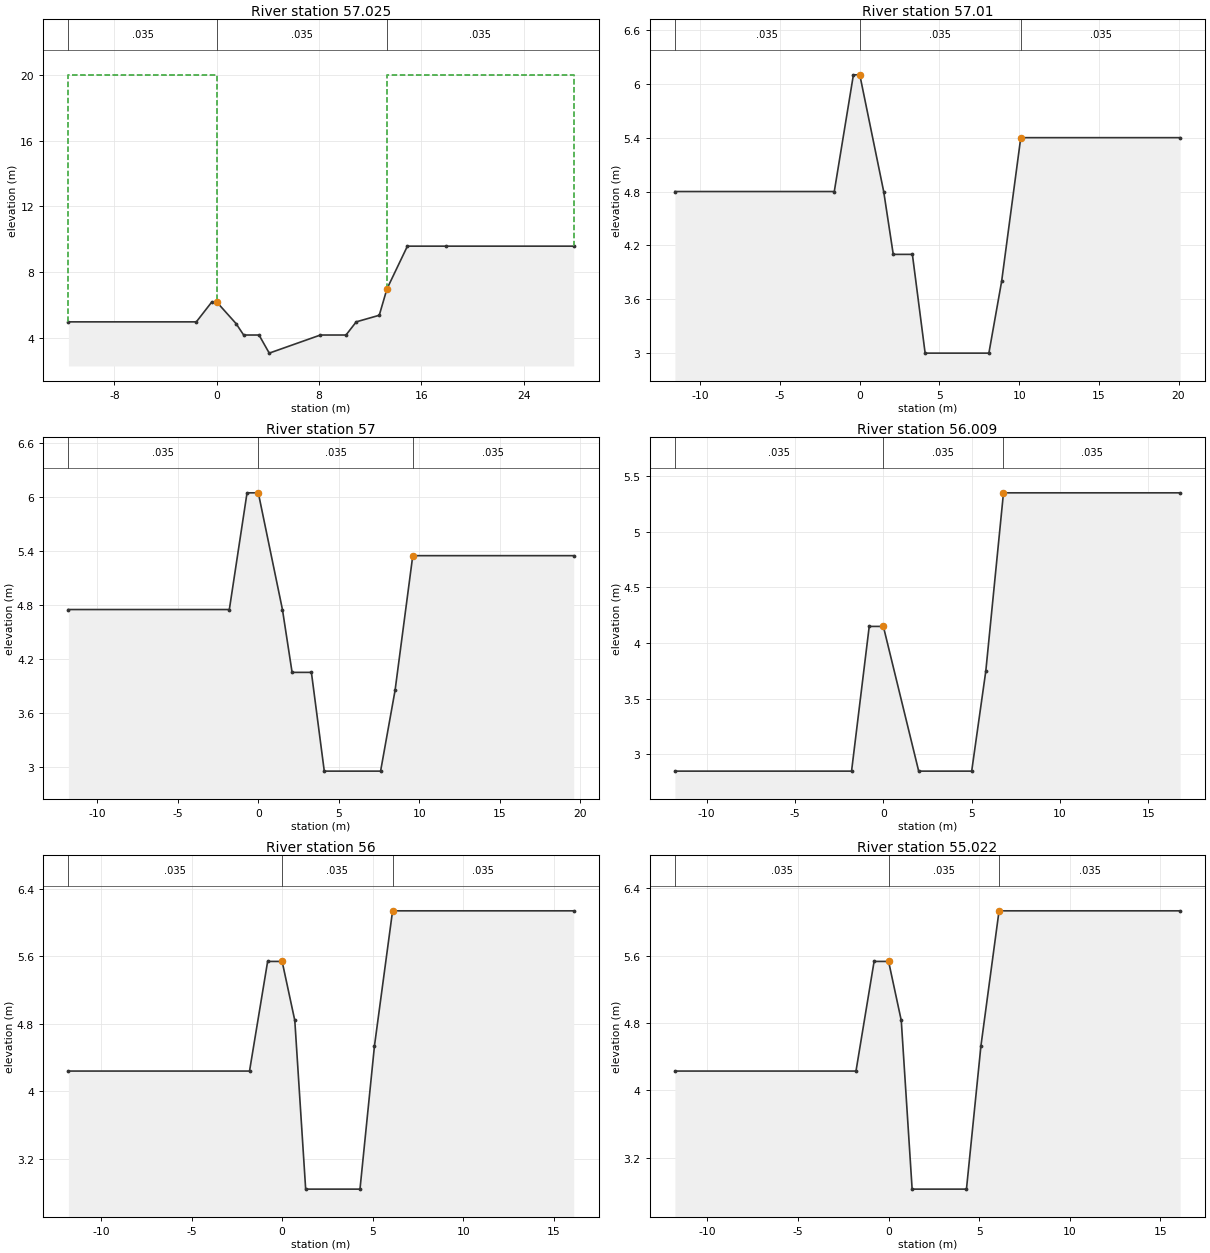
Type RM Length L Ch R = 1 ,57.025  ,15,15,15
#Sta/Elev= 16
   -11.6    4.99    -1.6    4.99     -.4    6.19       0    6.19     1.5    4.89
     2.1    4.19     3.3    4.19     4.1    3.09     8.1    4.19    10.1    4.19
    10.9    4.99    12.7    5.39    13.3    6.99    14.9    9.59    17.9    9.59
    27.9    9.59
#Mann= 3 , 0 , 0
   -11.6    .035       0       0    .035       0    13.3    .035       0
#XS Ineff= 2 , 0
               0      20    13.3              20
Permanent Ineff=
       F       F
#Block Obstruct= 2 , 0
                            13.3
Bank Sta=0,13.3
XS Rating Curve= 0
Exp/Cntr=.3,.1

Type RM Length L Ch R = 1 ,57.01   ,10,10,10
#Sta/Elev= 12
   -11.6     4.8    -1.6     4.8     -.4     6.1       0     6.1     1.5     4.8
     2.1     4.1     3.3     4.1     4.1       3     8.1       3     8.9     3.8
    10.1     5.4    20.1     5.4
#Mann= 3 , 0 , 0
   -11.6    .035       0       0    .035       0    10.1    .035       0
#XS Ineff= 2 , 0
               0      20    10.1              20
Permanent Ineff=
       F       F
#Block Obstruct= 2 , 0
                            10.1
Bank Sta=0,10.1
XS Rating Curve= 0
Exp/Cntr=.3,.1

Type RM Length L Ch R = 1 ,57      ,41,41,41
#Sta/Elev= 12
   -11.8    4.75    -1.8    4.75     -.7    6.05       0    6.05     1.5    4.75
     2.1    4.05     3.3    4.05     4.1    2.95     7.6    2.95     8.5    3.85
     9.6    5.35    19.6    5.35
#Mann= 3 , 0 , 0
   -11.8    .035       0       0    .035       0     9.6    .035       0
#XS Ineff= 2 , 0
               0      20     9.6              20
Permanent Ineff=
       F       F
#Block Obstruct= 2 , 0
                             9.6
Bank Sta=0,9.6
XS Rating Curve= 0
Exp/Cntr=.3,.1

Type RM Length L Ch R = 1 ,56.009  ,9,9,9
#Sta/Elev= 9
   -11.8    2.85    -1.8    2.85     -.8    4.15       0    4.15       2    2.85
       5    2.85     5.8    3.75     6.8    5.35    16.8    5.35
#Mann= 3 , 0 , 0
   -11.8    .035       0       0    .035       0     6.8    .035       0
#XS Ineff= 2 , 0
               0      20     6.8              20
Permanent Ineff=
       F       F
#Block Obstruct= 2 , 0
                             6.8
Bank Sta=0,6.8
XS Rating Curve= 0
Exp/Cntr=.3,.1

Type RM Length L Ch R = 1 ,56      ,28,28,28
#Sta/Elev= 10
   -11.8    4.24    -1.8    4.24     -.8    5.54       0    5.54      .7    4.84
     1.3    2.84     4.3    2.84     5.1    4.54     6.1    6.14    16.1    6.14
#Mann= 3 , 0 , 0
   -11.8    .035       0       0    .035       0     6.1    .035       0
#XS Ineff= 2 , 0
               0      20     6.1              20
Permanent Ineff=
       F       F
#Block Obstruct= 2 , 0
                             6.1
Bank Sta=0,6.1
XS Rating Curve= 0
Exp/Cntr=.3,.1

Type RM Length L Ch R = 1 ,55.022  ,22,22,22
#Sta/Elev= 10
   -11.8    4.23    -1.8    4.23     -.8    5.53       0    5.53      .7    4.83
     1.3    2.83     4.3    2.83     5.1    4.53     6.1    6.13    16.1    6.13
#Mann= 3 , 0 , 0
   -11.8    .035       0       0    .035       0     6.1    .035       0
#XS Ineff= 2 , 0
               0      20     6.1              20
Permanent Ineff=
       F       F
#Block Obstruct= 2 , 0
                             6.1
Bank Sta=0,6.1
XS Rating Curve= 0
Exp/Cntr=.3,.1

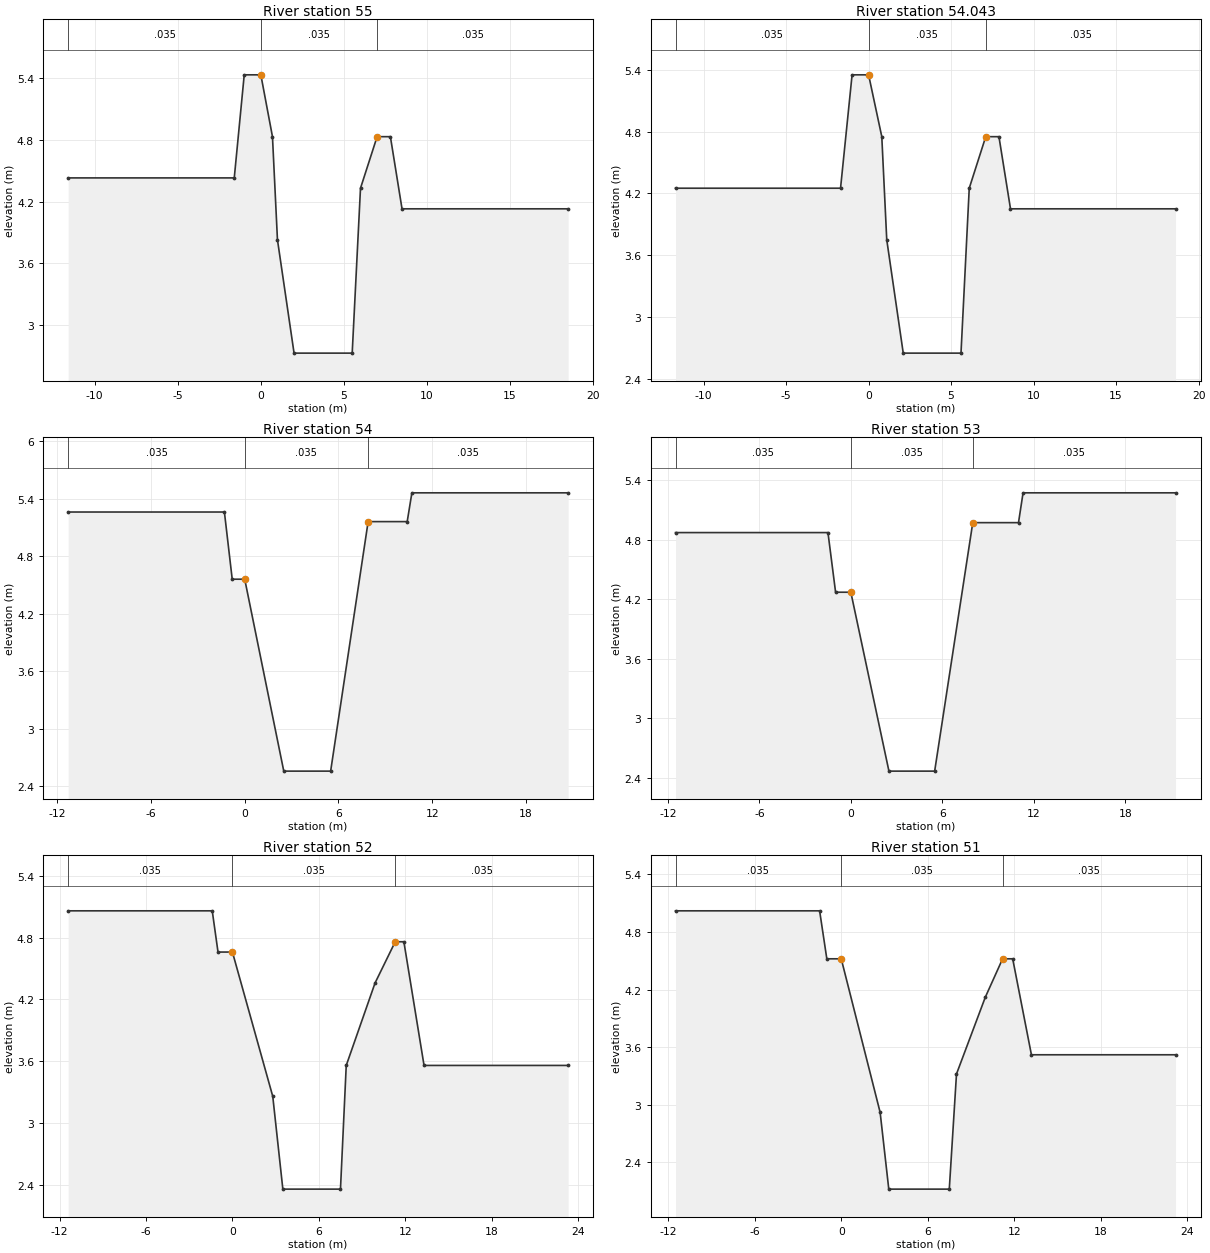
Type RM Length L Ch R = 1 ,55      ,7,7,7
#Sta/Elev= 13
   -11.6    4.43    -1.6    4.43      -1    5.43       0    5.43      .7    4.83
       1    3.83       2    2.73     5.5    2.73       6    4.33       7    4.83
     7.8    4.83     8.5    4.13    18.5    4.13
#Mann= 3 , 0 , 0
   -11.6    .035       0       0    .035       0       7    .035       0
#XS Ineff= 2 , 0
               0      20       7              20
Permanent Ineff=
       F       F
#Block Obstruct= 2 , 0
                               7
Bank Sta=0,7
XS Rating Curve= 0
Exp/Cntr=.3,.1

Type RM Length L Ch R = 1 ,54.043  ,43,43,43
#Sta/Elev= 13
   -11.7    4.25    -1.7    4.25      -1    5.35       0    5.35      .8    4.75
     1.1    3.75     2.1    2.65     5.6    2.65     6.1    4.25     7.1    4.75
     7.9    4.75     8.6    4.05    18.6    4.05
#Mann= 3 , 0 , 0
   -11.7    .035       0       0    .035       0     7.1    .035       0
#XS Ineff= 2 , 0
               0      20     7.1              20
Permanent Ineff=
       F       F
#Block Obstruct= 2 , 0
                             7.1
Bank Sta=0,7.1
XS Rating Curve= 0
Exp/Cntr=.3,.1

Type RM Length L Ch R = 1 ,54      ,50,50,50
#Sta/Elev= 10
   -11.3    5.26    -1.3    5.26     -.8    4.56       0    4.56     2.5    2.56
     5.5    2.56     7.9    5.16    10.4    5.16    10.7    5.46    20.7    5.46
#Mann= 3 , 0 , 0
   -11.3    .035       0       0    .035       0     7.9    .035       0
#XS Ineff= 2 , 0
               0      20     7.9              20
Permanent Ineff=
       F       F
#Block Obstruct= 2 , 0
                             7.9
Bank Sta=0,7.9
XS Rating Curve= 0
Exp/Cntr=.3,.1

Type RM Length L Ch R = 1 ,53      ,50,50,50
#Sta/Elev= 10
   -11.5    4.87    -1.5    4.87      -1    4.27       0    4.27     2.5    2.47
     5.5    2.47       8    4.97      11    4.97    11.3    5.27    21.3    5.27
#Mann= 3 , 0 , 0
   -11.5    .035       0       0    .035       0       8    .035       0
#XS Ineff= 2 , 0
               0      20       8              20
Permanent Ineff=
       F       F
#Block Obstruct= 2 , 0
                               8
Bank Sta=0,8
XS Rating Curve= 0
Exp/Cntr=.3,.1

Type RM Length L Ch R = 1 ,52      ,50,50,50
#Sta/Elev= 13
   -11.4    5.06    -1.4    5.06      -1    4.66       0    4.66     2.8    3.26
     3.5    2.36     7.5    2.36     7.9    3.56     9.9    4.36    11.3    4.76
    11.9    4.76    13.3    3.56    23.3    3.56
#Mann= 3 , 0 , 0
   -11.4    .035       0       0    .035       0    11.3    .035       0
#XS Ineff= 2 , 0
               0      20    11.3              20
Permanent Ineff=
       F       F
#Block Obstruct= 2 , 0
                            11.3
Bank Sta=0,11.3
XS Rating Curve= 0
Exp/Cntr=.3,.1

Type RM Length L Ch R = 1 ,51      ,50,50,50
#Sta/Elev= 13
   -11.5    5.02    -1.5    5.02      -1    4.52       0    4.52     2.7    2.92
     3.3    2.12     7.5    2.12       8    3.32      10    4.12    11.2    4.52
    11.9    4.52    13.2    3.52    23.2    3.52
#Mann= 3 , 0 , 0
   -11.5    .035       0       0    .035       0    11.2    .035       0
#XS Ineff= 2 , 0
               0      20    11.2              20
Permanent Ineff=
       F       F
#Block Obstruct= 2 , 0
                            11.2
Bank Sta=0,11.2
XS Rating Curve= 0
Exp/Cntr=.3,.1

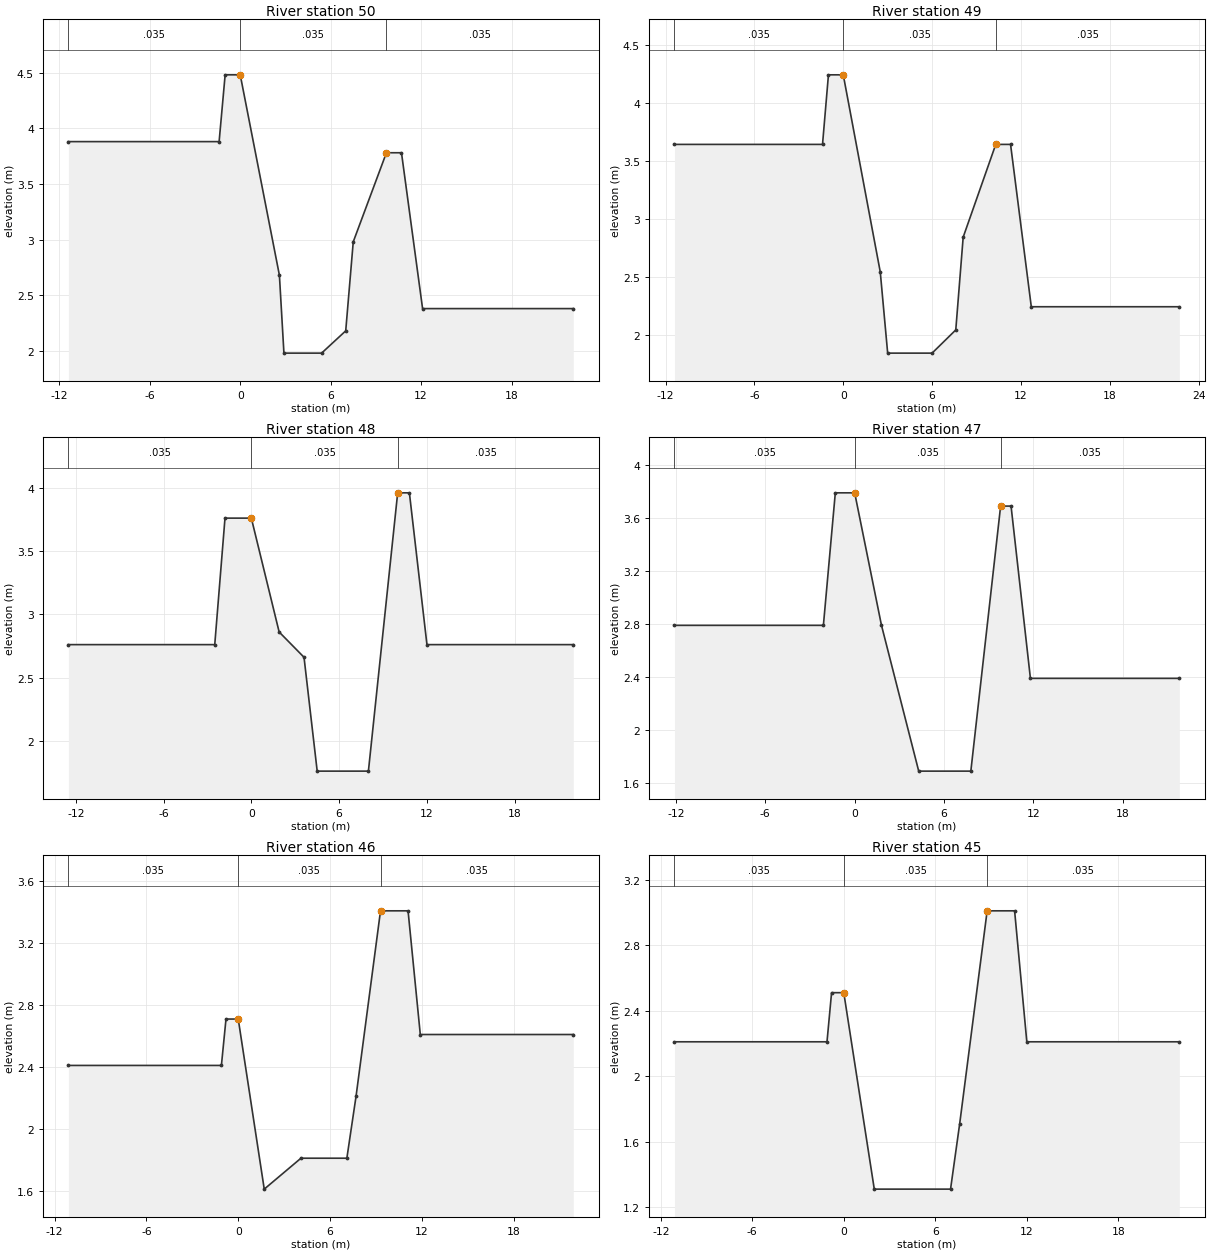
Type RM Length L Ch R = 1 ,50      ,50,50,50
#Sta/Elev= 13
   -11.4    3.88    -1.4    3.88      -1    4.48       0    4.48     2.6    2.68
     2.9    1.98     5.4    1.98       7    2.18     7.5    2.98     9.7    3.78
    10.7    3.78    12.1    2.38    22.1    2.38
#Mann= 3 , 0 , 0
   -11.4    .035       0       0    .035       0     9.7    .035       0
#XS Ineff= 2 , 0
               0      20     9.7              20
Permanent Ineff=
       F       F
#Block Obstruct= 2 , 0
                             9.7
Bank Sta=0,9.7
XS Rating Curve= 0
Exp/Cntr=.3,.1

Type RM Length L Ch R = 1 ,49      ,50,50,50
#Sta/Elev= 13
   -11.4    3.64    -1.4    3.64      -1    4.24       0    4.24     2.5    2.54
       3    1.84       6    1.84     7.6    2.04     8.1    2.84    10.3    3.64
    11.3    3.64    12.7    2.24    22.7    2.24
#Mann= 3 , 0 , 0
   -11.4    .035       0       0    .035       0    10.3    .035       0
#XS Ineff= 2 , 0
               0      20    10.3              20
Permanent Ineff=
       F       F
#Block Obstruct= 2 , 0
                            10.3
Bank Sta=0,10.3
XS Rating Curve= 0
Exp/Cntr=.3,.1

Type RM Length L Ch R = 1 ,48      ,50,50,50
#Sta/Elev= 12
   -12.5    2.76    -2.5    2.76    -1.8    3.76       0    3.76     1.9    2.86
     3.6    2.66     4.5    1.76       8    1.76      10    3.96    10.8    3.96
      12    2.76      22    2.76
#Mann= 3 , 0 , 0
   -12.5    .035       0       0    .035       0      10    .035       0
#XS Ineff= 2 , 0
               0      20      10              20
Permanent Ineff=
       F       F
#Block Obstruct= 2 , 0
                              10
Bank Sta=0,10
XS Rating Curve= 0
Exp/Cntr=.3,.1

Type RM Length L Ch R = 1 ,47      ,50,50,50
#Sta/Elev= 11
   -12.1    2.79    -2.1    2.79    -1.3    3.79       0    3.79     1.8    2.79
     4.3    1.69     7.8    1.69     9.8    3.69    10.5    3.69    11.8    2.39
    21.8    2.39
#Mann= 3 , 0 , 0
   -12.1    .035       0       0    .035       0     9.8    .035       0
#XS Ineff= 2 , 0
               0      20     9.8              20
Permanent Ineff=
       F       F
#Block Obstruct= 2 , 0
                             9.8
Bank Sta=0,9.8
XS Rating Curve= 0
Exp/Cntr=.3,.1

Type RM Length L Ch R = 1 ,46      ,50,50,50
#Sta/Elev= 12
   -11.1    2.41    -1.1    2.41     -.8    2.71       0    2.71     1.7    1.61
     4.1    1.81     7.1    1.81     7.7    2.21     9.3    3.41    11.1    3.41
    11.9    2.61    21.9    2.61
#Mann= 3 , 0 , 0
   -11.1    .035       0       0    .035       0     9.3    .035       0
#XS Ineff= 2 , 0
               0      20     9.3              20
Permanent Ineff=
       F       F
#Block Obstruct= 2 , 0
                             9.3
Bank Sta=0,9.3
XS Rating Curve= 0
Exp/Cntr=.3,.1

Type RM Length L Ch R = 1 ,45      ,50,50,50
#Sta/Elev= 11
   -11.1    2.21    -1.1    2.21     -.8    2.51       0    2.51       2    1.31
       7    1.31     7.6    1.71     9.4    3.01    11.2    3.01      12    2.21
      22    2.21
#Mann= 3 , 0 , 0
   -11.1    .035       0       0    .035       0     9.4    .035       0
#XS Ineff= 2 , 0
               0      20     9.4              20
Permanent Ineff=
       F       F
#Block Obstruct= 2 , 0
                             9.4
Bank Sta=0,9.4
XS Rating Curve= 0
Exp/Cntr=.3,.1

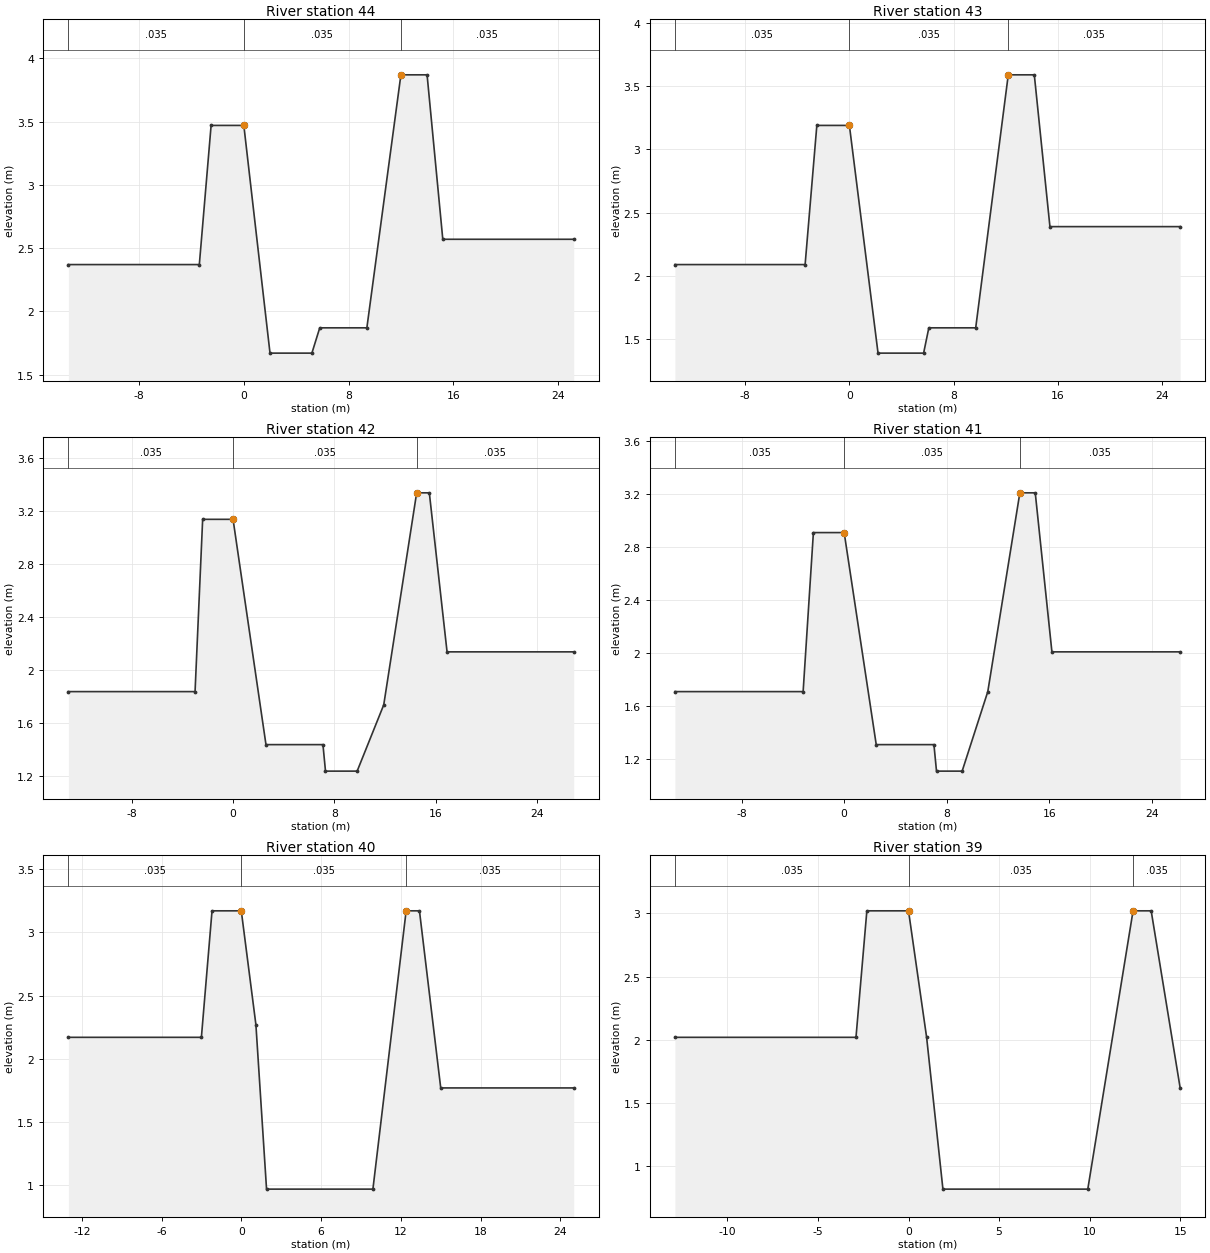
Type RM Length L Ch R = 1 ,44      ,50,50,50
#Sta/Elev= 12
   -13.4    2.37    -3.4    2.37    -2.5    3.47       0    3.47       2    1.67
     5.2    1.67     5.8    1.87     9.4    1.87      12    3.87      14    3.87
    15.2    2.57    25.2    2.57
#Mann= 3 , 0 , 0
   -13.4    .035       0       0    .035       0      12    .035       0
#XS Ineff= 2 , 0
               0      20      12              20
Permanent Ineff=
       F       F
#Block Obstruct= 2 , 0
                              12
Bank Sta=0,12
XS Rating Curve= 0
Exp/Cntr=.3,.1

Type RM Length L Ch R = 1 ,43      ,50,50,50
#Sta/Elev= 12
   -13.4    2.09    -3.4    2.09    -2.5    3.19       0    3.19     2.2    1.39
     5.7    1.39     6.1    1.59     9.7    1.59    12.2    3.59    14.2    3.59
    15.4    2.39    25.4    2.39
#Mann= 3 , 0 , 0
   -13.4    .035       0       0    .035       0    12.2    .035       0
#XS Ineff= 2 , 0
               0      20    12.2              20
Permanent Ineff=
       F       F
#Block Obstruct= 2 , 0
                            12.2
Bank Sta=0,12.2
XS Rating Curve= 0
Exp/Cntr=.3,.1

Type RM Length L Ch R = 1 ,42      ,50,50,50
#Sta/Elev= 13
     -13    1.84      -3    1.84    -2.4    3.14       0    3.14     2.6    1.44
     7.1    1.44     7.3    1.24     9.8    1.24    11.9    1.74    14.5    3.34
    15.5    3.34    16.9    2.14    26.9    2.14
#Mann= 3 , 0 , 0
     -13    .035       0       0    .035       0    14.5    .035       0
#XS Ineff= 2 , 0
               0      20    14.5              20
Permanent Ineff=
       F       F
#Block Obstruct= 2 , 0
                            14.5
Bank Sta=0,14.5
XS Rating Curve= 0
Exp/Cntr=.3,.1

Type RM Length L Ch R = 1 ,41      ,50,50,50
#Sta/Elev= 13
   -13.2    1.71    -3.2    1.71    -2.4    2.91       0    2.91     2.5    1.31
       7    1.31     7.2    1.11     9.2    1.11    11.2    1.71    13.7    3.21
    14.9    3.21    16.2    2.01    26.2    2.01
#Mann= 3 , 0 , 0
   -13.2    .035       0       0    .035       0    13.7    .035       0
#XS Ineff= 2 , 0
               0      20    13.7              20
Permanent Ineff=
       F       F
#Block Obstruct= 2 , 0
                            13.7
Bank Sta=0,13.7
XS Rating Curve= 0
Exp/Cntr=.3,.1

Type RM Length L Ch R = 1 ,40      ,50,50,50
#Sta/Elev= 11
     -13    2.17      -3    2.17    -2.2    3.17       0    3.17     1.1    2.27
     1.9     .97     9.9     .97    12.4    3.17    13.4    3.17      15    1.77
      25    1.77
#Mann= 3 , 0 , 0
     -13    .035       0       0    .035       0    12.4    .035       0
#XS Ineff= 2 , 0
               0      20    12.4              20
Permanent Ineff=
       F       F
#Block Obstruct= 2 , 0
                            12.4
Bank Sta=0,12.4
XS Rating Curve= 0
Exp/Cntr=.3,.1

Type RM Length L Ch R = 1 ,39      ,50,50,50
#Sta/Elev= 10
   -12.9    2.02    -2.9    2.02    -2.3    3.02       0    3.02       1    2.02
     1.9     .82     9.9     .82    12.4    3.02    13.4    3.02      15    1.62
#Mann= 3 , 0 , 0
   -12.9    .035       0       0    .035       0    12.4    .035       0
#XS Ineff= 2 , 0
               0      20    12.4              20
Permanent Ineff=
       F       F
#Block Obstruct= 2 , 0
                            12.4
Bank Sta=0,12.4
XS Rating Curve= 0
Exp/Cntr=.3,.1

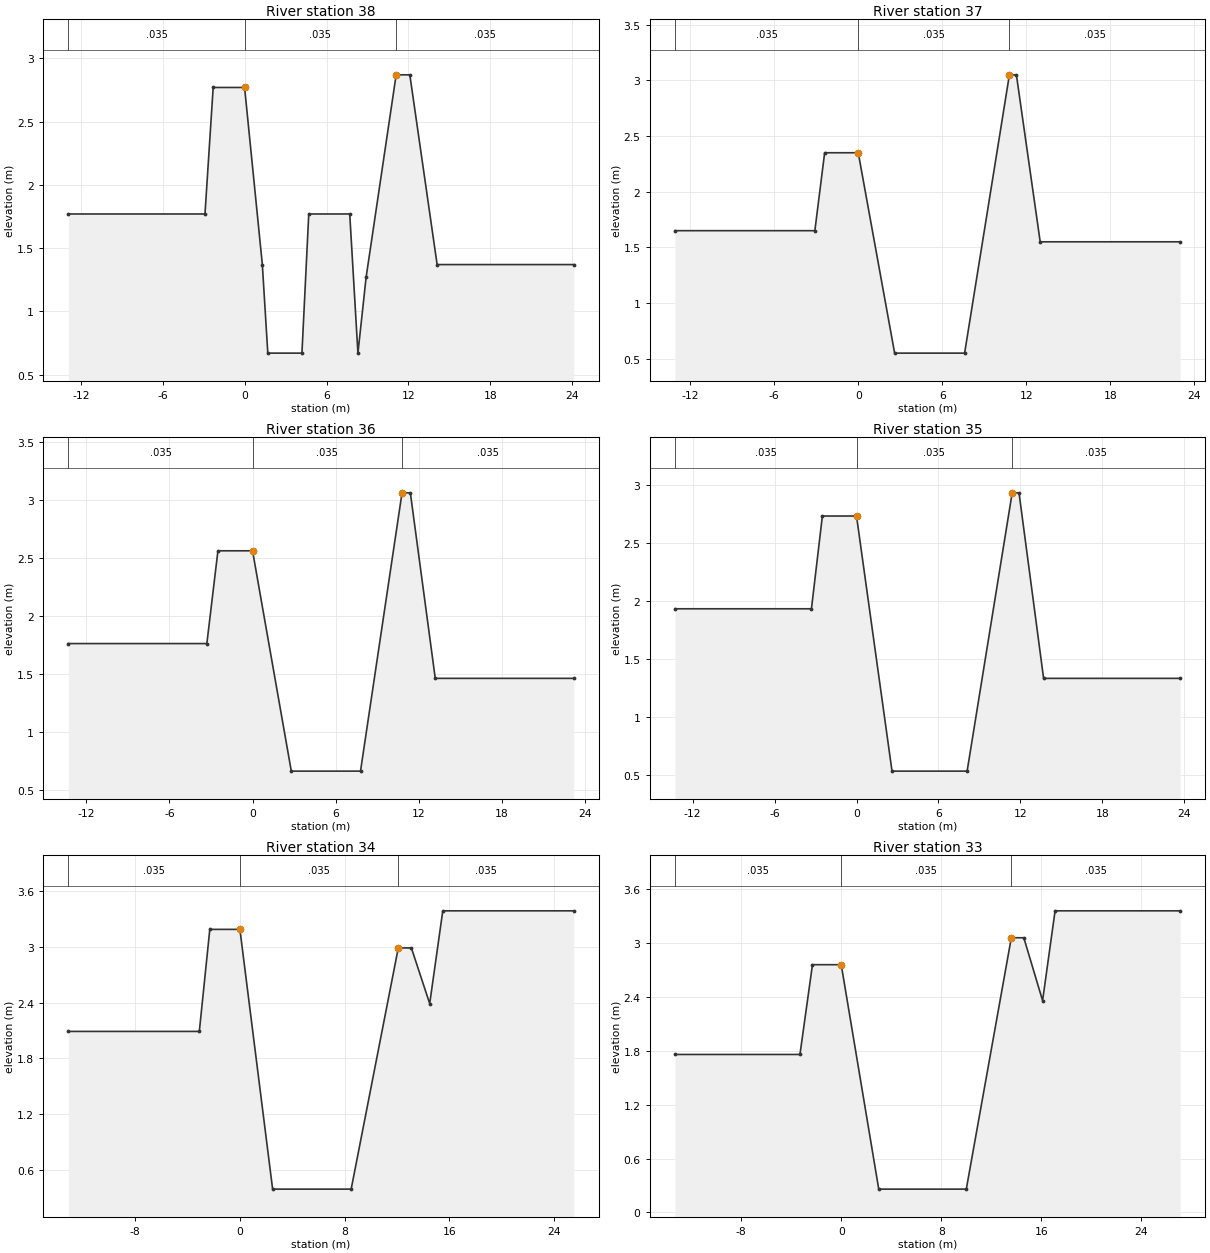
Type RM Length L Ch R = 1 ,38      ,50,50,50
#Sta/Elev= 15
   -12.9    1.77    -2.9    1.77    -2.3    2.77       0    2.77     1.3    1.37
     1.7     .67     4.2     .67     4.7    1.77     7.7    1.77     8.3     .67
     8.9    1.27    11.1    2.87    12.1    2.87    14.1    1.37    24.1    1.37
#Mann= 3 , 0 , 0
   -12.9    .035       0       0    .035       0    11.1    .035       0
#XS Ineff= 2 , 0
               0      20    11.1              20
Permanent Ineff=
       F       F
#Block Obstruct= 2 , 0
                            11.1
Bank Sta=0,11.1
XS Rating Curve= 0
Exp/Cntr=.3,.1

Type RM Length L Ch R = 1 ,37      ,50,50,50
#Sta/Elev= 10
   -13.1    1.65    -3.1    1.65    -2.4    2.35       0    2.35     2.6     .55
     7.6     .55    10.8    3.05    11.3    3.05      13    1.55      23    1.55
#Mann= 3 , 0 , 0
   -13.1    .035       0       0    .035       0    10.8    .035       0
#XS Ineff= 2 , 0
               0      20    10.8              20
Permanent Ineff=
       F       F
#Block Obstruct= 2 , 0
                            10.8
Bank Sta=0,10.8
XS Rating Curve= 0
Exp/Cntr=.3,.1

Type RM Length L Ch R = 1 ,36      ,50,50,50
#Sta/Elev= 10
   -13.3    1.76    -3.3    1.76    -2.5    2.56       0    2.56     2.8     .66
     7.8     .66    10.8    3.06    11.4    3.06    13.2    1.46    23.2    1.46
#Mann= 3 , 0 , 0
   -13.3    .035       0       0    .035       0    10.8    .035       0
#XS Ineff= 2 , 0
               0      20    10.8              20
Permanent Ineff=
       F       F
#Block Obstruct= 2 , 0
                            10.8
Bank Sta=0,10.8
XS Rating Curve= 0
Exp/Cntr=.3,.1

Type RM Length L Ch R = 1 ,35      ,50,50,50
#Sta/Elev= 10
   -13.3    1.93    -3.3    1.93    -2.5    2.73       0    2.73     2.6     .53
     8.1     .53    11.4    2.93    11.9    2.93    13.7    1.33    23.7    1.33
#Mann= 3 , 0 , 0
   -13.3    .035       0       0    .035       0    11.4    .035       0
#XS Ineff= 2 , 0
               0      20    11.4              20
Permanent Ineff=
       F       F
#Block Obstruct= 2 , 0
                            11.4
Bank Sta=0,11.4
XS Rating Curve= 0
Exp/Cntr=.3,.1

Type RM Length L Ch R = 1 ,34      ,50,50,50
#Sta/Elev= 11
   -13.1    2.09    -3.1    2.09    -2.3    3.19       0    3.19     2.5     .39
     8.5     .39    12.1    2.99    13.1    2.99    14.5    2.39    15.5    3.39
    25.5    3.39
#Mann= 3 , 0 , 0
   -13.1    .035       0       0    .035       0    12.1    .035       0
#XS Ineff= 2 , 0
               0      20    12.1              20
Permanent Ineff=
       F       F
#Block Obstruct= 2 , 0
                            12.1
Bank Sta=0,12.1
XS Rating Curve= 0
Exp/Cntr=.3,.1

Type RM Length L Ch R = 1 ,33      ,50,50,50
#Sta/Elev= 11
   -13.3    1.76    -3.3    1.76    -2.3    2.76       0    2.76       3     .26
      10     .26    13.6    3.06    14.6    3.06    16.1    2.36    17.1    3.36
    27.1    3.36
#Mann= 3 , 0 , 0
   -13.3    .035       0       0    .035       0    13.6    .035       0
#XS Ineff= 2 , 0
               0      20    13.6              20
Permanent Ineff=
       F       F
#Block Obstruct= 2 , 0
                            13.6
Bank Sta=0,13.6
XS Rating Curve= 0
Exp/Cntr=.3,.1

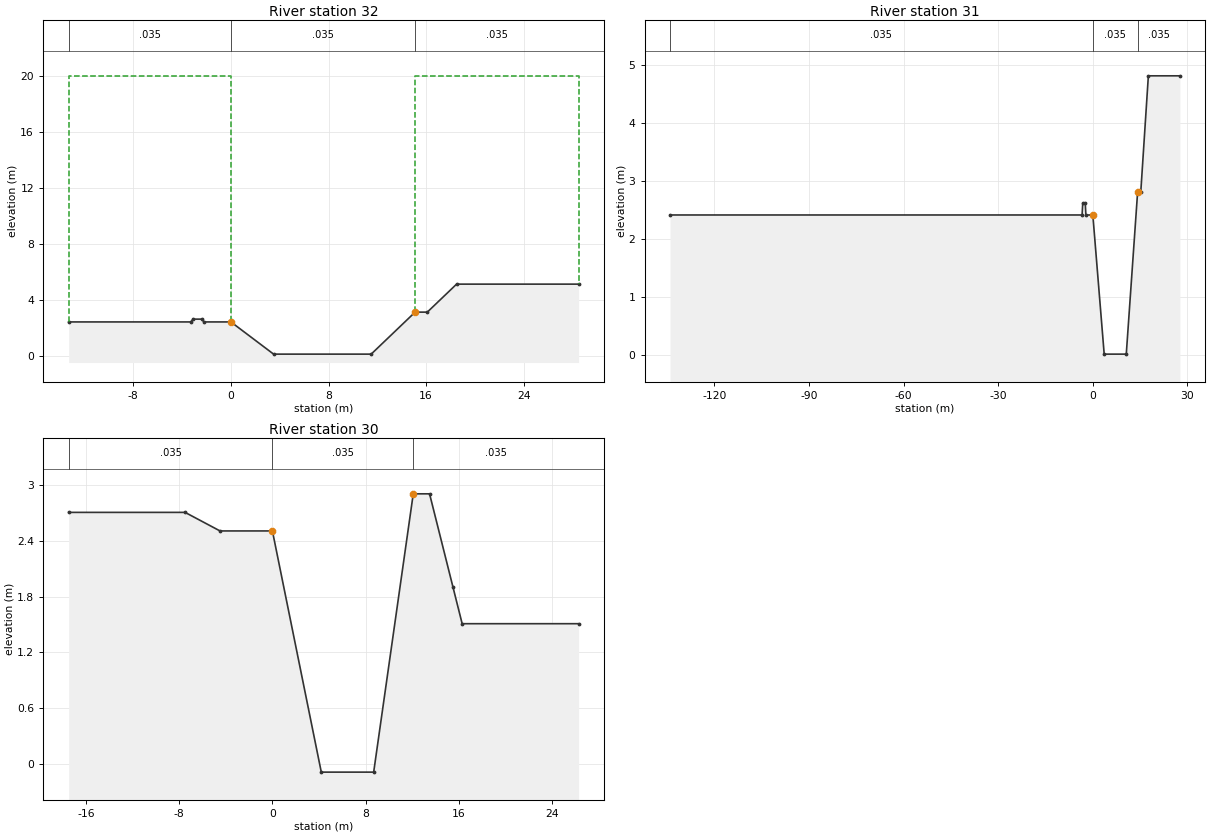
Type RM Length L Ch R = 1 ,32      ,50,50,50
#Sta/Elev= 12
   -13.3    2.42    -3.3    2.42    -3.1    2.62    -2.4    2.62    -2.2    2.42
       0    2.42     3.5     .12    11.5     .12    15.1    3.12    16.1    3.12
    18.5    5.12    28.5    5.12
#Mann= 3 , 0 , 0
   -13.3    .035       0       0    .035       0    15.1    .035       0
#XS Ineff= 2 , 0
               0      20    15.1              20
Permanent Ineff=
       F       F
#Block Obstruct= 2 , 0
                            15.1
Bank Sta=0,15.1
XS Rating Curve= 0
Exp/Cntr=.3,.1

Type RM Length L Ch R = 1 ,31      ,50,50,50
#Sta/Elev= 12
    -134    2.41    -3.4    2.41    -3.2    2.61    -2.4    2.61    -2.2    2.41
       0    2.41     3.6     .01    10.6     .01    14.2    2.81    15.2    2.81
    17.6    4.81    27.6    4.81
#Mann= 3 , 0 , 0
    -134    .035       0       0    .035       0    14.2    .035       0
#XS Ineff= 2 , 0
               0      20    14.2              20
Permanent Ineff=
       F       F
#Block Obstruct= 2 , 0
                            14.2
Bank Sta=0,14.2
XS Rating Curve= 0
Exp/Cntr=.3,.1

Type RM Length L Ch R = 1 ,30      ,50,50,50
#Sta/Elev= 11
   -17.5    2.71    -7.5    2.71    -4.5    2.51       0    2.51     4.2    -.09
     8.7    -.09    12.1    2.91    13.5    2.91    15.5    1.91    16.3    1.51
    26.3    1.51
#Mann= 3 , 0 , 0
   -17.5    .035       0       0    .035       0    12.1    .035       0
#XS Ineff= 2 , 0
               0      20    12.1              20
Permanent Ineff=
       F       F
#Block Obstruct= 2 , 0
                            12.1
Bank Sta=0,12.1
XS Rating Curve= 0
Exp/Cntr=.3,.1