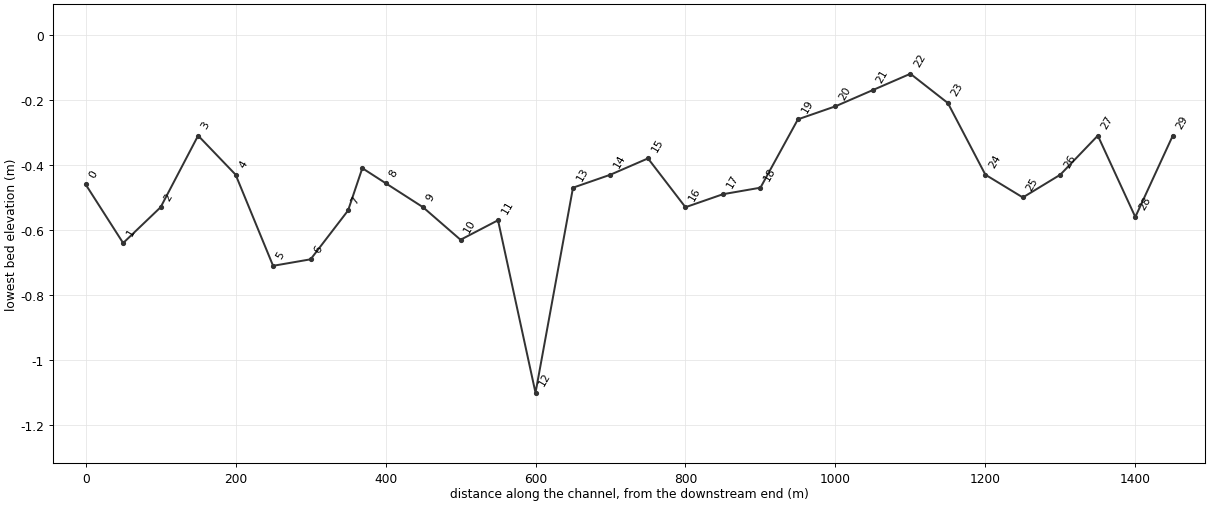
HEC-RAS study dsc.prj: dongsan

--- dsc.g01 (geometry) --- (continued)

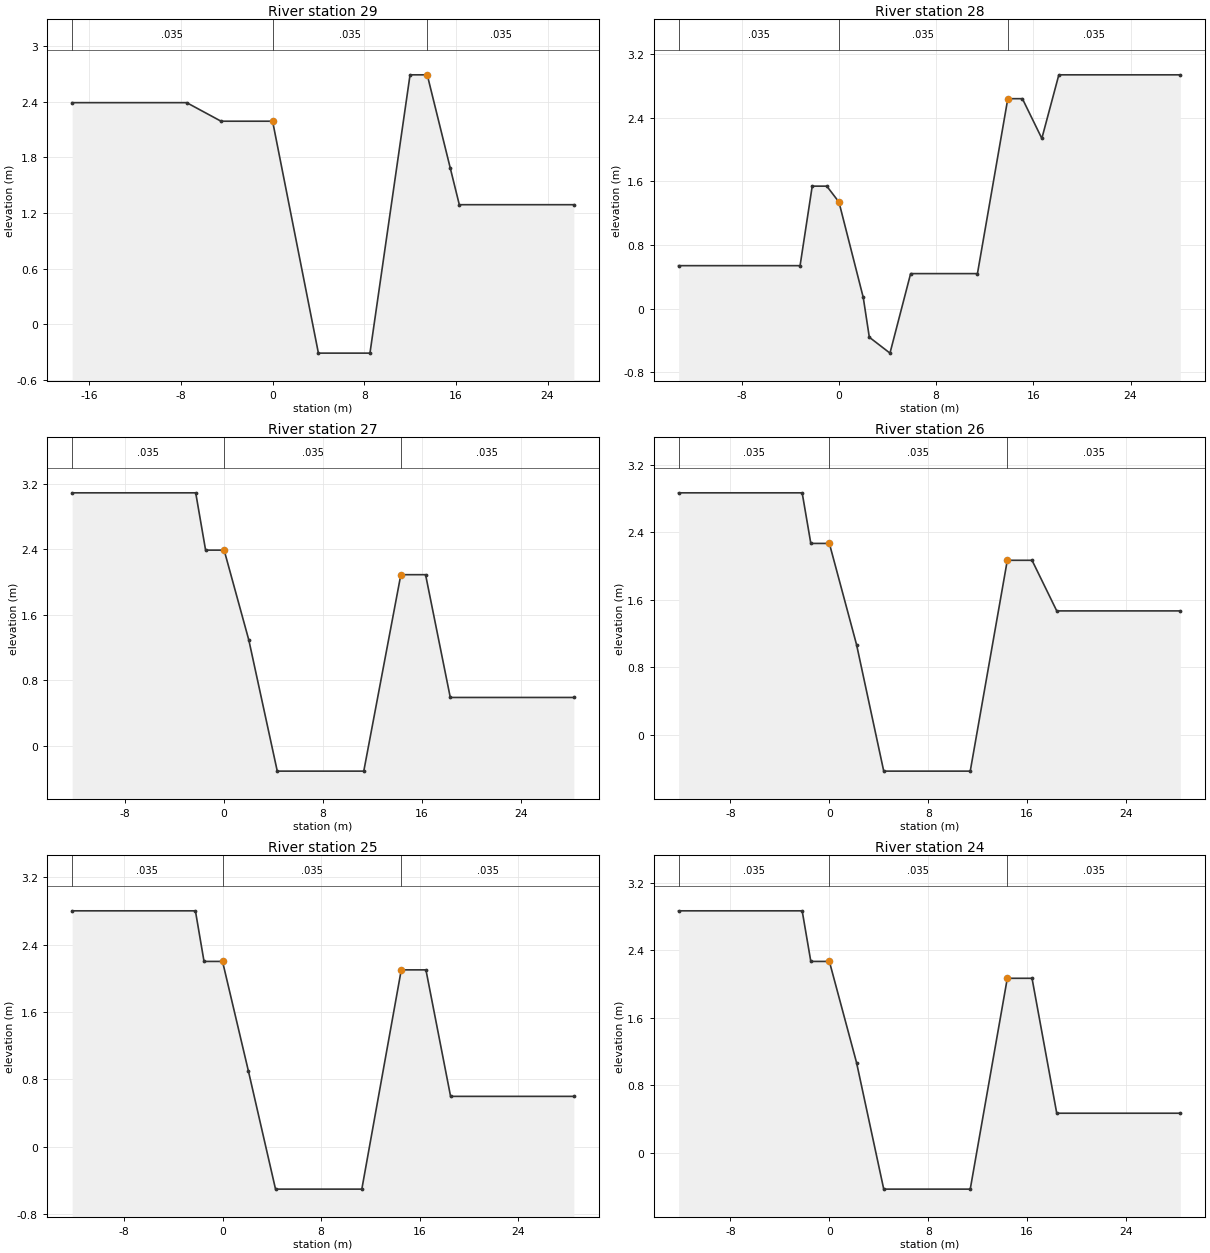
Type RM Length L Ch R = 1 ,29      ,50,50,50
#Sta/Elev= 11
   -17.5    2.39    -7.5    2.39    -4.5    2.19       0    2.19       4    -.31
     8.5    -.31      12    2.69    13.5    2.69    15.5    1.69    16.3    1.29
    26.3    1.29
#Mann= 3 , 0 , 0
   -17.5    .035       0       0    .035       0    13.5    .035       0
#XS Ineff= 2 , 0
               0      20    13.5              20
Permanent Ineff=
       F       F
#Block Obstruct= 2 , 0
                            14.4
Bank Sta=0,13.5
XS Rating Curve= 0
Exp/Cntr=.3,.1

Type RM Length L Ch R = 1 ,28      ,50,50,50
#Sta/Elev= 15
   -13.2     .54    -3.2     .54    -2.2    1.54      -1    1.54       0    1.34
       2     .14     2.5    -.36     4.2    -.56     5.9     .44    11.4     .44
    13.9    2.64    15.1    2.64    16.7    2.14    18.1    2.94    28.1    2.94
#Mann= 3 , 0 , 0
   -13.2    .035       0       0    .035       0    13.9    .035       0
#XS Ineff= 2 , 0
               0      20    13.9              20
Permanent Ineff=
       F       F
#Block Obstruct= 2 , 0
                            13.9
Bank Sta=0,13.9
XS Rating Curve= 0
Exp/Cntr=.3,.1

Type RM Length L Ch R = 1 ,27      ,50,50,50
#Sta/Elev= 11
   -12.3    3.09    -2.3    3.09    -1.5    2.39       0    2.39       2    1.29
     4.3    -.31    11.3    -.31    14.3    2.09    16.3    2.09    18.3     .59
    28.3     .59
#Mann= 3 , 0 , 0
   -12.3    .035       0       0    .035       0    14.3    .035       0
#XS Ineff= 2 , 0
               0      20    14.3              20
Permanent Ineff=
       F       F
#Block Obstruct= 2 , 0
                            14.3
Bank Sta=0,14.3
XS Rating Curve= 0
Exp/Cntr=.3,.1

Type RM Length L Ch R = 1 ,26      ,50,50,50
#Sta/Elev= 11
   -12.2    2.87    -2.2    2.87    -1.5    2.27       0    2.27     2.2    1.07
     4.4    -.43    11.4    -.43    14.4    2.07    16.4    2.07    18.4    1.47
    28.4    1.47
#Mann= 3 , 0 , 0
   -12.2    .035       0       0    .035       0    14.4    .035       0
#XS Ineff= 2 , 0
               0      20    14.4              20
Permanent Ineff=
       F       F
#Block Obstruct= 2 , 0
                            14.4
Bank Sta=0,14.4
XS Rating Curve= 0
Exp/Cntr=.3,.1

Type RM Length L Ch R = 1 ,25      ,50,50,50
#Sta/Elev= 11
   -12.2     2.8    -2.2     2.8    -1.5     2.2       0     2.2     2.1      .9
     4.3     -.5    11.3     -.5    14.5     2.1    16.5     2.1    18.5      .6
    28.5      .6
#Mann= 3 , 0 , 0
   -12.2    .035       0       0    .035       0    14.5    .035       0
#XS Ineff= 2 , 0
               0      20    14.5              20
Permanent Ineff=
       F       F
#Block Obstruct= 2 , 0
                            14.5
Bank Sta=0,14.5
XS Rating Curve= 0
Exp/Cntr=.3,.1

Type RM Length L Ch R = 1 ,24      ,50,50,50
#Sta/Elev= 11
   -12.2    2.87    -2.2    2.87    -1.5    2.27       0    2.27     2.2    1.07
     4.4    -.43    11.4    -.43    14.4    2.07    16.4    2.07    18.4     .47
    28.4     .47
#Mann= 3 , 0 , 0
   -12.2    .035       0       0    .035       0    14.4    .035       0
#XS Ineff= 2 , 0
               0      20    14.4              20
Permanent Ineff=
       F       F
#Block Obstruct= 2 , 0
                            14.4
Bank Sta=0,14.4
XS Rating Curve= 0
Exp/Cntr=.3,.1

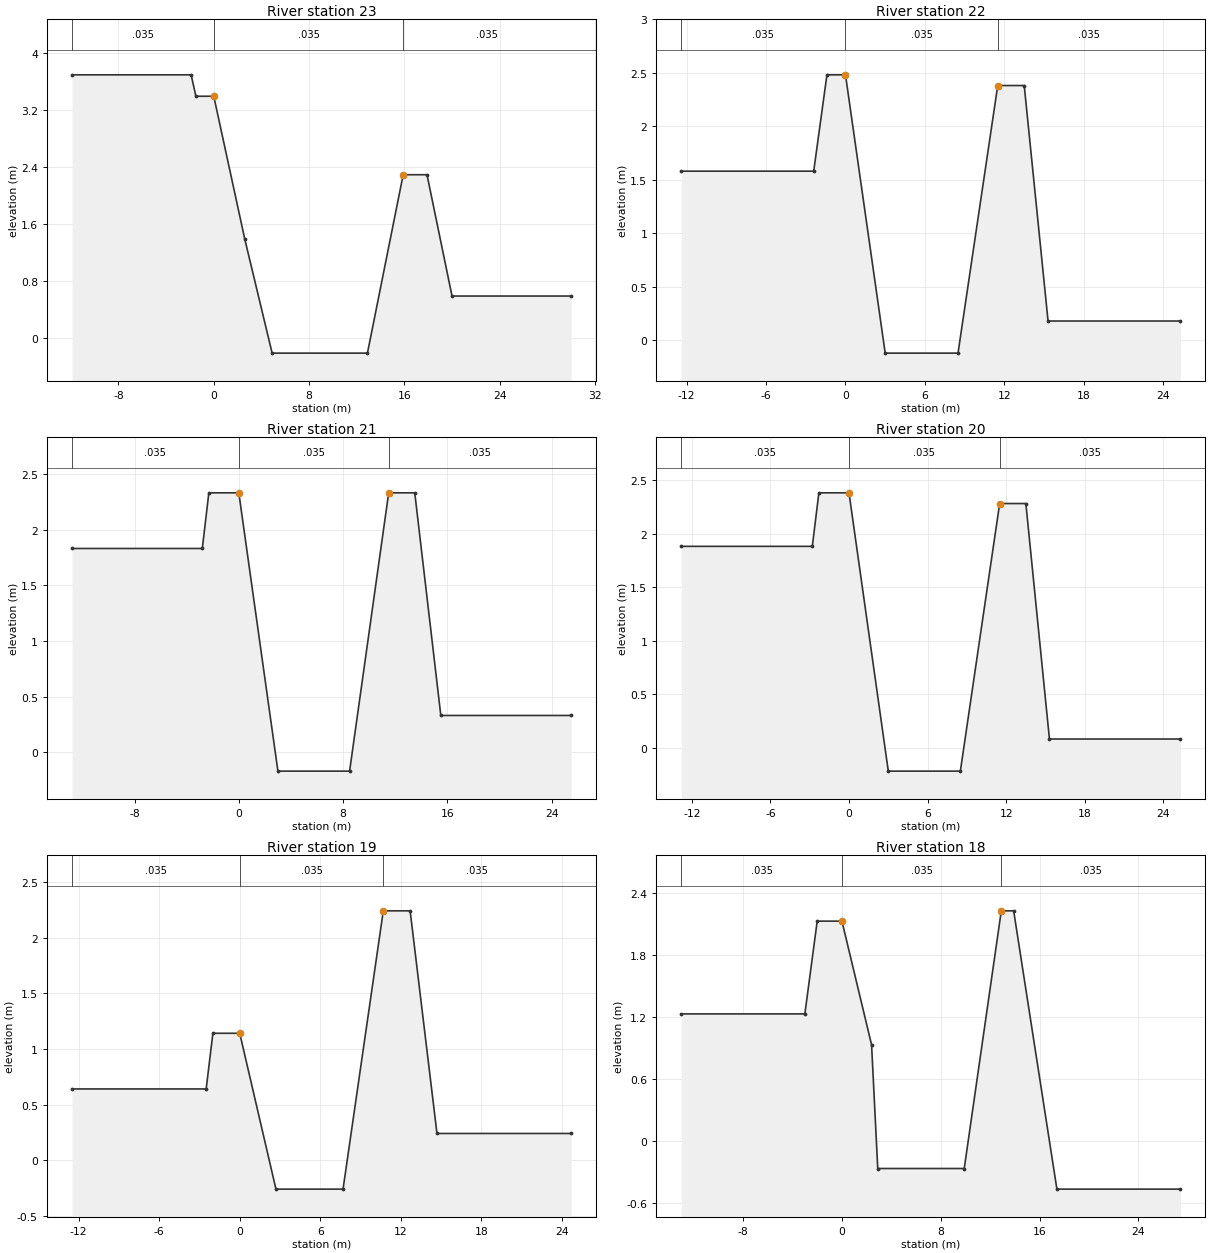
Type RM Length L Ch R = 1 ,23      ,50,50,50
#Sta/Elev= 11
   -11.9    3.69    -1.9    3.69    -1.5    3.39       0    3.39     2.6    1.39
     4.9    -.21    12.9    -.21    15.9    2.29    17.9    2.29      20     .59
      30     .59
#Mann= 3 , 0 , 0
   -11.9    .035       0       0    .035       0    15.9    .035       0
#XS Ineff= 2 , 0
               0      20    15.9              20
Permanent Ineff=
       F       F
#Block Obstruct= 2 , 0
                            15.9
Bank Sta=0,15.9
XS Rating Curve= 0
Exp/Cntr=.3,.1

Type RM Length L Ch R = 1 ,22      ,50,50,50
#Sta/Elev= 10
   -12.4    1.58    -2.4    1.58    -1.4    2.48       0    2.48       3    -.12
     8.5    -.12    11.5    2.38    13.5    2.38    15.3     .18    25.3     .18
#Mann= 3 , 0 , 0
   -12.4    .035       0       0    .035       0    11.5    .035       0
#XS Ineff= 2 , 0
               0      20    11.5              20
Permanent Ineff=
       F       F
#Block Obstruct= 2 , 0
                            11.5
Bank Sta=0,11.5
XS Rating Curve= 0
Exp/Cntr=.3,.1

Type RM Length L Ch R = 1 ,21      ,50,50,50
#Sta/Elev= 10
   -12.8    1.83    -2.8    1.83    -2.3    2.33       0    2.33       3    -.17
     8.5    -.17    11.5    2.33    13.5    2.33    15.5     .33    25.5     .33
#Mann= 3 , 0 , 0
   -12.8    .035       0       0    .035       0    11.5    .035       0
#XS Ineff= 2 , 0
               0      20    11.5              20
Permanent Ineff=
       F       F
#Block Obstruct= 2 , 0
                            11.5
Bank Sta=0,11.5
XS Rating Curve= 0
Exp/Cntr=.3,.1

Type RM Length L Ch R = 1 ,20      ,50,50,50
#Sta/Elev= 10
   -12.8    1.88    -2.8    1.88    -2.3    2.38       0    2.38       3    -.22
     8.5    -.22    11.5    2.28    13.5    2.28    15.3     .08    25.3     .08
#Mann= 3 , 0 , 0
   -12.8    .035       0       0    .035       0    11.5    .035       0
#XS Ineff= 2 , 0
               0      20    11.5              20
Permanent Ineff=
       F       F
#Block Obstruct= 2 , 0
                            11.5
Bank Sta=0,11.5
XS Rating Curve= 0
Exp/Cntr=.3,.1

Type RM Length L Ch R = 1 ,19      ,50,50,50
#Sta/Elev= 10
   -12.5     .64    -2.5     .64      -2    1.14       0    1.14     2.7    -.26
     7.7    -.26    10.7    2.24    12.7    2.24    14.7     .24    24.7     .24
#Mann= 3 , 0 , 0
   -12.5    .035       0       0    .035       0    10.7    .035       0
#XS Ineff= 2 , 0
               0      20    10.7              20
Permanent Ineff=
       F       F
#Block Obstruct= 2 , 0
                            10.7
Bank Sta=0,10.7
XS Rating Curve= 0
Exp/Cntr=.3,.1

Type RM Length L Ch R = 1 ,18      ,50,50,50
#Sta/Elev= 11
     -13    1.23      -3    1.23      -2    2.13       0    2.13     2.4     .93
     2.9    -.27     9.9    -.27    12.9    2.23    13.9    2.23    17.4    -.47
    27.4    -.47
#Mann= 3 , 0 , 0
     -13    .035       0       0    .035       0    12.9    .035       0
#XS Ineff= 2 , 0
               0      20    12.9              20
Permanent Ineff=
       F       F
#Block Obstruct= 2 , 0
                            12.9
Bank Sta=0,12.9
XS Rating Curve= 0
Exp/Cntr=.3,.1

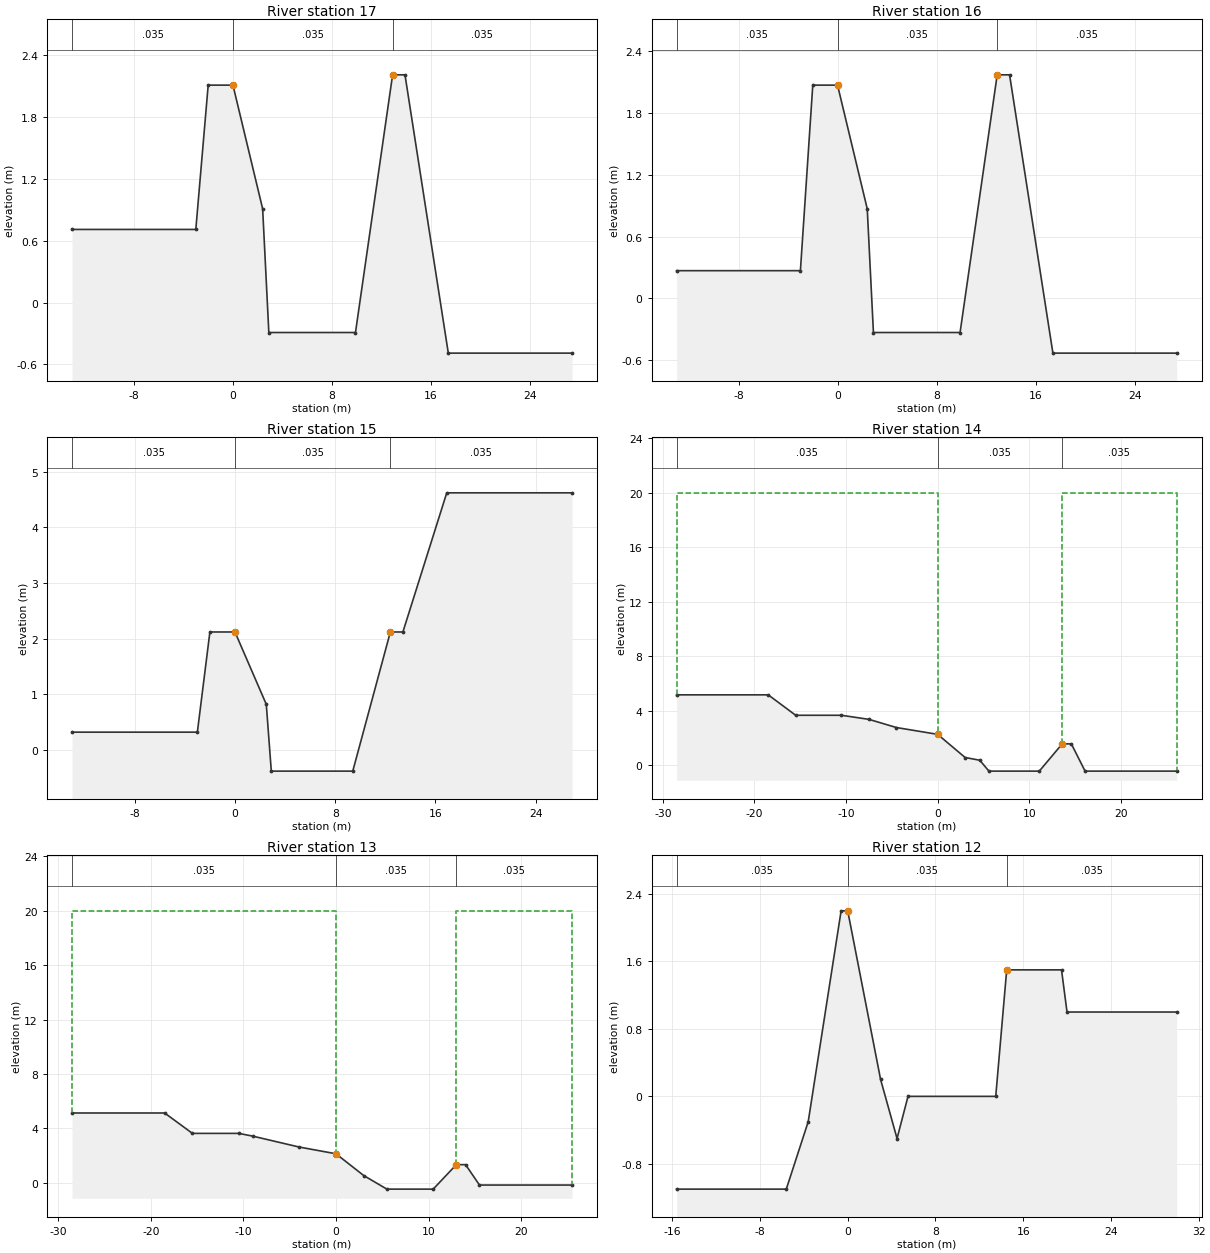
Type RM Length L Ch R = 1 ,17      ,50,50,50
#Sta/Elev= 11
     -13     .71      -3     .71      -2    2.11       0    2.11     2.4     .91
     2.9    -.29     9.9    -.29    12.9    2.21    13.9    2.21    17.4    -.49
    27.4    -.49
#Mann= 3 , 0 , 0
     -13    .035       0       0    .035       0    12.9    .035       0
#XS Ineff= 2 , 0
               0      20    12.9              20
Permanent Ineff=
       F       F
#Block Obstruct= 2 , 0
                            12.9
Bank Sta=0,12.9
XS Rating Curve= 0
Exp/Cntr=.3,.1

Type RM Length L Ch R = 1 ,16      ,50,50,50
#Sta/Elev= 11
     -13     .27      -3     .27      -2    2.07       0    2.07     2.4     .87
     2.9    -.33     9.9    -.33    12.9    2.17    13.9    2.17    17.4    -.53
    27.4    -.53
#Mann= 3 , 0 , 0
     -13    .035       0       0    .035       0    12.9    .035       0
#XS Ineff= 2 , 0
               0      20    12.9              20
Permanent Ineff=
       F       F
#Block Obstruct= 2 , 0
                            12.9
Bank Sta=0,12.9
XS Rating Curve= 0
Exp/Cntr=.3,.1

Type RM Length L Ch R = 1 ,15      ,50,50,50
#Sta/Elev= 11
     -13     .32      -3     .32      -2    2.12       0    2.12     2.5     .82
     2.9    -.38     9.4    -.38    12.4    2.12    13.4    2.12    16.9    4.62
    26.9    4.62
#Mann= 3 , 0 , 0
     -13    .035       0       0    .035       0    12.4    .035       0
#XS Ineff= 2 , 0
               0      20    12.4              20
Permanent Ineff=
       F       F
#Block Obstruct= 2 , 0
                            12.4
Bank Sta=0,12.4
XS Rating Curve= 0
Exp/Cntr=.3,.1

Type RM Length L Ch R = 1 ,14      ,50,50,50
#Sta/Elev= 15
   -28.5    5.17   -18.5    5.17   -15.5    3.67   -10.5    3.67    -7.5    3.37
    -4.5    2.77       0    2.27       3     .57     4.6     .37     5.6    -.43
    11.1    -.43    13.6    1.57    14.6    1.57    16.1    -.43    26.1    -.43
#Mann= 3 , 0 , 0
   -28.5    .035       0       0    .035       0    13.6    .035       0
#XS Ineff= 2 , 0
               0      20    13.6              20
Permanent Ineff=
       F       F
#Block Obstruct= 2 , 0
                            13.6
Bank Sta=0,13.6
XS Rating Curve= 0
Exp/Cntr=.3,.1

Type RM Length L Ch R = 1 ,13      ,50,50,50
#Sta/Elev= 14
   -28.5    5.13   -18.5    5.13   -15.5    3.63   -10.5    3.63      -9    3.43
      -4    2.63       0    2.13       3     .53     5.5    -.47    10.5    -.47
      13    1.33      14    1.33    15.5    -.17    25.5    -.17
#Mann= 3 , 0 , 0
   -28.5    .035       0       0    .035       0      13    .035       0
#XS Ineff= 2 , 0
               0      20      13              20
Permanent Ineff=
       F       F
#Block Obstruct= 2 , 0
                              13
Bank Sta=0,13
XS Rating Curve= 0
Exp/Cntr=.3,.1

Type RM Length L Ch R = 1 ,12      ,50,50,50
#Sta/Elev= 13
   -15.6    -1.1    -5.6    -1.1    -3.6     -.3     -.6     2.2       0     2.2
       3      .2     4.5     -.5     5.5       0    13.5       0    14.5     1.5
    19.5     1.5      20       1      30       1
#Mann= 3 , 0 , 0
   -15.6    .035       0       0    .035       0    14.5    .035       0
#XS Ineff= 2 , 0
               0      20    14.5              20
Permanent Ineff=
       F       F
#Block Obstruct= 2 , 0
                            14.5
Bank Sta=0,14.5
XS Rating Curve= 0
Exp/Cntr=.3,.1

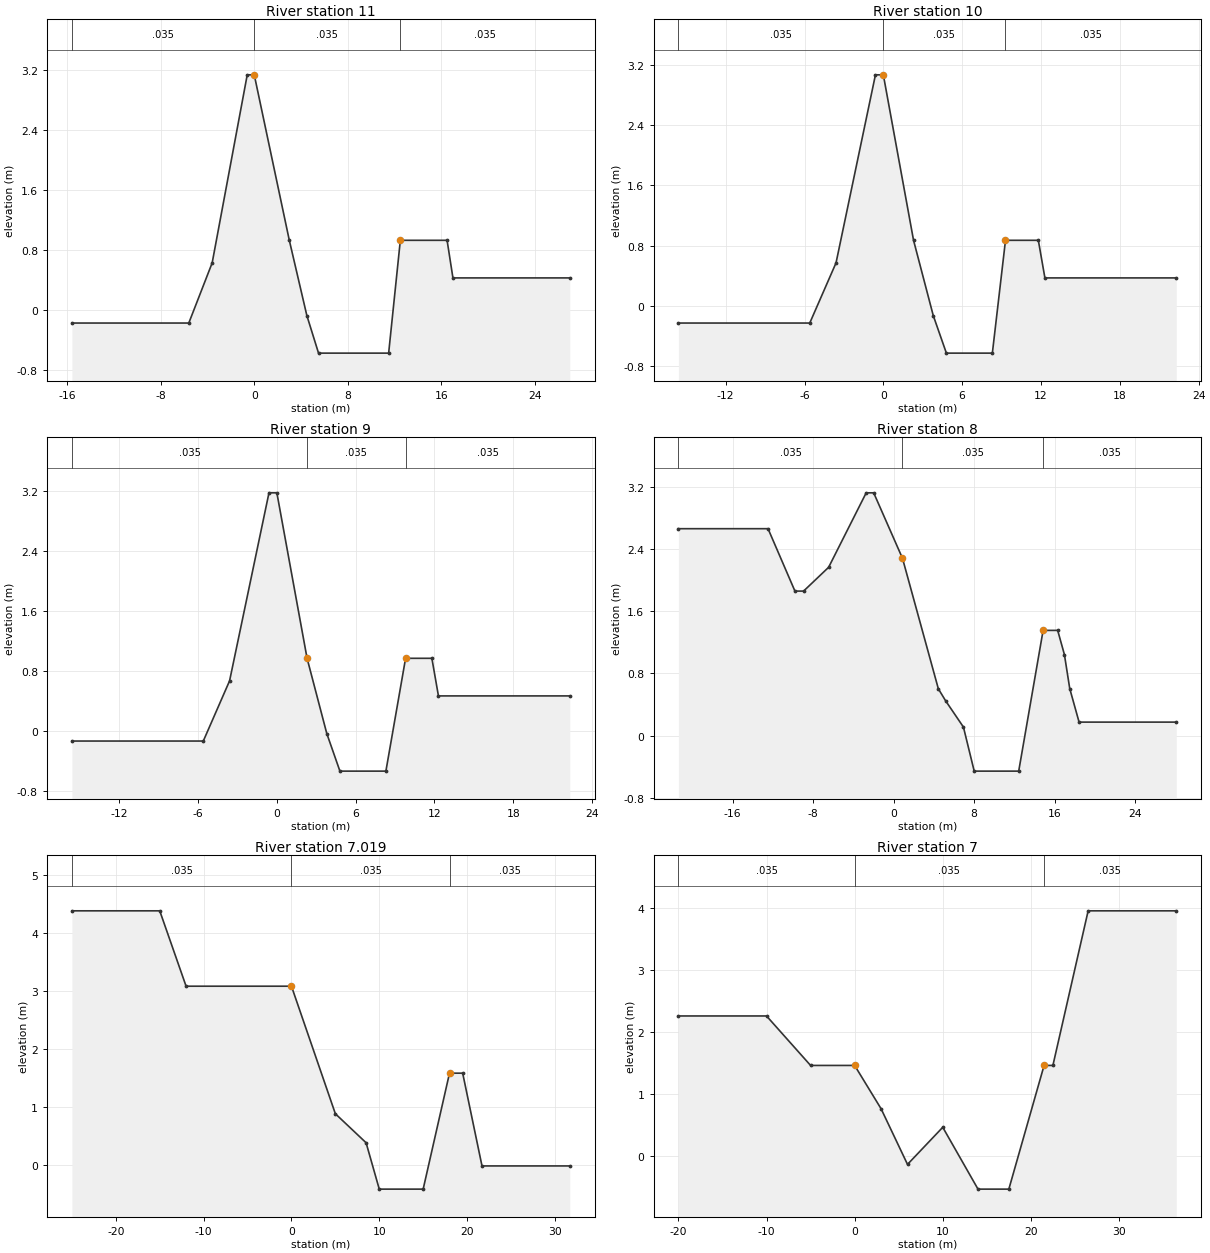
Type RM Length L Ch R = 1 ,11      ,50,50,50
#Sta/Elev= 13
   -15.6    -.17    -5.6    -.17    -3.6     .63     -.6    3.13       0    3.13
       3     .93     4.5    -.07     5.5    -.57    11.5    -.57    12.5     .93
    16.5     .93      17     .43      27     .43
#Mann= 3 , 0 , 0
   -15.6    .035       0       0    .035       0    12.5    .035       0
#XS Ineff= 2 , 0
               0      20    12.5              20
Permanent Ineff=
       F       F
#Block Obstruct= 2 , 0
                            12.5
Bank Sta=0,12.5
XS Rating Curve= 0
Exp/Cntr=.3,.1

Type RM Length L Ch R = 1 ,10      ,50,50,50
#Sta/Elev= 13
   -15.6    -.23    -5.6    -.23    -3.6     .57     -.6    3.07       0    3.07
     2.3     .87     3.8    -.13     4.8    -.63     8.3    -.63     9.3     .87
    11.8     .87    12.3     .37    22.3     .37
#Mann= 3 , 0 , 0
   -15.6    .035       0       0    .035       0     9.3    .035       0
#XS Ineff= 2 , 0
               0      20     9.3              20
Permanent Ineff=
       F       F
#Block Obstruct= 2 , 0
                             9.3
Bank Sta=0,9.3
XS Rating Curve= 0
Exp/Cntr=.3,.1

Type RM Length L Ch R = 1 ,9       ,50,50,50
#Sta/Elev= 13
   -15.6    -.13    -5.6    -.13    -3.6     .67     -.6    3.17       0    3.17
     2.3     .97     3.8    -.03     4.8    -.53     8.3    -.53     9.8     .97
    11.8     .97    12.3     .47    22.3     .47
#Mann= 3 , 0 , 0
   -15.6    .035       0     2.3    .035       0     9.8    .035       0
#XS Ineff= 2 , 0
             2.3      20     9.8              20
Permanent Ineff=
       F       F
#Block Obstruct= 2 , 0
             2.3             9.8
Bank Sta=2.3,9.8
XS Rating Curve= 0
Exp/Cntr=.3,.1

Type RM Length L Ch R = 1 ,8       ,31,31,31
#Sta/Elev= 19
 -21.402    2.66 -12.489    2.66  -9.815   1.858  -8.954   1.858  -6.464   2.164
   -2.73   3.121  -1.983   3.121     .88   2.279   4.445    .602   5.158     .45
    6.94     .11    8.01   -.456  12.436   -.456  14.862   1.353  16.311   1.353
   16.98   1.042   17.51    .605  18.438    .174  28.102    .174
#Mann= 3 , 0 , 0
 -21.402    .035       0     .88    .035       0  14.862    .035       0
#XS Ineff= 2 , 0
        .8802469      2014.86173              20
Permanent Ineff=
       F       F
#Block Obstruct= 2 , 0
                        14.86173
Bank Sta=.88,14.862
XS Rating Curve= 0
Exp/Cntr=.3,.1

Type RM Length L Ch R = 1 ,7.019   ,19,19,19
#Sta/Elev= 12
     -25    4.39     -15    4.39     -12    3.09       0    3.09       5     .89
     8.5     .39      10    -.41      15    -.41      18    1.59    19.5    1.59
    21.7    -.01    31.7    -.01
#Mann= 3 , 0 , 0
     -25    .035       0       0    .035       0      18    .035       0
#XS Ineff= 2 , 0
               0      20      18              20
Permanent Ineff=
       F       F
#Block Obstruct= 2 , 0
                              18
Bank Sta=0,18
XS Rating Curve= 0
Exp/Cntr=.3,.1

Type RM Length L Ch R = 1 ,7       ,50,50,50
#Sta/Elev= 13
     -20    2.26     -10    2.26      -5    1.46       0    1.46       3     .76
       6    -.14      10     .46      14    -.54    17.5    -.54    21.5    1.46
    22.5    1.46    26.5    3.96    36.5    3.96
#Mann= 3 , 0 , 0
     -20    .035       0       0    .035       0    21.5    .035       0
#XS Ineff= 2 , 0
               0      20    21.5              20
Permanent Ineff=
       F       F
#Block Obstruct= 2 , 0
                            21.5
Bank Sta=0,21.5
XS Rating Curve= 0
Exp/Cntr=.3,.1

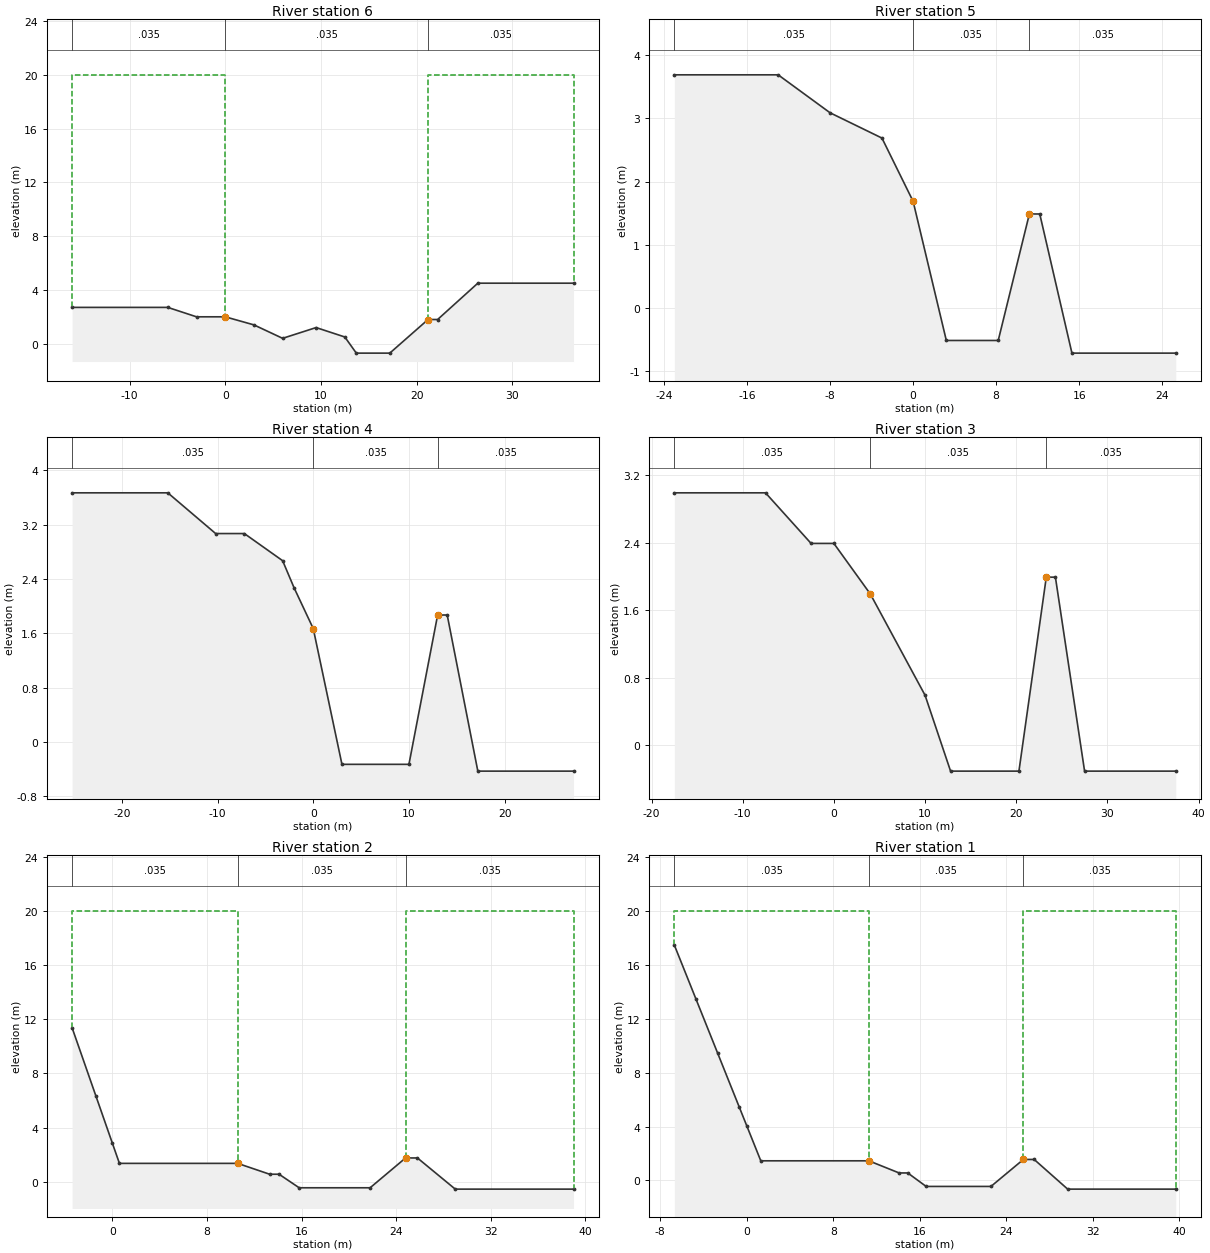
Type RM Length L Ch R = 1 ,6       ,50,50,50
#Sta/Elev= 14
     -16    2.71      -6    2.71      -3    2.01       0    2.01       3    1.41
       6     .41     9.5    1.21    12.5     .51    13.7    -.69    17.2    -.69
    21.2    1.81    22.2    1.81    26.4    4.51    36.4    4.51
#Mann= 3 , 0 , 0
     -16    .035       0       0    .035       0    21.2    .035       0
#XS Ineff= 2 , 0
               0      20    21.2              20
Permanent Ineff=
       F       F
#Block Obstruct= 2 , 0
                            21.2
Bank Sta=0,21.2
XS Rating Curve= 0
Exp/Cntr=.3,.1

Type RM Length L Ch R = 1 ,5       ,50,50,50
#Sta/Elev= 11
     -23    3.69     -13    3.69      -8    3.09      -3    2.69       0    1.69
     3.2    -.51     8.2    -.51    11.2    1.49    12.2    1.49    15.3    -.71
    25.3    -.71
#Mann= 3 , 0 , 0
     -23    .035       0       0    .035       0    11.2    .035       0
#XS Ineff= 2 , 0
               0      20    11.2              20
Permanent Ineff=
       F       F
#Block Obstruct= 2 , 0
                            11.2
Bank Sta=0,11.2
XS Rating Curve= 0
Exp/Cntr=.3,.1

Type RM Length L Ch R = 1 ,4       ,50,50,50
#Sta/Elev= 13
   -25.2    3.67   -15.2    3.67   -10.2    3.07    -7.2    3.07    -3.2    2.67
      -2    2.27       0    1.67       3    -.33      10    -.33      13    1.87
      14    1.87    17.2    -.43    27.2    -.43
#Mann= 3 , 0 , 0
   -25.2    .035       0       0    .035       0      13    .035       0
#XS Ineff= 2 , 0
               0      20      13              20
Permanent Ineff=
       F       F
#Block Obstruct= 2 , 0
                              13
Bank Sta=0,13
XS Rating Curve= 0
Exp/Cntr=.3,.1

Type RM Length L Ch R = 1 ,3       ,50,50,50
#Sta/Elev= 12
   -17.5    2.99    -7.5    2.99    -2.5    2.39       0    2.39       4    1.79
      10     .59    12.8    -.31    20.3    -.31    23.3    1.99    24.3    1.99
    27.5    -.31    37.5    -.31
#Mann= 3 , 0 , 0
   -17.5    .035       0       4    .035       0    23.3    .035       0
#XS Ineff= 2 , 0
               4      20    23.3              20
Permanent Ineff=
       F       F
#Block Obstruct= 2 , 0
               4            23.3
Bank Sta=4,23.3
XS Rating Curve= 0
Exp/Cntr=.3,.1

Type RM Length L Ch R = 1 ,2       ,50,50,50
#Sta/Elev= 13
    -3.4   11.37    -1.4    6.37       0    2.87      .6    1.37    10.6    1.37
    13.3     .57    14.1     .57    15.8    -.43    21.8    -.43    24.8    1.77
    25.8    1.77      29    -.53      39    -.53
#Mann= 3 , 0 , 0
    -3.4    .035       0    10.6    .035       0    24.8    .035       0
#XS Ineff= 2 , 0
            10.6      20    24.8              20
Permanent Ineff=
       F       F
#Block Obstruct= 2 , 0
            10.6            24.8
Bank Sta=10.6,24.8
XS Rating Curve= 0
Exp/Cntr=.3,.1

Type RM Length L Ch R = 1 ,1       ,50,50,50
#Sta/Elev= 15
    -6.7   17.46    -4.7   13.46    -2.7    9.46     -.7    5.46       0    4.06
     1.3    1.46    11.3    1.46    14.1     .56    14.9     .56    16.6    -.44
    22.6    -.44    25.6    1.56    26.6    1.56    29.7    -.64    39.7    -.64
#Mann= 3 , 0 , 0
    -6.7    .035       0    11.3    .035       0    25.6    .035       0
#XS Ineff= 2 , 0
            11.3      20    25.6              20
Permanent Ineff=
       F       F
#Block Obstruct= 2 , 0
            11.3            25.6
Bank Sta=11.3,25.6
XS Rating Curve= 0
Exp/Cntr=.3,.1

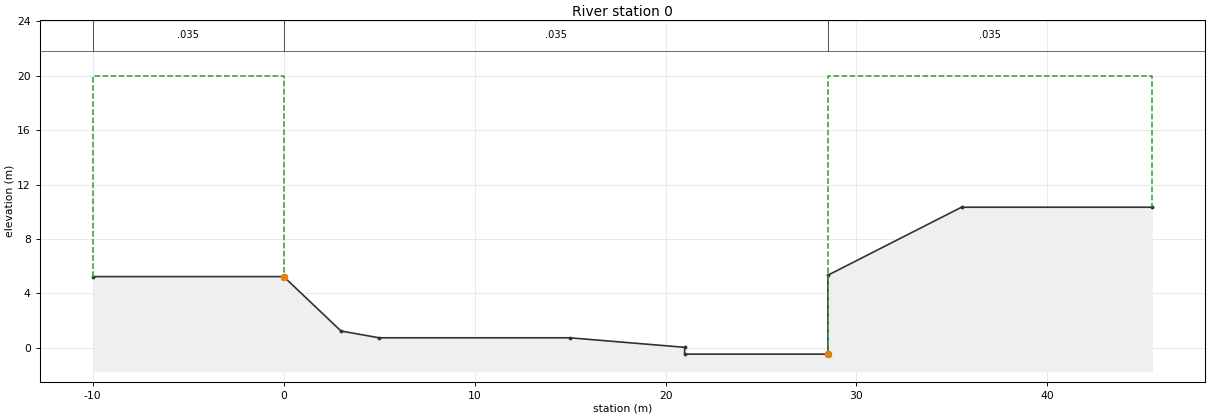
Type RM Length L Ch R = 1 ,0       ,0,0,0
#Sta/Elev= 11
     -10    5.24       0    5.24       3    1.24       5     .74      15     .74
      21     .04      21    -.46    28.5    -.46    28.5    5.34    35.5   10.34
    45.5   10.34
#Mann= 3 , 0 , 0
     -10    .035       0       0    .035       0    28.5    .035       0
#XS Ineff= 2 , 0
               0      20    28.5              20
Permanent Ineff=
       F       F
#Block Obstruct= 2 , 0
                            28.5
Bank Sta=0,28.5
XS Rating Curve= 0
Exp/Cntr=.3,.1

Chan Stop Cuts=-1