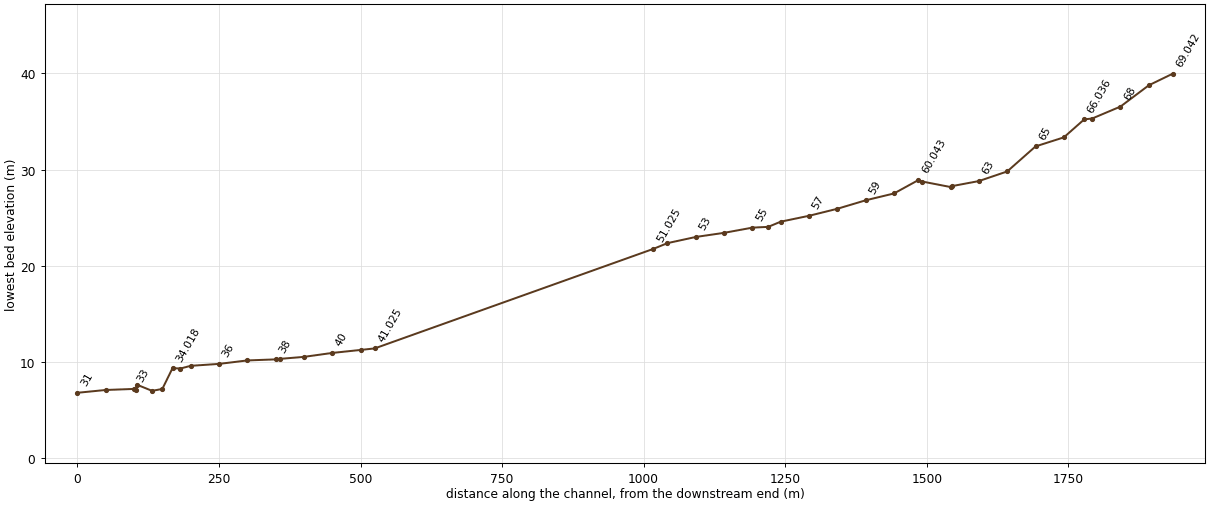
--- sukok.prj (project) ---

Proj Title=sukok
Current Plan=p01
Default Exp/Contr=.3,.1
SI Units
Geom File=g01
Flow File=f01
Plan File=p01
Y Axis Title=Elevation
X Axis Title(PF)=Main Channel Distance
X Axis Title(XS)=Station
BEGIN DESCRIPTION:
           BACK WATER COMPUTATION
      APPLICATION OF HEC-2 BY Samju Construction Engineering
      sukok-ch: 10,20,30,50,80 yr
END DESCRIPTION:
DSS Export Rating Curves= 0
DSS Export Rating Curve Sorted= 0
DSS Export Volume Flow Curves= 0
DXF OffsetX= 0
DXF OffsetY= 0
DXF ScaleX= 1
DXF ScaleY= 10

--- sukok.p01 (plan) ---

Plan Title=Imported Plan 01
Version=Version 3.0.1  Mar 2001
Short Identifier=Imported Pla
Geom File=g01
Flow File=f01
Subcritical Flow
K Sum by GR= 0
Std Step Tol= 0.003
Critical Tol= 0.003
Num of Std Step Trials= 20
Max Error Tol= 0.1
Flow Tol Ratio= 0.001
Split Flow NTrial= 30
Split Flow Tol= 0.02
Split Flow Ratio= 0.02
Log Output Level= 0
Friction Slope Method= 1
Unsteady Friction Slope Method= 2
Parabolic Critical Depth
Global Vel Dist= 0 , 0 , 0
Global Log Level= 0
CheckData=True
Encroach Param=-1 ,0,0, 0
Computation Interval=1HOUR
Output Interval=1HOUR
Run HTab= 0
Run UNet= 0
Run PostProcess= 0
UNET Theta= 1
UNET ZTol= 0.02
UNET ZSATol= 0.1
UNET MxIter= 20
UNET MaxInSteps= 20
UNET DtIC= 0
UNET DtMin= 0
UNET MaxCRTS= 20
UNET WFStab= 2
UNET SFStab= 1
UNET WFX= 1
UNET SFX= 1
UNET Convert EG Bridges=-1
UNET Use Existing IB Tables=-1
Instantaneous Interval=1HOUR
Write IC File= 0
Write Velocity= 0
Write Detailed= 0

--- sukok.f01 (steady flow) ---

Flow Title=Imported Flow 01
Version=Version 3.0.1  Mar 2001
Number of Profiles= 5
Profile Names=10yr,20yr,30yr,50yr,80yr
River Rch & RM=RIVER-1,Reach-1         ,69.042
   18.07   19.91   20.98   22.34    23.5
River Rch & RM=RIVER-1,Reach-1         ,30
   27.74   30.59   32.26   34.36   36.29
River Rch & RM=SOOKOK,SOOKOK          ,69.042
   18.07   19.91   20.98   22.34    23.5
River Rch & RM=SOOKOK,SOOKOK          ,30
   27.74   30.59   32.26   34.36   36.29
Boundary for River Rch & Prof#=SOOKOK,SOOKOK          , 1
Up Type= 0
Dn Type= 3
Dn Slope=.011
Boundary for River Rch & Prof#=SOOKOK,SOOKOK          , 2
Up Type= 0
Dn Type= 3
Dn Slope=.011
Boundary for River Rch & Prof#=SOOKOK,SOOKOK          , 3
Up Type= 0
Dn Type= 3
Dn Slope=.011
Boundary for River Rch & Prof#=SOOKOK,SOOKOK          , 4
Up Type= 0
Dn Type= 3
Dn Slope=.011
Boundary for River Rch & Prof#=SOOKOK,SOOKOK          , 5
Up Type= 0
Dn Type= 3
Dn Slope=.011
DSS Import GetInterval= 0
DSS Import GetPeak= 0
DSS Import FillOption= 0

--- sukok.g01 (geometry) ---

Geom Title=Imported Geom 01
Version=Version 3.0.1  Mar 2001

River Reach=SOOKOK          ,SOOKOK
Reach XY= 2
              .5             .95              .5             .05

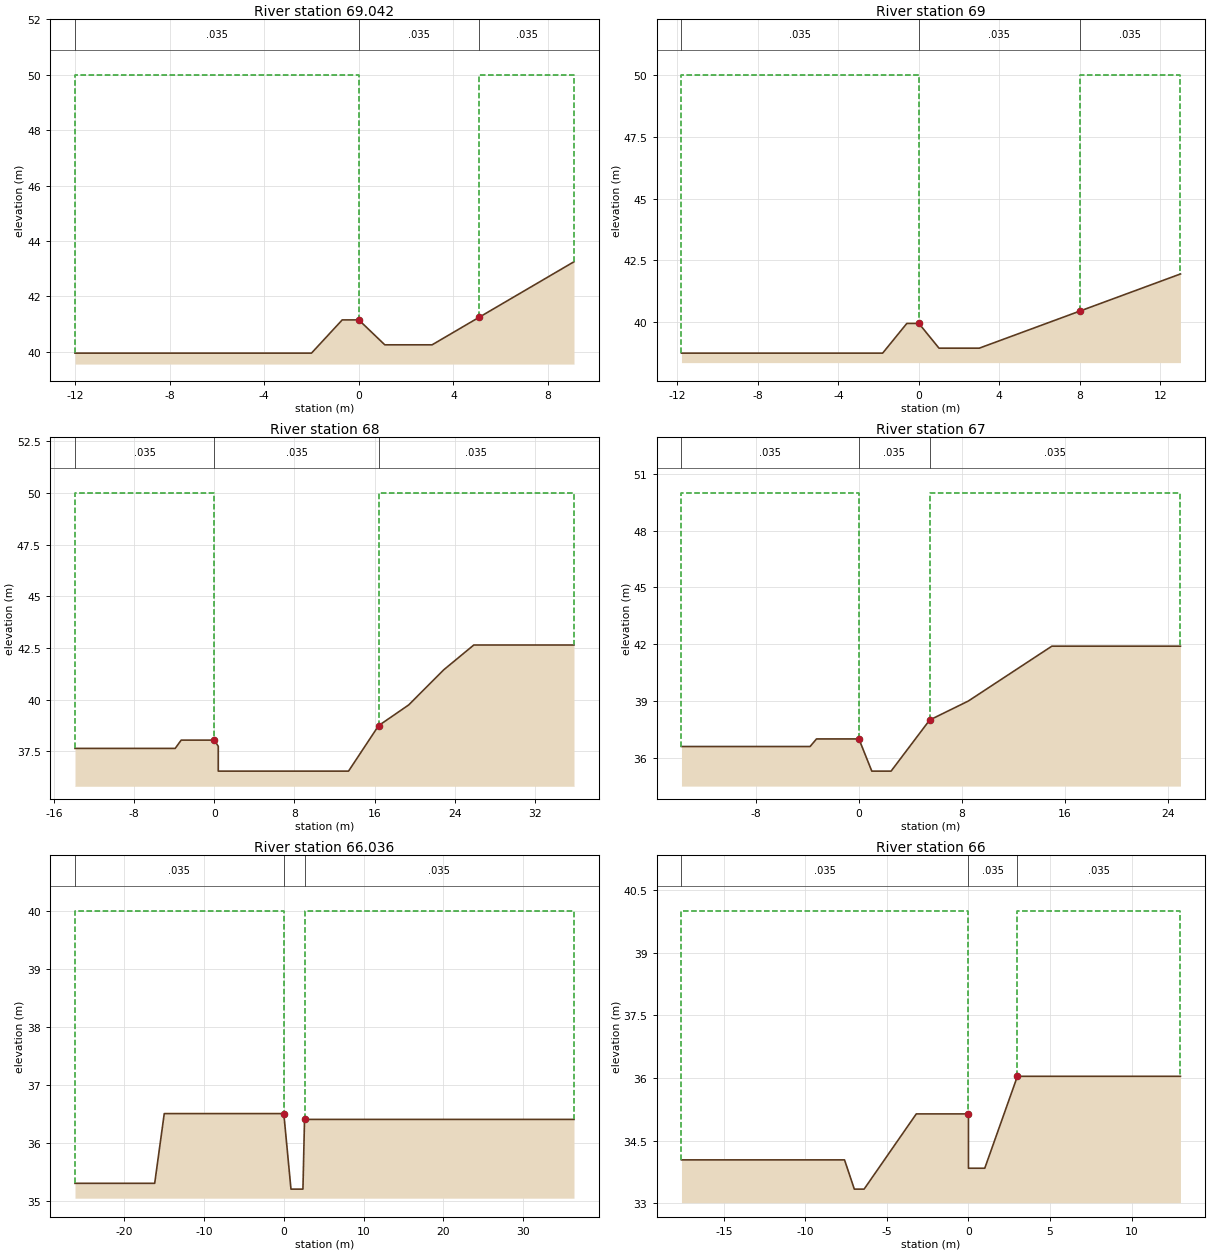
Type RM Length L Ch R = 1 ,69.042  ,42,42,42
#Sta/Elev= 9
     -12   39.95      -2   39.95     -.7   41.15       0   41.15     1.1   40.25
     3.1   40.25     5.1   41.25     7.1   42.25     9.1   43.25
#Mann= 3 , 0 , 0
     -12    .035       0       0    .035       0     5.1    .035       0
#XS Ineff= 2 , 0
               0      50     5.1              50
Permanent Ineff=
       F       F
#Block Obstruct= 2 , 0
                             5.1
Bank Sta=0,5.1
XS Rating Curve= 0
Exp/Cntr=.3,.1

Type RM Length L Ch R = 1 ,69      ,50,50,50
#Sta/Elev= 8
   -11.8   38.75    -1.8   38.75     -.6   39.95       0   39.95       1   38.95
       3   38.95       8   40.45      13   41.95
#Mann= 3 , 0 , 0
   -11.8    .035       0       0    .035       0       8    .035       0
#XS Ineff= 2 , 0
               0      50       8              50
Permanent Ineff=
       F       F
#Block Obstruct= 2 , 0
                               8
Bank Sta=0,8
XS Rating Curve= 0
Exp/Cntr=.3,.1

Type RM Length L Ch R = 1 ,68      ,50,50,50
#Sta/Elev= 12
   -13.9   37.64    -3.9   37.64    -3.3   38.04       0   38.04      .4   37.74
      .4   36.54    13.4   36.54    16.4   38.74    19.4   39.74    22.9   41.44
    25.9   42.64    35.9   42.64
#Mann= 3 , 0 , 0
   -13.9    .035       0       0    .035       0    16.4    .035       0
#XS Ineff= 2 , 0
               0      50    16.4              50
Permanent Ineff=
       F       F
#Block Obstruct= 2 , 0
                            16.4
Bank Sta=0,16.4
XS Rating Curve= 0
Exp/Cntr=.3,.1

Type RM Length L Ch R = 1 ,67      ,14,14,14
#Sta/Elev= 10
   -13.8    36.6    -3.8    36.6    -3.3      37       0      37       1    35.3
     2.5    35.3     5.5      38     8.5      39      15    41.9      25    41.9
#Mann= 3 , 0 , 0
   -13.8    .035       0       0    .035       0     5.5    .035       0
#XS Ineff= 2 , 0
               0      50     5.5              50
Permanent Ineff=
       F       F
#Block Obstruct= 2 , 0
                             5.5
Bank Sta=0,5.5
XS Rating Curve= 0
Exp/Cntr=.3,.1

Type RM Length L Ch R = 1 ,66.036  ,36,36,36
#Sta/Elev= 8
   -26.2   35.31   -16.2   35.31     -15   36.51       0   36.51      .9   35.21
     2.4   35.21     2.6   36.41   36.41   36.41
#Mann= 3 , 0 , 0
   -26.2    .035       0       0    .035       0     2.6    .035       0
#XS Ineff= 2 , 0
               0      40     2.6              40
Permanent Ineff=
       F       F
#Block Obstruct= 2 , 0
                             2.6
Bank Sta=0,2.6
XS Rating Curve= 0
Exp/Cntr=.3,.1

Type RM Length L Ch R = 1 ,66      ,50,50,50
#Sta/Elev= 10
   -17.6   34.04    -7.6   34.04      -7   33.34    -6.4   33.34    -3.2   35.14
       0   35.14       0   33.84       1   33.84       3   36.04      13   36.04
#Mann= 3 , 0 , 0
   -17.6    .035       0       0    .035       0       3    .035       0
#XS Ineff= 2 , 0
               0      40       3              40
Permanent Ineff=
       F       F
#Block Obstruct= 2 , 0
                               3
Bank Sta=0,3
XS Rating Curve= 0
Exp/Cntr=.3,.1

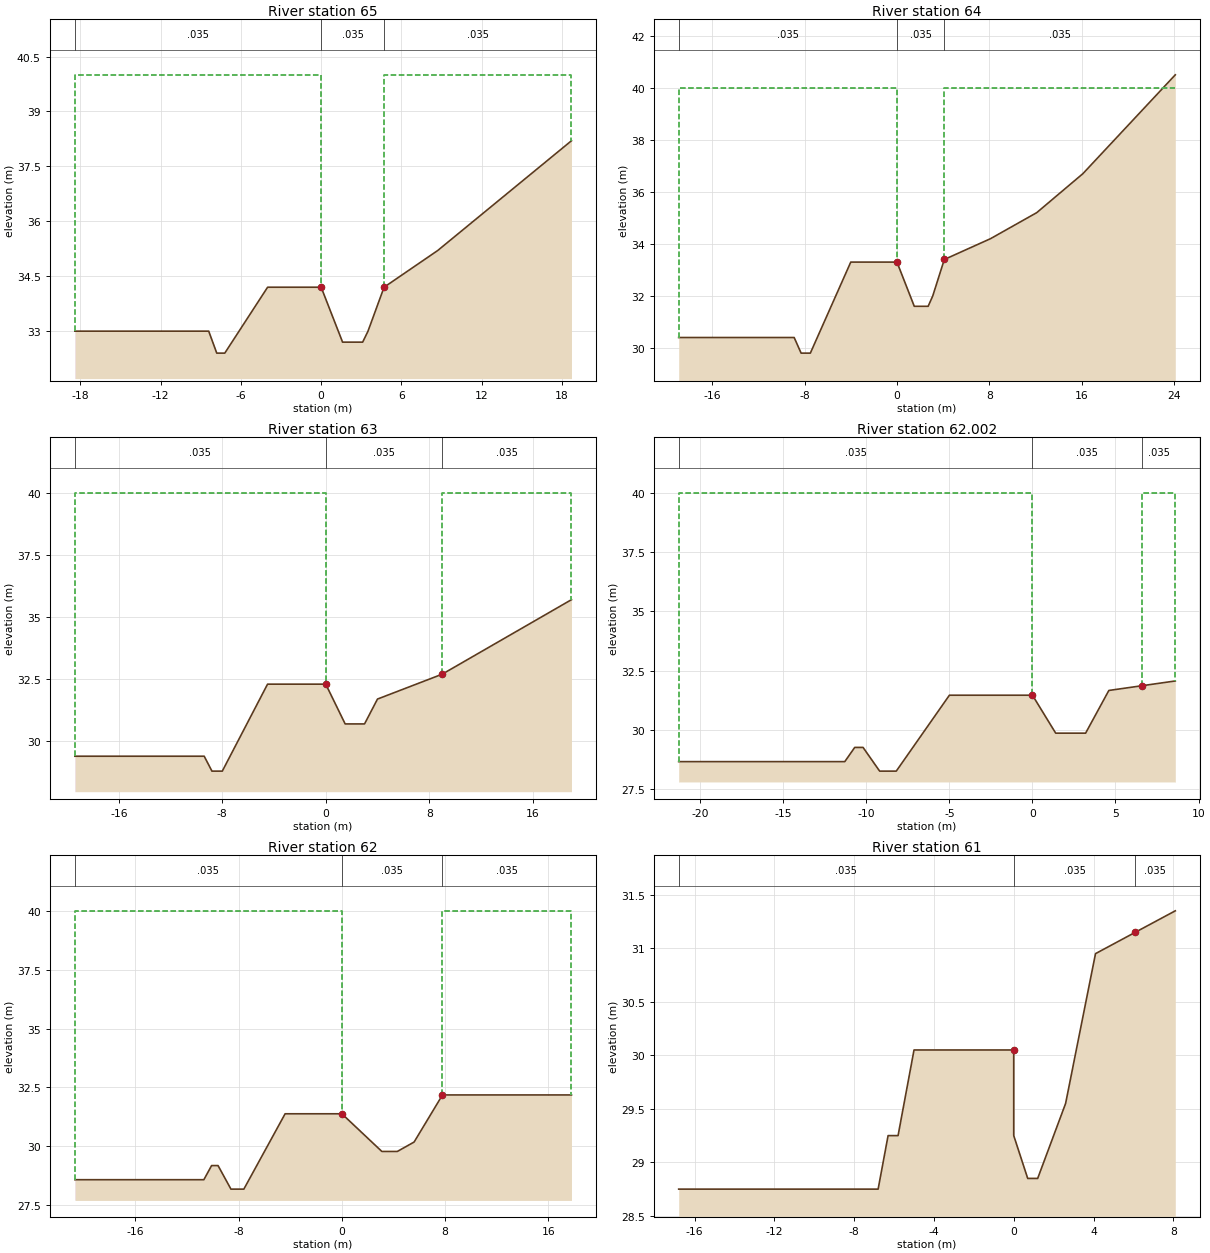
Type RM Length L Ch R = 1 ,65      ,50,50,50
#Sta/Elev= 13
   -18.4      33    -8.4      33    -7.8    32.4    -7.2    32.4      -4    34.2
       0    34.2     1.6    32.7     3.1    32.7     3.5      33     4.7    34.2
     8.7    35.2    13.7    36.7    18.7    38.2
#Mann= 3 , 0 , 0
   -18.4    .035       0       0    .035       0     4.7    .035       0
#XS Ineff= 2 , 0
               0      40     4.7              40
Permanent Ineff=
       F       F
#Block Obstruct= 2 , 0
                             4.7
Bank Sta=0,4.7
XS Rating Curve= 0
Exp/Cntr=.3,.1

Type RM Length L Ch R = 1 ,64      ,50,50,50
#Sta/Elev= 15
   -18.9    30.4    -8.9    30.4    -8.3    29.8    -7.5    29.8      -4    33.3
       0    33.3     1.5    31.6     2.7    31.6     3.1      32     4.1    33.4
     8.1    34.2    12.1    35.2    16.1    36.7    20.1    38.6    24.1    40.5
#Mann= 3 , 0 , 0
   -18.9    .035       0       0    .035       0     4.1    .035       0
#XS Ineff= 2 , 0
               0      40     4.1              40
Permanent Ineff=
       F       F
#Block Obstruct= 2 , 0
                             4.1
Bank Sta=0,4.1
XS Rating Curve= 0
Exp/Cntr=.3,.1

Type RM Length L Ch R = 1 ,63      ,48,48,48
#Sta/Elev= 13
   -19.4    29.4    -9.4    29.4    -8.8    28.8      -8    28.8    -4.5    32.3
       0    32.3     1.5    30.7       3    30.7       4    31.7       5    31.9
       9    32.7      14    34.2      19    35.7
#Mann= 3 , 0 , 0
   -19.4    .035       0       0    .035       0       9    .035       0
#XS Ineff= 2 , 0
               0      40       9              40
Permanent Ineff=
       F       F
#Block Obstruct= 2 , 0
                               9
Bank Sta=0,9
XS Rating Curve= 0
Exp/Cntr=.3,.1

Type RM Length L Ch R = 1 ,62.002  ,2,2,2
#Sta/Elev= 13
   -21.3   28.67   -11.3   28.67   -10.7   29.27   -10.2   29.27    -9.2   28.27
    -8.2   28.27      -5   31.47       0   31.47     1.4   29.87     3.2   29.87
     4.6   31.67     6.6   31.87     8.6   32.07
#Mann= 3 , 0 , 0
   -21.3    .035       0       0    .035       0     6.6    .035       0
#XS Ineff= 2 , 0
               0      40     6.6              40
Permanent Ineff=
       F       F
#Block Obstruct= 2 , 0
                             6.6
Bank Sta=0,6.6
XS Rating Curve= 0
Exp/Cntr=.3,.1

Type RM Length L Ch R = 1 ,62      ,50,50,50
#Sta/Elev= 13
   -20.7   28.58   -10.7   28.58   -10.1   29.18    -9.6   29.18    -8.6   28.18
    -7.6   28.18    -4.4   31.38       0   31.38     3.1   29.78     4.3   29.78
     5.6   30.18     7.8   32.18    17.8   32.18
#Mann= 3 , 0 , 0
   -20.7    .035       0       0    .035       0     7.8    .035       0
#XS Ineff= 2 , 0
               0      40     7.8              40
Permanent Ineff=
       F       F
#Block Obstruct= 2 , 0
                             7.8
Bank Sta=0,7.8
XS Rating Curve= 0
Exp/Cntr=.3,.1

Type RM Length L Ch R = 1 ,61      ,7,7,7
#Sta/Elev= 13
   -16.8   28.75    -6.8   28.75    -6.3   29.25    -5.8   29.25      -5   30.05
       0   30.05       0   29.25      .7   28.85     1.2   28.85     2.6   29.55
     4.1   30.95     6.1   31.15     8.1   31.35
#Mann= 3 , 0 , 0
   -16.8    .035       0       0    .035       0     6.1    .035       0
#XS Ineff= 2 , 0
               0      40     6.1              40
Permanent Ineff=
       F       F
#Block Obstruct= 2 , 0
                             6.1
Bank Sta=0,6.1
XS Rating Curve= 0
Exp/Cntr=.3,.1

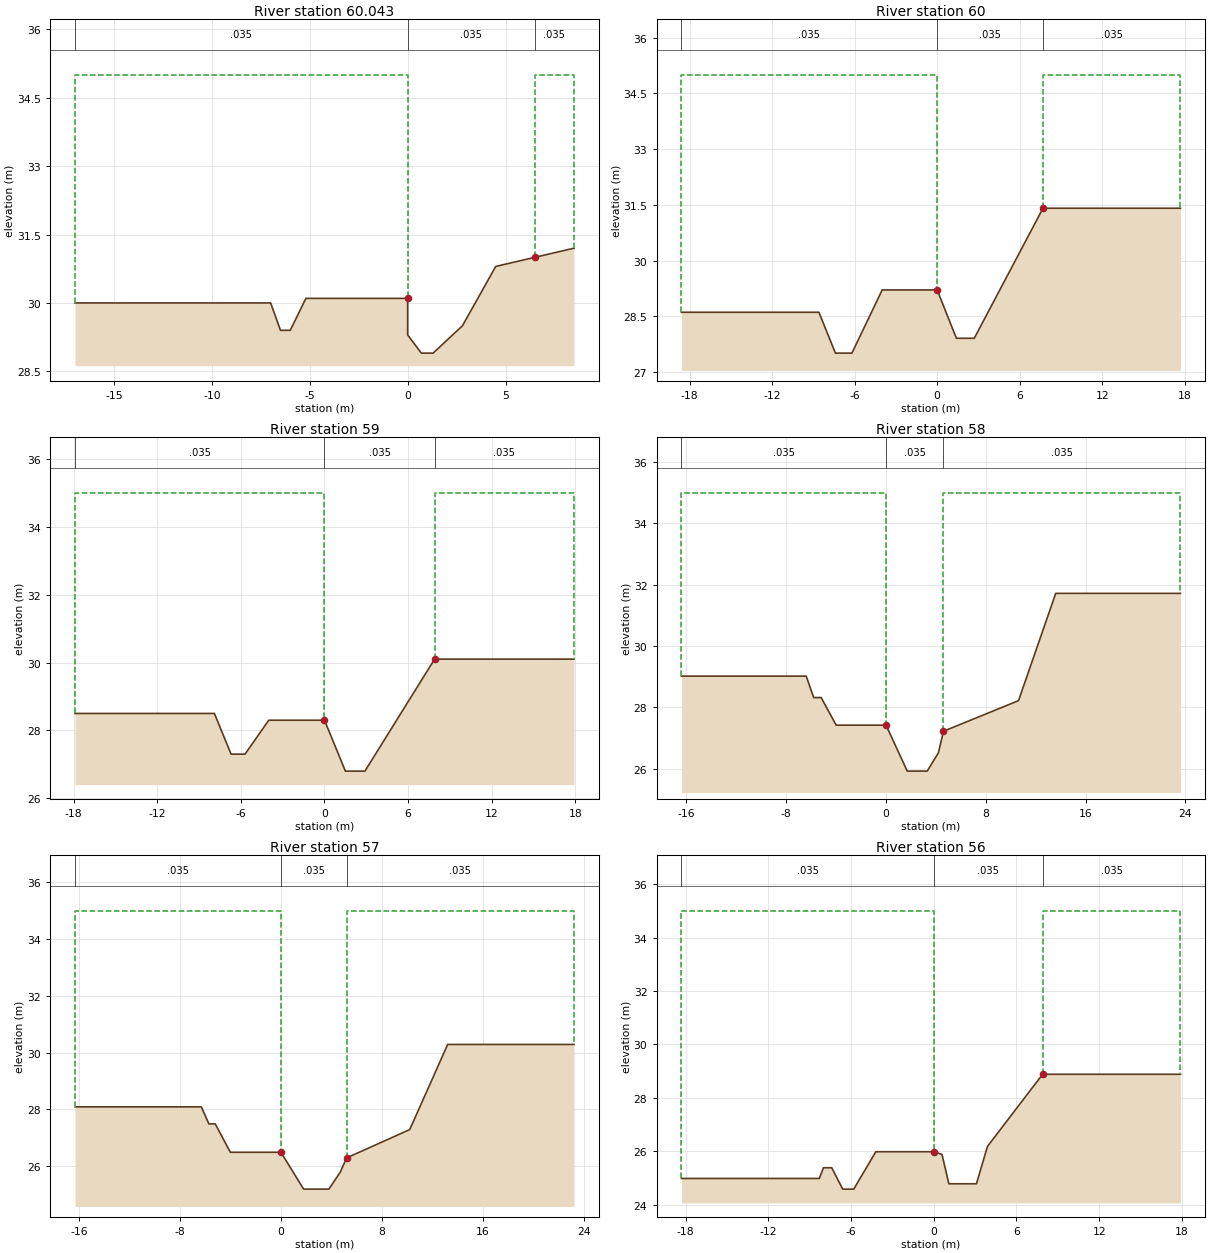
Type RM Length L Ch R = 1 ,60.043  ,43,43,43
#Sta/Elev= 13
     -17      30      -7      30    -6.5    29.4      -6    29.4    -5.2    30.1
       0    30.1       0    29.3      .7    28.9     1.3    28.9     2.8    29.5
     4.5    30.8     6.5      31     8.5    31.2
#Mann= 3 , 0 , 0
     -17    .035       0       0    .035       0     6.5    .035       0
#XS Ineff= 2 , 0
               0      35     6.5              35
Permanent Ineff=
       F       F
#Block Obstruct= 2 , 0
                             6.5
Bank Sta=0,6.5
XS Rating Curve= 0
Exp/Cntr=.3,.1

Type RM Length L Ch R = 1 ,60      ,50,50,50
#Sta/Elev= 10
   -18.6   28.61    -8.6   28.61    -7.4   27.51    -6.2   27.51      -4   29.21
       0   29.21     1.4   27.91     2.7   27.91     7.7   31.41    17.7   31.41
#Mann= 3 , 0 , 0
   -18.6    .035       0       0    .035       0     7.7    .035       0
#XS Ineff= 2 , 0
               0      35     7.7              35
Permanent Ineff=
       F       F
#Block Obstruct= 2 , 0
                             7.7
Bank Sta=0,7.7
XS Rating Curve= 0
Exp/Cntr=.3,.1

Type RM Length L Ch R = 1 ,59      ,50,50,50
#Sta/Elev= 10
   -17.9    28.5    -7.9    28.5    -6.7    27.3    -5.7    27.3      -4    28.3
       0    28.3     1.5    26.8     2.9    26.8     7.9    30.1    17.9    30.1
#Mann= 3 , 0 , 0
   -17.9    .035       0       0    .035       0     7.9    .035       0
#XS Ineff= 2 , 0
               0      35     7.9              35
Permanent Ineff=
       F       F
#Block Obstruct= 2 , 0
                             7.9
Bank Sta=0,7.9
XS Rating Curve= 0
Exp/Cntr=.3,.1

Type RM Length L Ch R = 1 ,58      ,50,50,50
#Sta/Elev= 13
   -16.4   29.02    -6.4   29.02    -5.8   28.32    -5.2   28.32      -4   27.42
       0   27.42     1.7   25.92     3.3   25.92     4.2   26.52     4.6   27.22
   10.62   28.22    13.6   31.72    23.6   31.72
#Mann= 3 , 0 , 0
   -16.4    .035       0       0    .035       0     4.6    .035       0
#XS Ineff= 2 , 0
               0      35     4.6              35
Permanent Ineff=
       F       F
#Block Obstruct= 2 , 0
                             4.6
Bank Sta=0,4.6
XS Rating Curve= 0
Exp/Cntr=.3,.1

Type RM Length L Ch R = 1 ,57      ,50,50,50
#Sta/Elev= 13
   -16.3   28.09    -6.3   28.09    -5.7   27.49    -5.2   27.49      -4   26.49
       0   26.49     1.8   25.19     3.8   25.19     4.7   25.79     5.2   26.29
    10.2   27.29    13.2   30.29    23.2   30.29
#Mann= 3 , 0 , 0
   -16.3    .035       0       0    .035       0     5.2    .035       0
#XS Ineff= 2 , 0
               0      35     5.2              35
Permanent Ineff=
       F       F
#Block Obstruct= 2 , 0
                             5.2
Bank Sta=0,5.2
XS Rating Curve= 0
Exp/Cntr=.3,.1

Type RM Length L Ch R = 1 ,56      ,22,22,22
#Sta/Elev= 14
   -18.3   24.98    -8.3   24.98      -8   25.38    -7.4   25.38    -6.6   24.58
    -5.8   24.58    -4.2   25.98       0   25.98      .6   25.88     1.1   24.78
     3.1   24.78     3.9   26.18     7.9   28.88    17.9   28.88
#Mann= 3 , 0 , 0
   -18.3    .035       0       0    .035       0     7.9    .035       0
#XS Ineff= 2 , 0
               0      35     7.9              35
Permanent Ineff=
       F       F
#Block Obstruct= 2 , 0
                             7.9
Bank Sta=0,7.9
XS Rating Curve= 0
Exp/Cntr=.3,.1

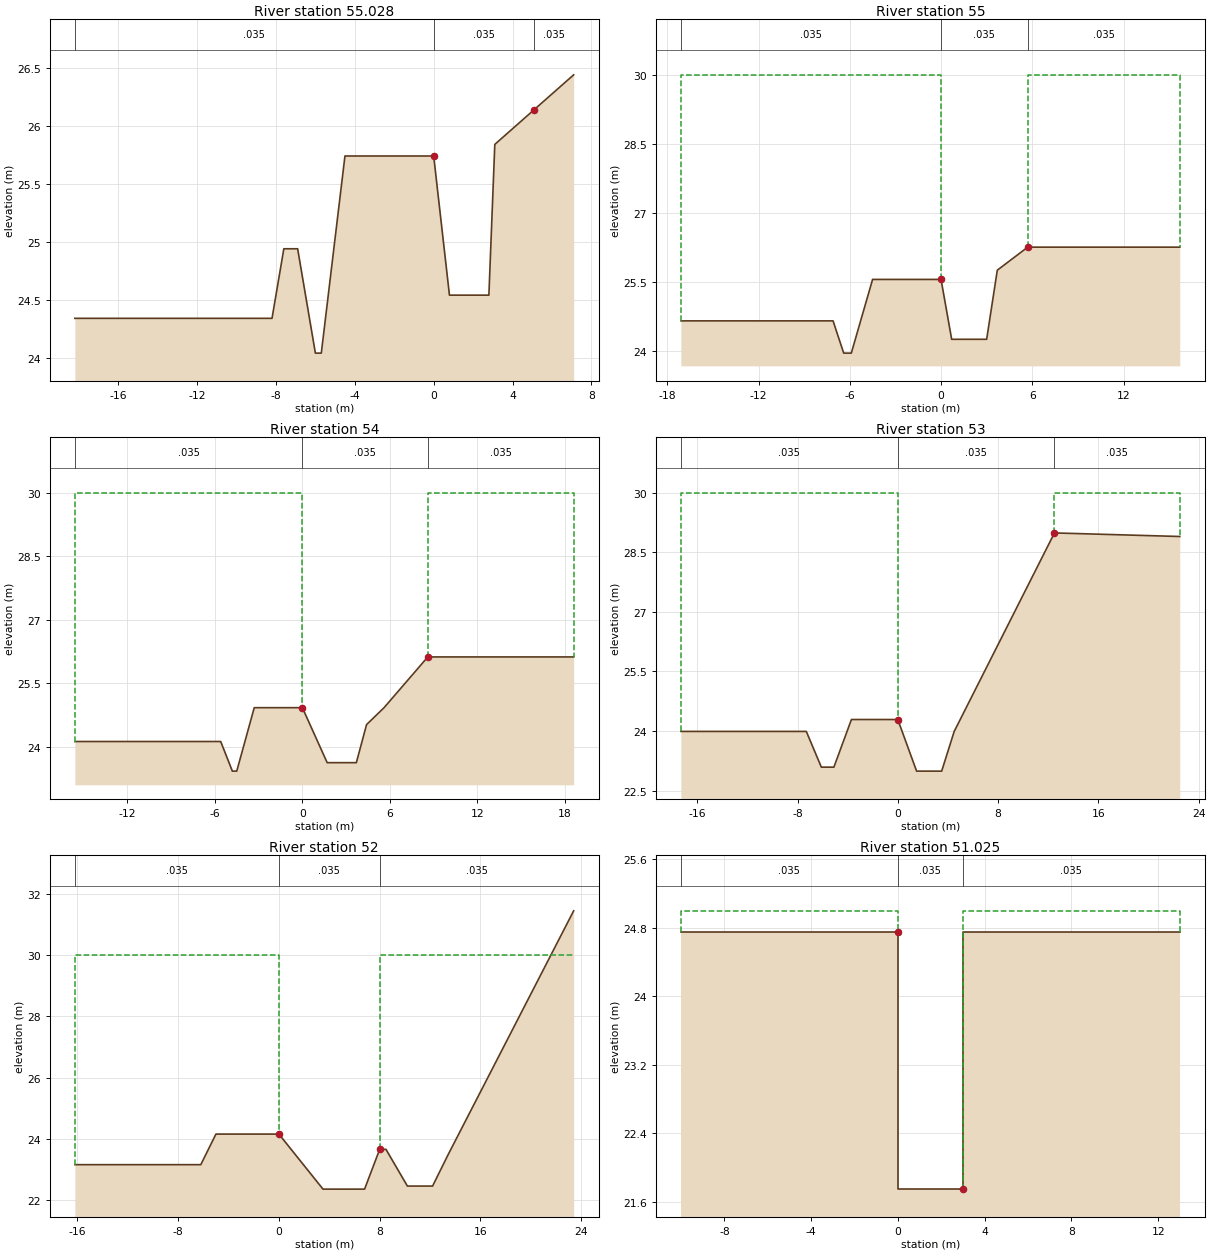
Type RM Length L Ch R = 1 ,55.028  ,28,28,28
#Sta/Elev= 13
   -18.2   24.34    -8.2   24.34    -7.6   24.94    -6.9   24.94      -6   24.04
    -5.7   24.04    -4.5   25.74       0   25.74      .8   24.54     2.8   24.54
     3.1   25.84     5.1   26.14     7.1   26.44
#Mann= 3 , 0 , 0
   -18.2    .035       0       0    .035       0     5.1    .035       0
#XS Ineff= 2 , 0
               0      35     5.1              35
Permanent Ineff=
       F       F
#Block Obstruct= 2 , 0
                             5.1
Bank Sta=0,5.1
XS Rating Curve= 0
Exp/Cntr=.3,.1

Type RM Length L Ch R = 1 ,55      ,50,50,50
#Sta/Elev= 11
   -17.1   24.66    -7.1   24.66    -6.4   23.96    -5.9   23.96    -4.5   25.56
       0   25.56      .7   24.26       3   24.26     3.7   25.76     5.7   26.26
    15.7   26.26
#Mann= 3 , 0 , 0
   -17.1    .035       0       0    .035       0     5.7    .035       0
#XS Ineff= 2 , 0
               0      30     5.7              30
Permanent Ineff=
       F       F
#Block Obstruct= 2 , 0
                             5.7
Bank Sta=0,5.7
XS Rating Curve= 0
Exp/Cntr=.3,.1

Type RM Length L Ch R = 1 ,54      ,50,50,50
#Sta/Elev= 12
   -15.6   24.12    -5.6   24.12    -4.8   23.42    -4.5   23.42    -3.3   24.92
       0   24.92     1.7   23.62     3.7   23.62     4.4   24.52     5.6   24.92
     8.6   26.12    18.6   26.12
#Mann= 3 , 0 , 0
   -15.6    .035       0       0    .035       0     8.6    .035       0
#XS Ineff= 2 , 0
               0      30     8.6              30
Permanent Ineff=
       F       F
#Block Obstruct= 2 , 0
                             8.6
Bank Sta=0,8.6
XS Rating Curve= 0
Exp/Cntr=.3,.1

Type RM Length L Ch R = 1 ,53      ,50,50,50
#Sta/Elev= 12
   -17.3   23.99    -7.3   23.99    -6.1   23.09    -5.1   23.09    -3.7   24.29
       0   24.29     1.5   22.99     3.5   22.99     4.5   23.99     8.5   26.49
    12.5   28.99    22.5    28.9
#Mann= 3 , 0 , 0
   -17.3    .035       0       0    .035       0    12.5    .035       0
#XS Ineff= 2 , 0
               0      30    12.5              30
Permanent Ineff=
       F       F
#Block Obstruct= 2 , 0
                            12.5
Bank Sta=0,12.5
XS Rating Curve= 0
Exp/Cntr=.3,.1

Type RM Length L Ch R = 1 ,52      ,25,25,25
#Sta/Elev= 13
   -16.2   23.15    -6.2   23.15      -5   24.15       0   24.15     3.5   22.35
     6.8   22.35       8   23.65     8.5   23.65    10.2   22.45    12.2   22.45
    13.4   23.45    18.4   27.45    23.4   31.45
#Mann= 3 , 0 , 0
   -16.2    .035       0       0    .035       0       8    .035       0
#XS Ineff= 2 , 0
               0      30       8              30
Permanent Ineff=
       F       F
#Block Obstruct= 2 , 0
                               8
Bank Sta=0,8
XS Rating Curve= 0
Exp/Cntr=.3,.1

Type RM Length L Ch R = 1 ,51.025  ,492,492,492
#Sta/Elev= 6
     -10   24.75       0   24.75       0   21.75       3   21.75       3   24.75
      13   24.75
#Mann= 3 , 0 , 0
     -10    .035       0       0    .035       0       3    .035       0
#XS Ineff= 2 , 0
               0      25       3              25
Permanent Ineff=
       F       F
#Block Obstruct= 2 , 0
                               3
Bank Sta=0,3
XS Rating Curve= 0
Exp/Cntr=.3,.1

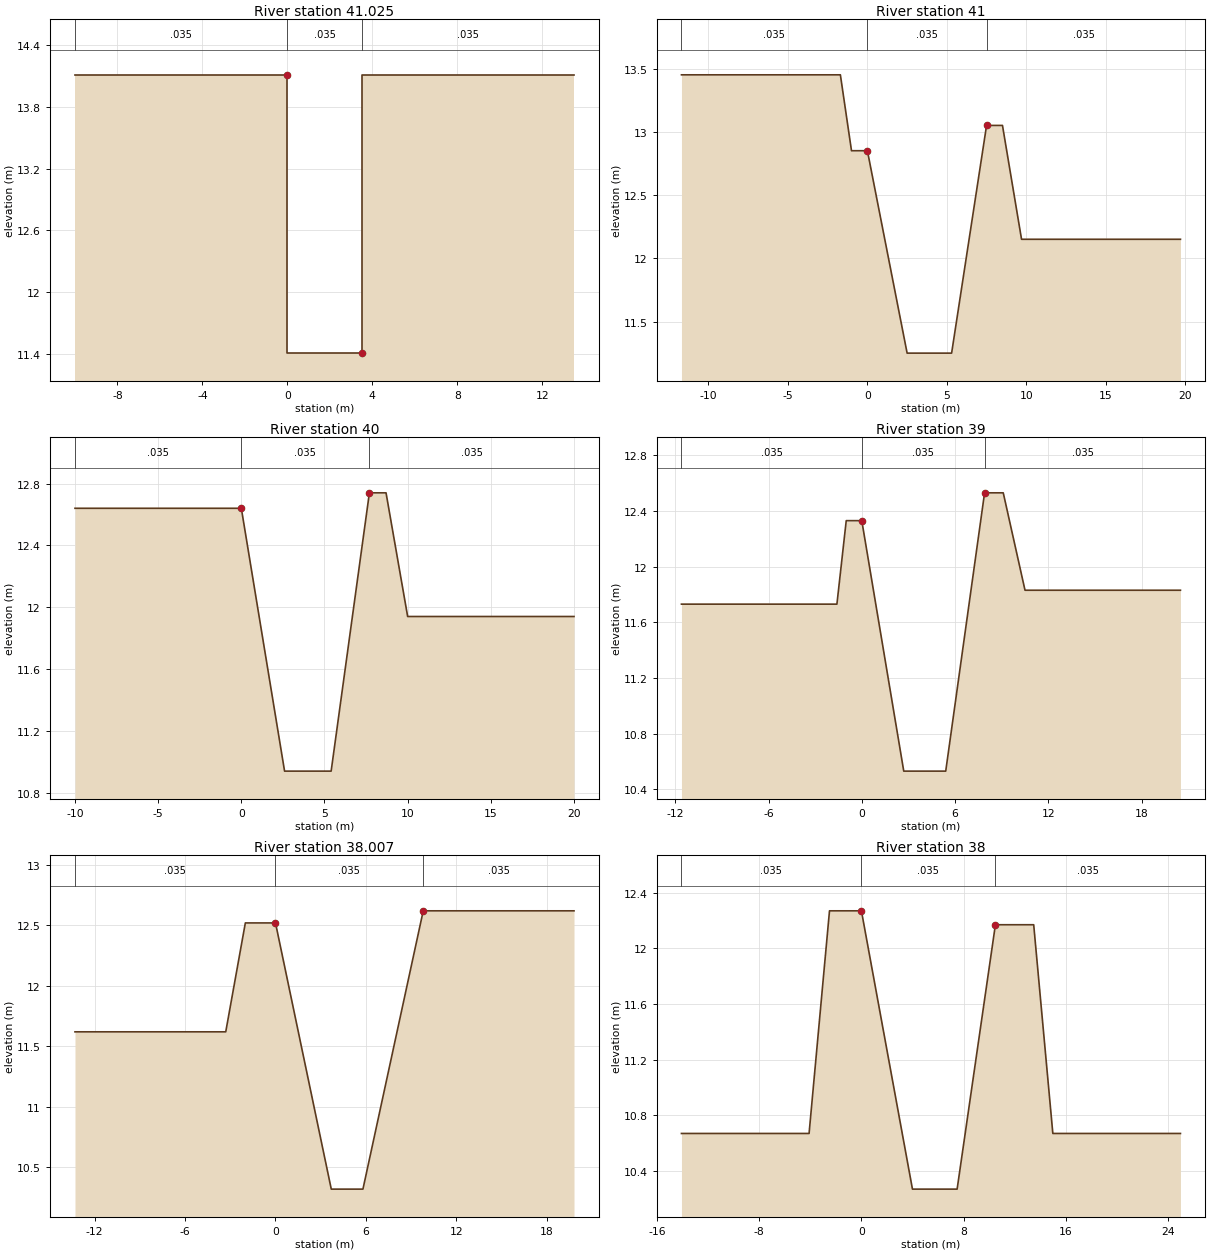
Type RM Length L Ch R = 1 ,41.025  ,25,25,25
#Sta/Elev= 6
     -10   14.11       0   14.11       0   11.41     3.5   11.41     3.5   14.11
    13.5   14.11
#Mann= 3 , 0 , 0
     -10    .035       0       0    .035       0     3.5    .035       0
#XS Ineff= 2 , 0
               0      25     3.5              25
Permanent Ineff=
       F       F
#Block Obstruct= 2 , 0
                             3.5
Bank Sta=0,3.5
XS Rating Curve= 0
Exp/Cntr=.3,.1

Type RM Length L Ch R = 1 ,41      ,50,50,50
#Sta/Elev= 10
   -11.7   13.45    -1.7   13.45      -1   12.85       0   12.85     2.5   11.25
     5.3   11.25     7.5   13.05     8.5   13.05     9.7   12.15    19.7   12.15
#Mann= 3 , 0 , 0
   -11.7    .035       0       0    .035       0     7.5    .035       0
#XS Ineff= 2 , 0
               0      25     7.5              25
Permanent Ineff=
       F       F
#Block Obstruct= 2 , 0
                             7.5
Bank Sta=0,7.5
XS Rating Curve= 0
Exp/Cntr=.3,.1

Type RM Length L Ch R = 1 ,40      ,50,50,50
#Sta/Elev= 8
     -10   12.64       0   12.64     2.6   10.94     5.4   10.94     7.7   12.74
     8.7   12.74      10   11.94      20   11.94
#Mann= 3 , 0 , 0
     -10    .035       0       0    .035       0     7.7    .035       0
#XS Ineff= 2 , 0
               0      25     7.7              25
Permanent Ineff=
       F       F
#Block Obstruct= 2 , 0
                             7.7
Bank Sta=0,7.7
XS Rating Curve= 0
Exp/Cntr=.3,.1

Type RM Length L Ch R = 1 ,39      ,43,43,43
#Sta/Elev= 10
   -11.6   11.73    -1.6   11.73      -1   12.33       0   12.33     2.7   10.53
     5.4   10.53     7.9   12.53     9.1   12.53    10.5   11.83    20.5   11.83
#Mann= 3 , 0 , 0
   -11.6    .035       0       0    .035       0     7.9    .035       0
#XS Ineff= 2 , 0
               0      25     7.9              25
Permanent Ineff=
       F       F
#Block Obstruct= 2 , 0
                             7.9
Bank Sta=0,7.9
XS Rating Curve= 0
Exp/Cntr=.3,.1

Type RM Length L Ch R = 1 ,38.007  ,7,7,7
#Sta/Elev= 8
   -13.3   11.62    -3.3   11.62      -2   12.52       0   12.52     3.7   10.32
     5.8   10.32     9.8   12.62    19.8   12.62
#Mann= 3 , 0 , 0
   -13.3    .035       0       0    .035       0     9.8    .035       0
#XS Ineff= 2 , 0
               0      25     9.8              25
Permanent Ineff=
       F       F
#Block Obstruct= 2 , 0
                             9.8
Bank Sta=0,9.8
XS Rating Curve= 0
Exp/Cntr=.3,.1

Type RM Length L Ch R = 1 ,38      ,50,50,50
#Sta/Elev= 10
   -14.1   10.67    -4.1   10.67    -2.5   12.27       0   12.27       4   10.27
     7.5   10.27    10.5   12.17    13.5   12.17      15   10.67      25   10.67
#Mann= 3 , 0 , 0
   -14.1    .035       0       0    .035       0    10.5    .035       0
#XS Ineff= 2 , 0
               0      25    10.5              25
Permanent Ineff=
       F       F
#Block Obstruct= 2 , 0
                            10.5
Bank Sta=0,10.5
XS Rating Curve= 0
Exp/Cntr=.3,.1

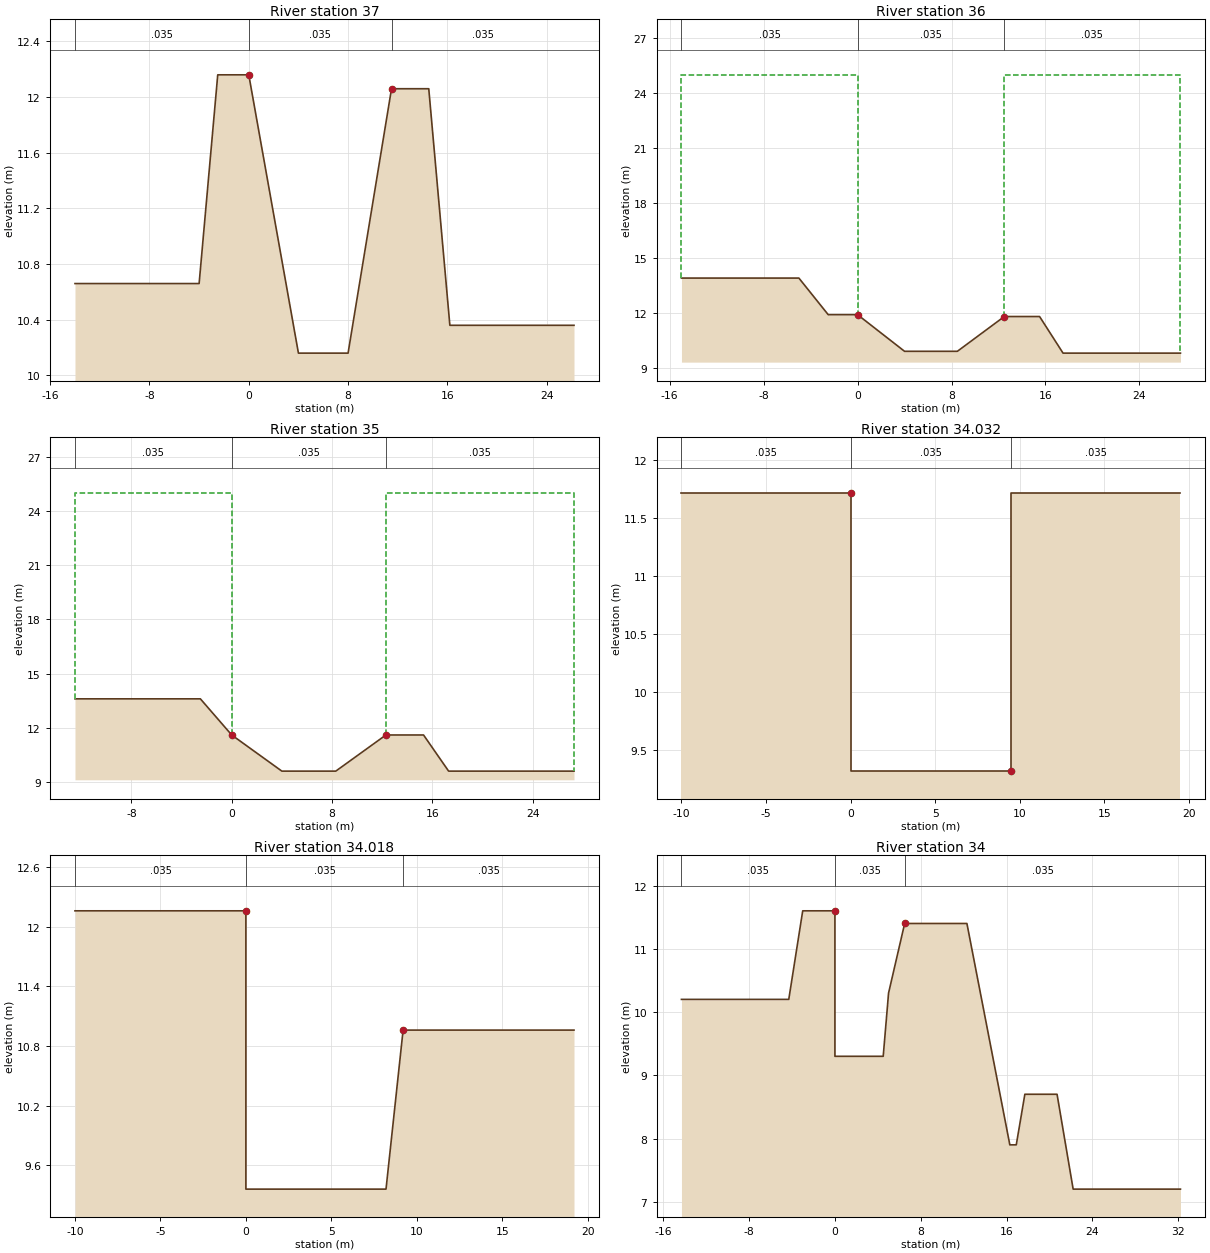
Type RM Length L Ch R = 1 ,37      ,50,50,50
#Sta/Elev= 10
     -14   10.66      -4   10.66    -2.5   12.16       0   12.16       4   10.16
       8   10.16    11.5   12.06    14.5   12.06    16.2   10.36    26.2   10.36
#Mann= 3 , 0 , 0
     -14    .035       0       0    .035       0    11.5    .035       0
#XS Ineff= 2 , 0
               0      25    11.5              25
Permanent Ineff=
       F       F
#Block Obstruct= 2 , 0
                            11.5
Bank Sta=0,11.5
XS Rating Curve= 0
Exp/Cntr=.3,.1

Type RM Length L Ch R = 1 ,36      ,50,50,50
#Sta/Elev= 10
     -15    13.9      -5    13.9    -2.5    11.9       0    11.9       4     9.9
     8.5     9.9    12.5    11.8    15.5    11.8    17.5     9.8    27.5     9.8
#Mann= 3 , 0 , 0
     -15    .035       0       0    .035       0    12.5    .035       0
#XS Ineff= 2 , 0
               0      25    12.5              25
Permanent Ineff=
       F       F
#Block Obstruct= 2 , 0
                            12.5
Bank Sta=0,12.5
XS Rating Curve= 0
Exp/Cntr=.3,.1

Type RM Length L Ch R = 1 ,35      ,18,18,18
#Sta/Elev= 9
   -12.5    13.6    -2.5    13.6       0    11.6       4     9.6     8.3     9.6
    12.3    11.6    15.3    11.6    17.3     9.6    27.3     9.6
#Mann= 3 , 0 , 0
   -12.5    .035       0       0    .035       0    12.3    .035       0
#XS Ineff= 2 , 0
               0      25    12.3              25
Permanent Ineff=
       F       F
#Block Obstruct= 2 , 0
                            12.3
Bank Sta=0,12.3
XS Rating Curve= 0
Exp/Cntr=.3,.1

Type RM Length L Ch R = 1 ,34.032  ,14,14,14
#Sta/Elev= 6
     -10   11.72       0   11.72       0    9.32     9.5    9.32     9.5   11.72
    19.5   11.72
#Mann= 3 , 0 , 0
     -10    .035       0       0    .035       0     9.5    .035       0
#XS Ineff= 2 , 0
               0      25     9.5              25
Permanent Ineff=
       F       F
#Block Obstruct= 2 , 0
                             9.5
Bank Sta=0,9.5
XS Rating Curve= 0
Exp/Cntr=.3,.1

Type RM Length L Ch R = 1 ,34.018  ,18,18,18
#Sta/Elev= 6
     -10   12.16       0   12.16       0    9.36     8.2    9.36     9.2   10.96
    19.2   10.96
#Mann= 3 , 0 , 0
     -10    .035       0       0    .035       0     9.2    .035       0
#XS Ineff= 2 , 0
               0      25     9.2              25
Permanent Ineff=
       F       F
#Block Obstruct= 2 , 0
                             9.2
Bank Sta=0,9.2
XS Rating Curve= 0
Exp/Cntr=.3,.1

Type RM Length L Ch R = 1 ,34      ,18,18,18
#Sta/Elev= 17
   -14.3    10.2    -4.3    10.2      -3    11.6       0    11.6       0     9.3
     4.5     9.3       5    10.3     6.5    11.4     8.3    11.4    11.3    11.4
    12.3    11.4    16.3     7.9    16.9     7.9    17.7     8.7    20.7     8.7
    22.2     7.2    32.2     7.2
#Mann= 3 , 0 , 0
   -14.3    .035       0       0    .035       0     6.5    .035       0
#XS Ineff= 2 , 0
               0      25     6.5              25
Permanent Ineff=
       F       F
#Block Obstruct= 2 , 0
                             6.5
Bank Sta=0,6.5
XS Rating Curve= 0
Exp/Cntr=.3,.1

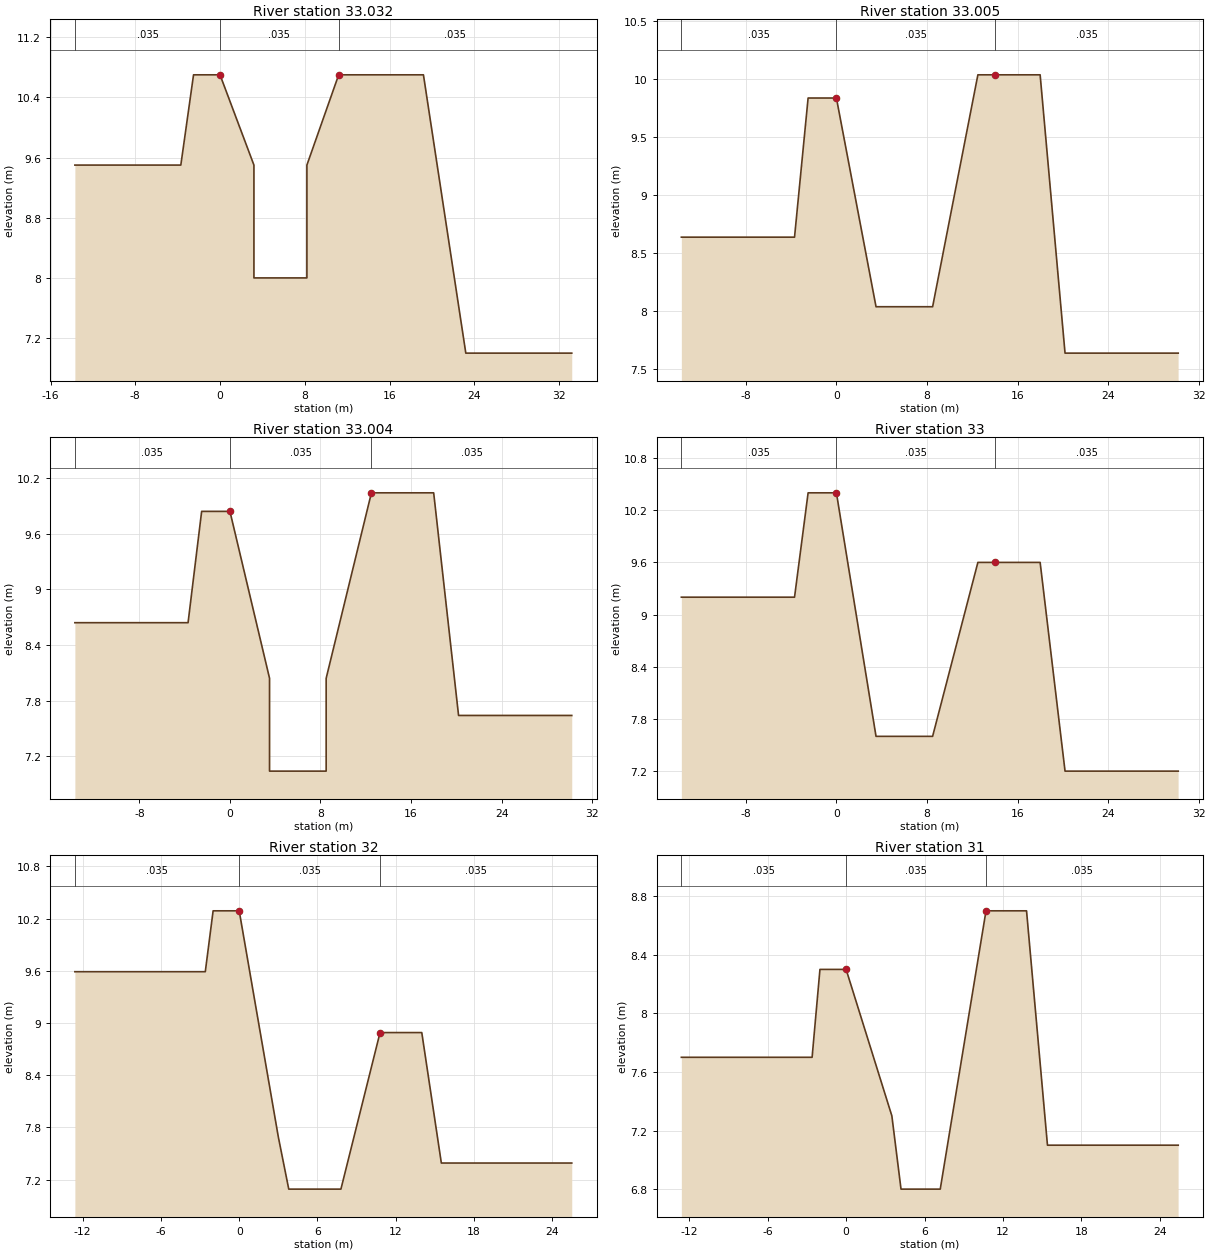
Type RM Length L Ch R = 1 ,33.032  ,27,27,27
#Sta/Elev= 14
   -13.7     9.5    -3.7     9.5    -2.5    10.7       0    10.7     3.2     9.5
     3.2       8     8.2       8     8.2     9.5    11.2    10.7    12.2    10.7
    15.2    10.7    19.2    10.7    23.2       7    33.2       7
#Mann= 3 , 0 , 0
   -13.7    .035       0       0    .035       0    11.2    .035       0
#XS Ineff= 2 , 0
               0      25    11.2              25
Permanent Ineff=
       F       F
#Block Obstruct= 2 , 0
                            11.2
Bank Sta=0,11.2
XS Rating Curve= 0
Exp/Cntr=.3,.1

Type RM Length L Ch R = 1 ,33.005  ,1,1,1
#Sta/Elev= 12
   -13.7    8.64    -3.7    8.64    -2.5    9.84       0    9.84     3.5    8.04
     8.5    8.04    12.5   10.04      14   10.04      17   10.04      18   10.04
    20.2    7.64    30.2    7.64
#Mann= 3 , 0 , 0
   -13.7    .035       0       0    .035       0      14    .035       0
#XS Ineff= 2 , 0
               0      25      14              25
Permanent Ineff=
       F       F
#Block Obstruct= 2 , 0
                              14
Bank Sta=0,14
XS Rating Curve= 0
Exp/Cntr=.3,.1

Type RM Length L Ch R = 1 ,33.004  ,4,4,4
#Sta/Elev= 15
   -13.7    8.64   -12.5    8.64    -3.7    8.64    -2.5    9.84       0    9.84
     3.5    8.04     3.5    7.04     8.5    7.04     8.5    8.04    12.5   10.04
      14   10.04      17   10.04      18   10.04    20.2    7.64    30.2    7.64
#Mann= 3 , 0 , 0
   -13.7    .035       0       0    .035       0    12.5    .035       0
#XS Ineff= 2 , 0
               0      25    12.5              25
Permanent Ineff=
       F       F
#Block Obstruct= 2 , 0
                            12.5
Bank Sta=0,12.5
XS Rating Curve= 0
Exp/Cntr=.3,.1

Type RM Length L Ch R = 1 ,33      ,50,50,50
#Sta/Elev= 12
   -13.7     9.2    -3.7     9.2    -2.5    10.4       0    10.4     3.5     7.6
     8.5     7.6    12.5     9.6      14     9.6      17     9.6      18     9.6
    20.2     7.2    30.2     7.2
#Mann= 3 , 0 , 0
   -13.7    .035       0       0    .035       0      14    .035       0
#XS Ineff= 2 , 0
               0      25      14              25
Permanent Ineff=
       F       F
#Block Obstruct= 2 , 0
                              14
Bank Sta=0,14
XS Rating Curve= 0
Exp/Cntr=.3,.1

Type RM Length L Ch R = 1 ,32      ,50,50,50
#Sta/Elev= 11
   -12.6    9.59    -2.6    9.59      -2   10.29       0   10.29       3    7.69
     3.8    7.09     7.8    7.09    10.8    8.89      14    8.89    15.5    7.39
    25.5    7.39
#Mann= 3 , 0 , 0
   -12.6    .035       0       0    .035       0    10.8    .035       0
#XS Ineff= 2 , 0
               0      25    10.8              25
Permanent Ineff=
       F       F
#Block Obstruct= 2 , 0
                            10.8
Bank Sta=0,10.8
XS Rating Curve= 0
Exp/Cntr=.3,.1

Type RM Length L Ch R = 1 ,31      ,50,50,50
#Sta/Elev= 11
   -12.6     7.7    -2.6     7.7      -2     8.3       0     8.3     3.5     7.3
     4.2     6.8     7.2     6.8    10.7     8.7    13.8     8.7    15.4     7.1
    25.4     7.1
#Mann= 3 , 0 , 0
   -12.6    .035       0       0    .035       0    10.7    .035       0
#XS Ineff= 2 , 0
               0      25    10.7              25
Permanent Ineff=
       F       F
#Block Obstruct= 2 , 0
                            10.7
Bank Sta=0,10.7
XS Rating Curve= 0
Exp/Cntr=.3,.1