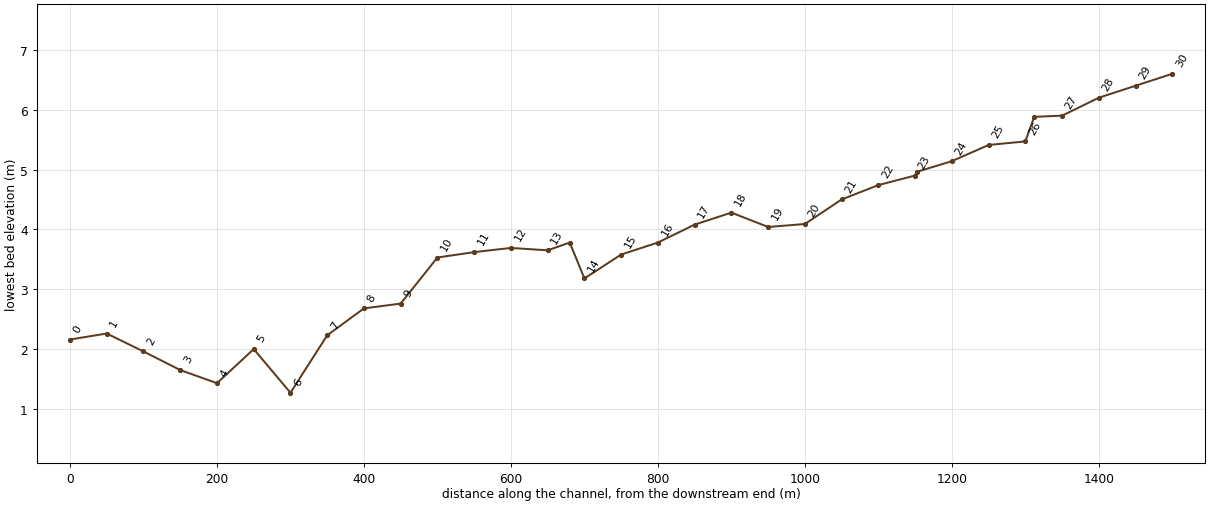
HEC-RAS study sukok.prj: sukok

--- sukok.g01 (geometry) --- (continued)

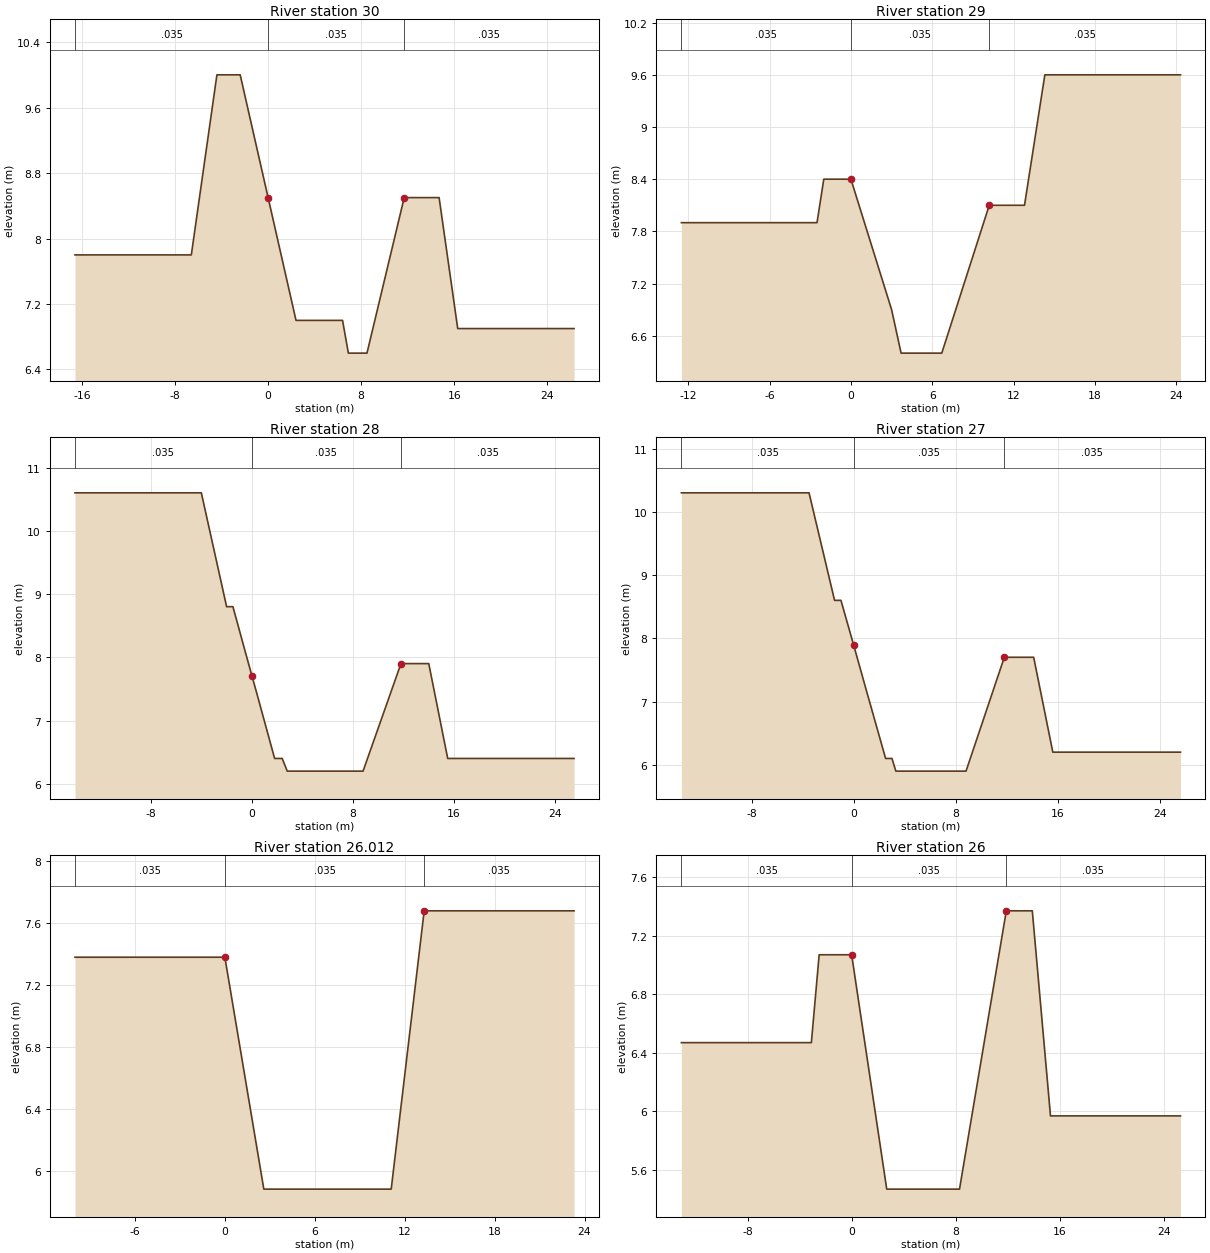
Type RM Length L Ch R = 1 ,30      ,50,50,50
#Sta/Elev= 13
   -16.6     7.8    -6.6     7.8    -4.4      10    -2.4      10       0     8.5
     2.4       7     6.4       7     6.9     6.6     8.5     6.6    11.7     8.5
    14.7     8.5    16.3     6.9    26.3     6.9
#Mann= 3 , 0 , 0
   -16.6    .035       0       0    .035       0    11.7    .035       0
#XS Ineff= 2 , 0
               0      25    11.7              25
Permanent Ineff=
       F       F
#Block Obstruct= 2 , 0
                            11.7
Bank Sta=0,11.7
XS Rating Curve= 0
Exp/Cntr=.3,.1

Type RM Length L Ch R = 1 ,29      ,50,50,50
#Sta/Elev= 11
   -12.5     7.9    -2.5     7.9      -2     8.4       0     8.4       3     6.9
     3.7     6.4     6.7     6.4    10.2     8.1    12.8     8.1    14.3     9.6
    24.3     9.6
#Mann= 3 , 0 , 0
   -12.5    .035       0       0    .035       0    10.2    .035       0
#XS Ineff= 2 , 0
               0      25    10.2              25
Permanent Ineff=
       F       F
#Block Obstruct= 2 , 0
                            10.2
Bank Sta=0,10.2
XS Rating Curve= 0
Exp/Cntr=.3,.1

Type RM Length L Ch R = 1 ,28      ,50,50,50
#Sta/Elev= 15
     -14    10.6      -4    10.6      -2     8.8    -1.5     8.8     -.5    8.07
       0    7.71      .5    7.35     1.8     6.4     2.4     6.4     2.8     6.2
     8.8     6.2    11.8     7.9      14     7.9    15.5     6.4    25.5     6.4
#Mann= 3 , 0 , 0
     -14    .035       0       0    .035       0    11.8    .035       0
#XS Ineff= 2 , 0
               0      25    11.8              25
Permanent Ineff=
       F       F
#Block Obstruct= 2 , 0
                            11.8
Bank Sta=0,11.8
XS Rating Curve= 0
Exp/Cntr=.3,.1

Type RM Length L Ch R = 1 ,27      ,38,38,38
#Sta/Elev= 14
   -13.5    10.3    -3.5    10.3    -1.5     8.6      -1     8.6       0    7.89
       1    7.17     2.5     6.1       3     6.1     3.3     5.9     8.8     5.9
    11.8     7.7    14.1     7.7    15.6     6.2    25.6     6.2
#Mann= 3 , 0 , 0
   -13.5    .035       0       0    .035       0    11.8    .035       0
#XS Ineff= 2 , 0
               0      25    11.8              25
Permanent Ineff=
       F       F
#Block Obstruct= 2 , 0
                            11.8
Bank Sta=0,11.8
XS Rating Curve= 0
Exp/Cntr=.3,.1

Type RM Length L Ch R = 1 ,26.012  ,12,12,12
#Sta/Elev= 6
     -10    7.38       0    7.38     2.6    5.88    11.1    5.88    13.3    7.68
    23.3    7.68
#Mann= 3 , 0 , 0
     -10    .035       0       0    .035       0    13.3    .035       0
#XS Ineff= 2 , 0
               0      25    13.3              25
Permanent Ineff=
       F       F
#Block Obstruct= 2 , 0
                            13.3
Bank Sta=0,13.3
XS Rating Curve= 0
Exp/Cntr=.3,.1

Type RM Length L Ch R = 1 ,26      ,50,50,50
#Sta/Elev= 10
   -13.1    6.47    -3.1    6.47    -2.5    7.07       0    7.07     2.7    5.47
     8.3    5.47    11.9    7.37    13.9    7.37    15.3    5.97    25.3    5.97
#Mann= 3 , 0 , 0
   -13.1    .035       0       0    .035       0    11.9    .035       0
#XS Ineff= 2 , 0
               0      25    11.9              25
Permanent Ineff=
       F       F
#Block Obstruct= 2 , 0
                            11.9
Bank Sta=0,11.9
XS Rating Curve= 0
Exp/Cntr=.3,.1

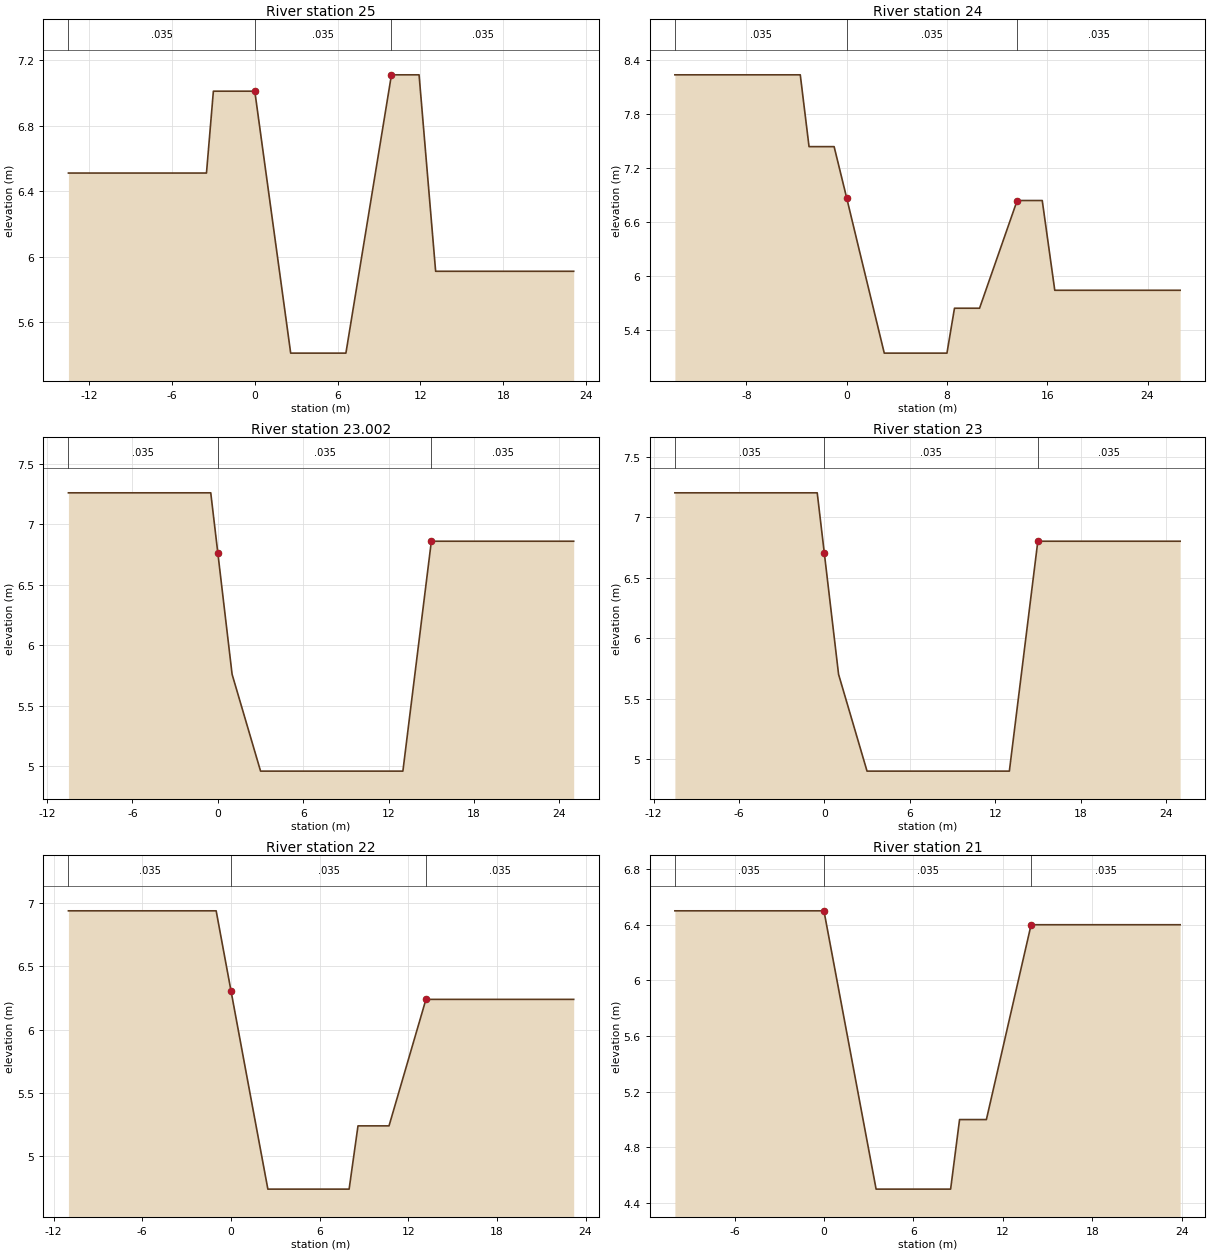
Type RM Length L Ch R = 1 ,25      ,50,50,50
#Sta/Elev= 10
   -13.5    6.51    -3.5    6.51      -3    7.01       0    7.01     2.6    5.41
     6.6    5.41     9.9    7.11    11.9    7.11    13.1    5.91    23.1    5.91
#Mann= 3 , 0 , 0
   -13.5    .035       0       0    .035       0     9.9    .035       0
#XS Ineff= 2 , 0
               0      25     9.9              25
Permanent Ineff=
       F       F
#Block Obstruct= 2 , 0
                             9.9
Bank Sta=0,9.9
XS Rating Curve= 0
Exp/Cntr=.3,.1

Type RM Length L Ch R = 1 ,24      ,48,48,48
#Sta/Elev= 14
   -13.7    8.24    -3.7    8.24      -3    7.44      -1    7.44       0    6.87
       1    6.29       3    5.14       8    5.14     8.6    5.64    10.6    5.64
    13.6    6.84    15.6    6.84    16.6    5.84    26.6    5.84
#Mann= 3 , 0 , 0
   -13.7    .035       0       0    .035       0    13.6    .035       0
#XS Ineff= 2 , 0
               0      25    13.6              25
Permanent Ineff=
       F       F
#Block Obstruct= 2 , 0
                            13.6
Bank Sta=0,13.6
XS Rating Curve= 0
Exp/Cntr=.3,.1

Type RM Length L Ch R = 1 ,23.002  ,2,2,2
#Sta/Elev= 8
   -10.5    7.26     -.5    7.26       0    6.76       1    5.76       3    4.96
      13    4.96      15    6.86      25    6.86
#Mann= 3 , 0 , 0
   -10.5    .035       0       0    .035       0      15    .035       0
#XS Ineff= 2 , 0
               0      25      15              25
Permanent Ineff=
       F       F
#Block Obstruct= 2 , 0
                              15
Bank Sta=0,15
XS Rating Curve= 0
Exp/Cntr=.3,.1

Type RM Length L Ch R = 1 ,23      ,50,50,50
#Sta/Elev= 8
   -10.5     7.2     -.5     7.2       0     6.7       1     5.7       3     4.9
      13     4.9      15     6.8      25     6.8
#Mann= 3 , 0 , 0
   -10.5    .035       0       0    .035       0      15    .035       0
#XS Ineff= 2 , 0
               0      25      15              25
Permanent Ineff=
       F       F
#Block Obstruct= 2 , 0
                              15
Bank Sta=0,15
XS Rating Curve= 0
Exp/Cntr=.3,.1

Type RM Length L Ch R = 1 ,22      ,50,50,50
#Sta/Elev= 10
     -11    6.94      -1    6.94       0    6.31       1    5.68     2.5    4.74
       8    4.74     8.6    5.24    10.7    5.24    13.2    6.24    23.2    6.24
#Mann= 3 , 0 , 0
     -11    .035       0       0    .035       0    13.2    .035       0
#XS Ineff= 2 , 0
               0      25    13.2              25
Permanent Ineff=
       F       F
#Block Obstruct= 2 , 0
                            13.2
Bank Sta=0,13.2
XS Rating Curve= 0
Exp/Cntr=.3,.1

Type RM Length L Ch R = 1 ,21      ,50,50,50
#Sta/Elev= 8
     -10     6.5       0     6.5     3.5     4.5     8.5     4.5     9.1       5
    10.9       5    13.9     6.4    23.9     6.4
#Mann= 3 , 0 , 0
     -10    .035       0       0    .035       0    13.9    .035       0
#XS Ineff= 2 , 0
               0      25    13.9              25
Permanent Ineff=
       F       F
#Block Obstruct= 2 , 0
                            13.9
Bank Sta=0,13.9
XS Rating Curve= 0
Exp/Cntr=.3,.1

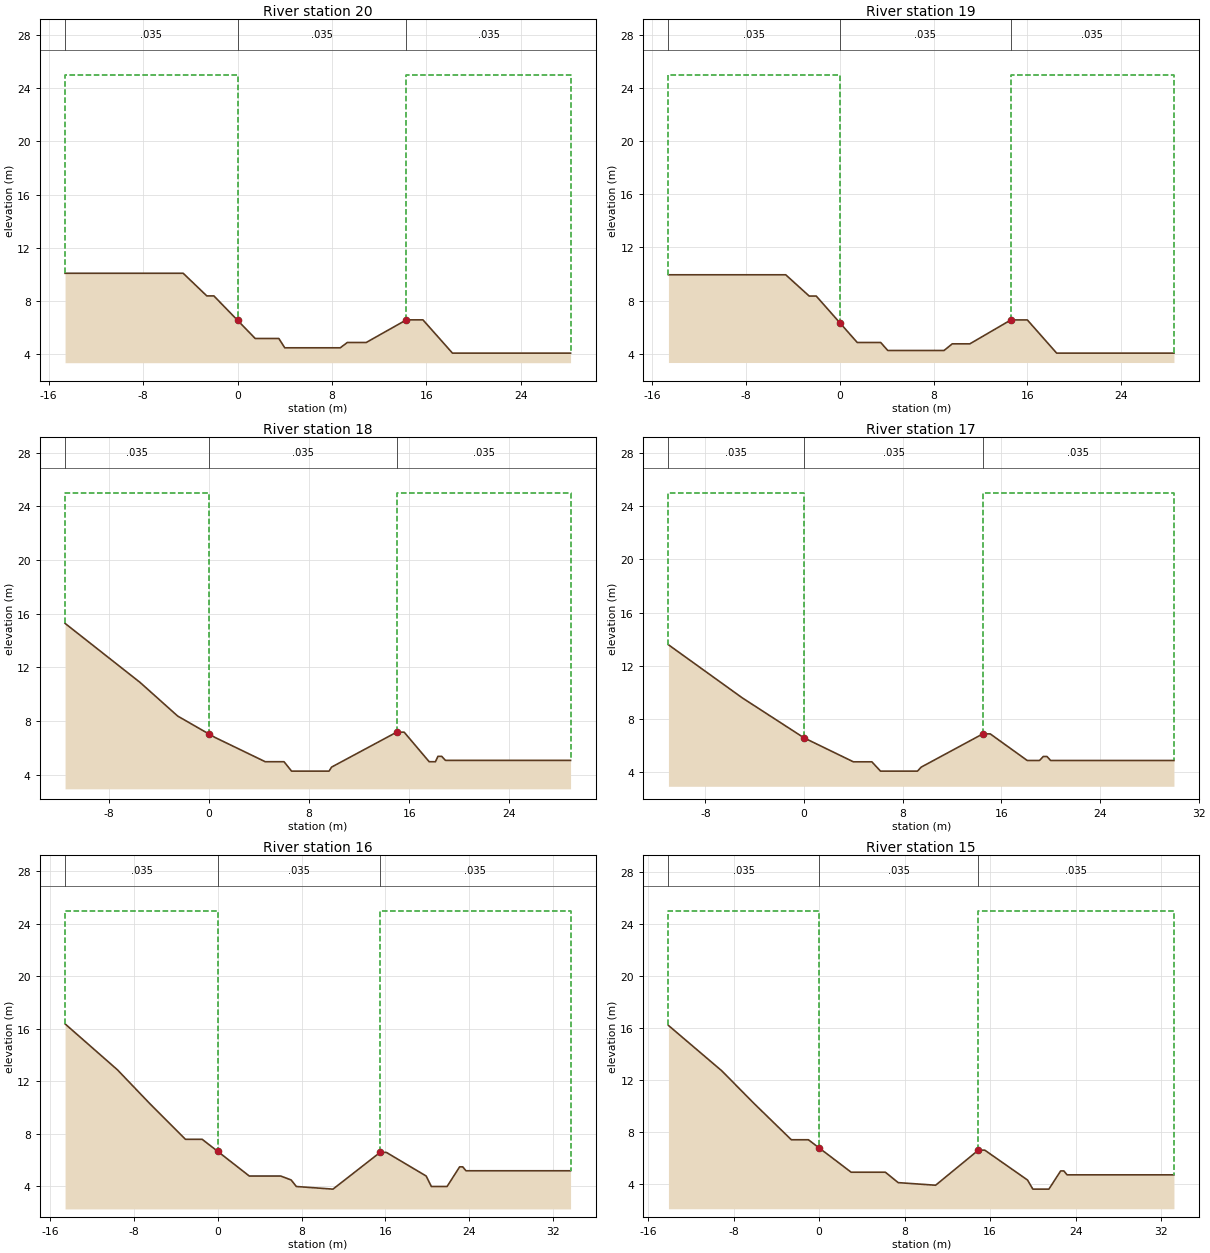
Type RM Length L Ch R = 1 ,20      ,50,50,50
#Sta/Elev= 15
   -14.6   10.09    -4.6   10.09    -2.6    8.39      -2    8.39       0    6.56
     1.5    5.19     3.5    5.19       4    4.49     8.7    4.49     9.3    4.89
    10.9    4.89    14.3    6.59    15.7    6.59    18.2    4.09    28.2    4.09
#Mann= 3 , 0 , 0
   -14.6    .035       0       0    .035       0    14.3    .035       0
#XS Ineff= 2 , 0
               0      25    14.3              25
Permanent Ineff=
       F       F
#Block Obstruct= 2 , 0
                            14.3
Bank Sta=0,14.3
XS Rating Curve= 0
Exp/Cntr=.3,.1

Type RM Length L Ch R = 1 ,19      ,50,50,50
#Sta/Elev= 16
   -14.6    9.94    -4.6    9.94    -2.6    8.34      -2    8.34       0    6.34
       1    5.34     1.5    4.84     3.5    4.84     4.1    4.24     8.9    4.24
     9.6    4.74    11.1    4.74    14.6    6.54      16    6.54    18.5    4.04
    28.5    4.04
#Mann= 3 , 0 , 0
   -14.6    .035       0       0    .035       0    14.6    .035       0
#XS Ineff= 2 , 0
               0      25    14.6              25
Permanent Ineff=
       F       F
#Block Obstruct= 2 , 0
                            14.6
Bank Sta=0,14.6
XS Rating Curve= 0
Exp/Cntr=.3,.1

Type RM Length L Ch R = 1 ,18      ,50,50,50
#Sta/Elev= 20
   -11.5   15.28    -8.5   13.08    -5.5   10.88    -2.5    8.38     -.5    7.31
       0    7.05      .5    6.78     4.5    4.98       6    4.98     6.6    4.28
     9.6    4.28     9.8    4.58      15    7.18    15.6    7.18    17.6    4.98
    18.1    4.98    18.3    5.38    18.6    5.38    18.9    5.08    28.9    5.08
#Mann= 3 , 0 , 0
   -11.5    .035       0       0    .035       0      15    .035       0
#XS Ineff= 2 , 0
               0      25      15              25
Permanent Ineff=
       F       F
#Block Obstruct= 2 , 0
                              15
Bank Sta=0,15
XS Rating Curve= 0
Exp/Cntr=.3,.1

Type RM Length L Ch R = 1 ,17      ,50,50,50
#Sta/Elev= 17
     -11   13.58      -8   11.58      -5    9.58       0    6.58       4    4.78
     5.5    4.78     6.2    4.08     9.2    4.08     9.5    4.38    14.5    6.88
    15.1    6.88    18.1    4.88    19.1    4.88    19.4    5.18    19.7    5.18
      20    4.88      30    4.88
#Mann= 3 , 0 , 0
     -11    .035       0       0    .035       0    14.5    .035       0
#XS Ineff= 2 , 0
               0      25    14.5              25
Permanent Ineff=
       F       F
#Block Obstruct= 2 , 0
                            14.5
Bank Sta=0,14.5
XS Rating Curve= 0
Exp/Cntr=.3,.1

Type RM Length L Ch R = 1 ,16      ,50,50,50
#Sta/Elev= 20
   -14.6   16.38    -9.6   12.88    -6.6   10.38    -3.1    7.58    -1.5    7.58
       0    6.65       3    4.78       6    4.78       7    4.48     7.5    3.98
      11    3.78    15.5    6.58    16.1    6.58    19.9    4.78    20.4    3.98
    21.9    3.98    23.1    5.48    23.4    5.48    23.7    5.18    33.7    5.18
#Mann= 3 , 0 , 0
   -14.6    .035       0       0    .035       0    15.5    .035       0
#XS Ineff= 2 , 0
               0      25    15.5              25
Permanent Ineff=
       F       F
#Block Obstruct= 2 , 0
                            15.5
Bank Sta=0,15.5
XS Rating Curve= 0
Exp/Cntr=.3,.1

Type RM Length L Ch R = 1 ,15      ,50,50,50
#Sta/Elev= 20
   -14.1   16.18    -9.1   12.68    -6.1   10.18    -2.6    7.38      -1    7.38
       0    6.75       1    6.13       3    4.88     6.2    4.88     7.4    4.08
    10.9    3.88    14.9    6.58    15.5    6.58    19.5    4.28      20    3.58
    21.5    3.58    22.6    4.98    22.9    4.98    23.2    4.68    33.2    4.68
#Mann= 3 , 0 , 0
   -14.1    .035       0       0    .035       0    14.9    .035       0
#XS Ineff= 2 , 0
               0      25    14.9              25
Permanent Ineff=
       F       F
#Block Obstruct= 2 , 0
                            14.9
Bank Sta=0,14.9
XS Rating Curve= 0
Exp/Cntr=.3,.1

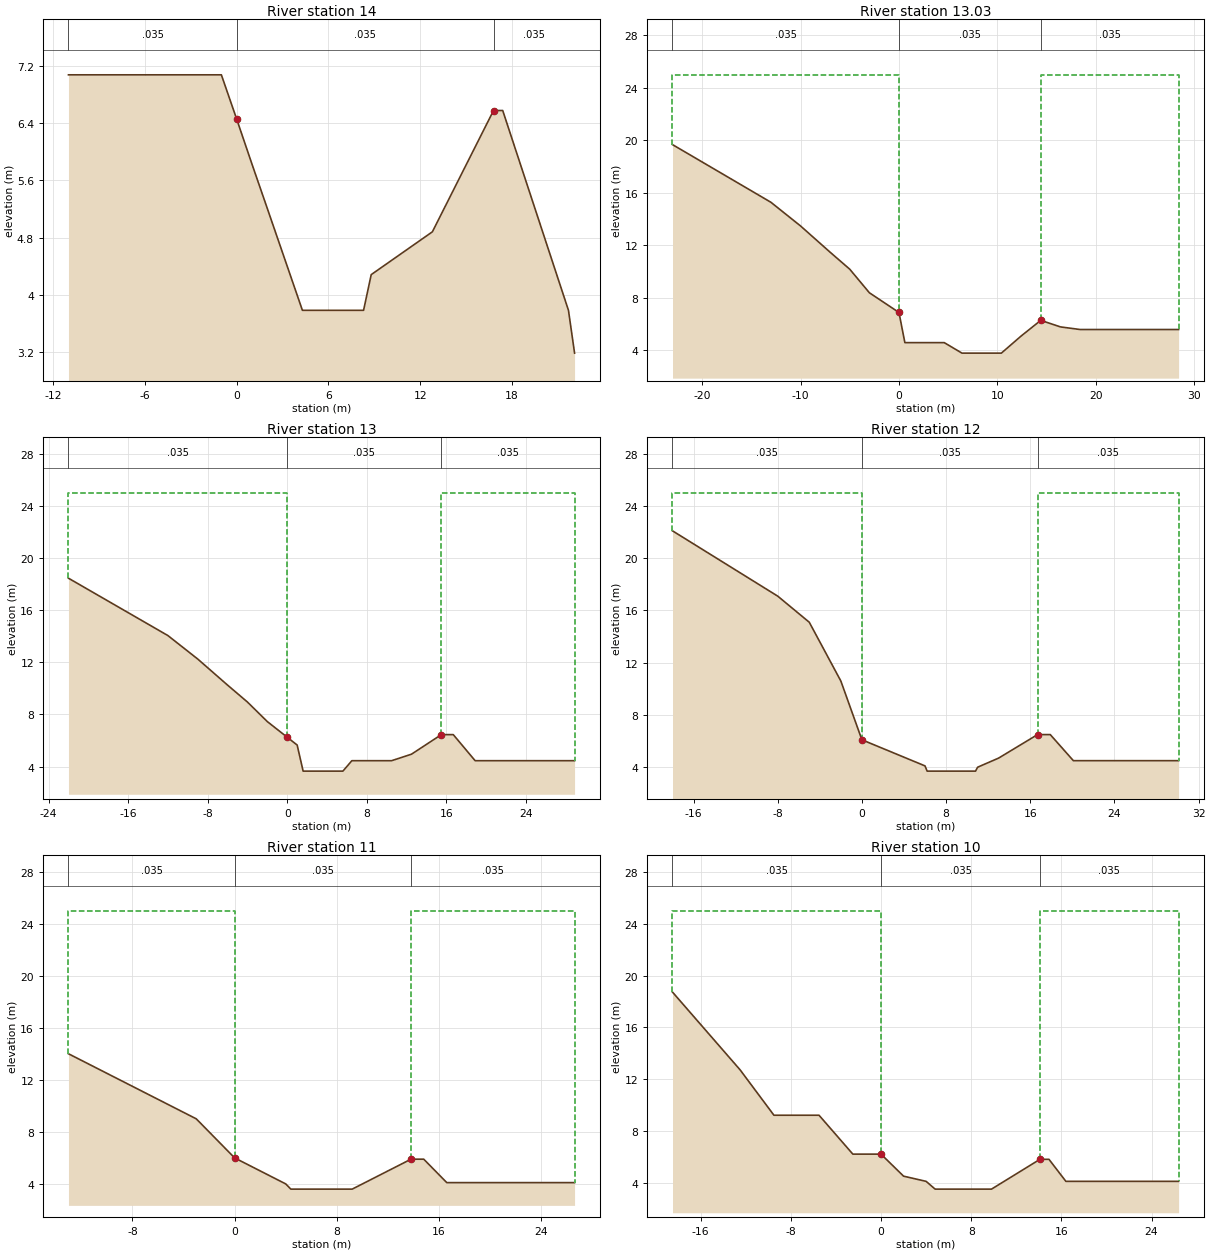
Type RM Length L Ch R = 1 ,14      ,20,20,20
#Sta/Elev= 13
     -11    7.08      -1    7.08       0    6.46       1    5.83       2    5.21
     4.3    3.78     8.3    3.78     8.8    4.28    12.8    4.88    16.8    6.58
    17.4    6.58    21.7    3.78    22.1    3.18
#Mann= 3 , 0 , 0
     -11    .035       0       0    .035       0    16.8    .035       0
#XS Ineff= 2 , 0
               0      25    16.8              25
Permanent Ineff=
       F       F
#Block Obstruct= 2 , 0
                            16.8
Bank Sta=0,16.8
XS Rating Curve= 0
Exp/Cntr=.3,.1

Type RM Length L Ch R = 1 ,13.03   ,30,30,30
#Sta/Elev= 17
     -23   19.68     -18   17.48     -13   15.28     -10   13.48      -7   11.48
      -5   10.18      -3    8.38       0    6.88      .6    4.58     4.6    4.58
     6.4    3.78    10.4    3.78    12.4    5.08    14.4    6.28    16.4    5.78
    18.4    5.58    28.4    5.58
#Mann= 3 , 0 , 0
     -23    .035       0       0    .035       0    14.4    .035       0
#XS Ineff= 2 , 0
               0      25    14.4              25
Permanent Ineff=
       F       F
#Block Obstruct= 2 , 0
                            14.4
Bank Sta=0,14.4
XS Rating Curve= 0
Exp/Cntr=.3,.1

Type RM Length L Ch R = 1 ,13      ,50,50,50
#Sta/Elev= 18
     -22   18.45     -17   16.25     -12   14.05      -9   12.25      -6   10.25
      -4    8.95      -2    7.45       0    6.25       1    5.65     1.6    3.65
     5.6    3.65     6.5    4.45    10.5    4.45    12.5    4.95    15.5    6.45
    16.7    6.45    18.9    4.45    28.9    4.45
#Mann= 3 , 0 , 0
     -22    .035       0       0    .035       0    15.5    .035       0
#XS Ineff= 2 , 0
               0      25    15.5              25
Permanent Ineff=
       F       F
#Block Obstruct= 2 , 0
                            15.5
Bank Sta=0,15.5
XS Rating Curve= 0
Exp/Cntr=.3,.1

Type RM Length L Ch R = 1 ,12      ,50,50,50
#Sta/Elev= 15
     -18   22.09     -13   19.59      -8   17.09      -5   15.09      -2   10.59
       0    6.09       6    4.09     6.2    3.69    10.8    3.69      11    3.99
      13    4.69    16.7    6.49    17.9    6.49    20.1    4.49    30.1    4.49
#Mann= 3 , 0 , 0
     -18    .035       0       0    .035       0    16.7    .035       0
#XS Ineff= 2 , 0
               0      25    16.7              25
Permanent Ineff=
       F       F
#Block Obstruct= 2 , 0
                            16.7
Bank Sta=0,16.7
XS Rating Curve= 0
Exp/Cntr=.3,.1

Type RM Length L Ch R = 1 ,11      ,50,50,50
#Sta/Elev= 11
     -13   14.02      -8   11.52      -3    9.02       0    6.02       4    4.02
     4.4    3.62     9.2    3.62    13.8    5.92    14.8    5.92    16.6    4.12
    26.6    4.12
#Mann= 3 , 0 , 0
     -13    .035       0       0    .035       0    13.8    .035       0
#XS Ineff= 2 , 0
               0      25    13.8              25
Permanent Ineff=
       F       F
#Block Obstruct= 2 , 0
                            13.8
Bank Sta=0,13.8
XS Rating Curve= 0
Exp/Cntr=.3,.1

Type RM Length L Ch R = 1 ,10      ,50,50,50
#Sta/Elev= 15
   -18.5   18.73   -15.5   15.73   -12.5   12.73    -9.5    9.23    -5.5    9.23
    -2.5    6.23       0    6.23       2    4.53       4    4.13     4.8    3.53
     9.8    3.53    14.1    5.83    14.9    5.83    16.4    4.13    26.4    4.13
#Mann= 3 , 0 , 0
   -18.5    .035       0       0    .035       0    14.1    .035       0
#XS Ineff= 2 , 0
               0      25    14.1              25
Permanent Ineff=
       F       F
#Block Obstruct= 2 , 0
                            14.1
Bank Sta=0,14.1
XS Rating Curve= 0
Exp/Cntr=.3,.1

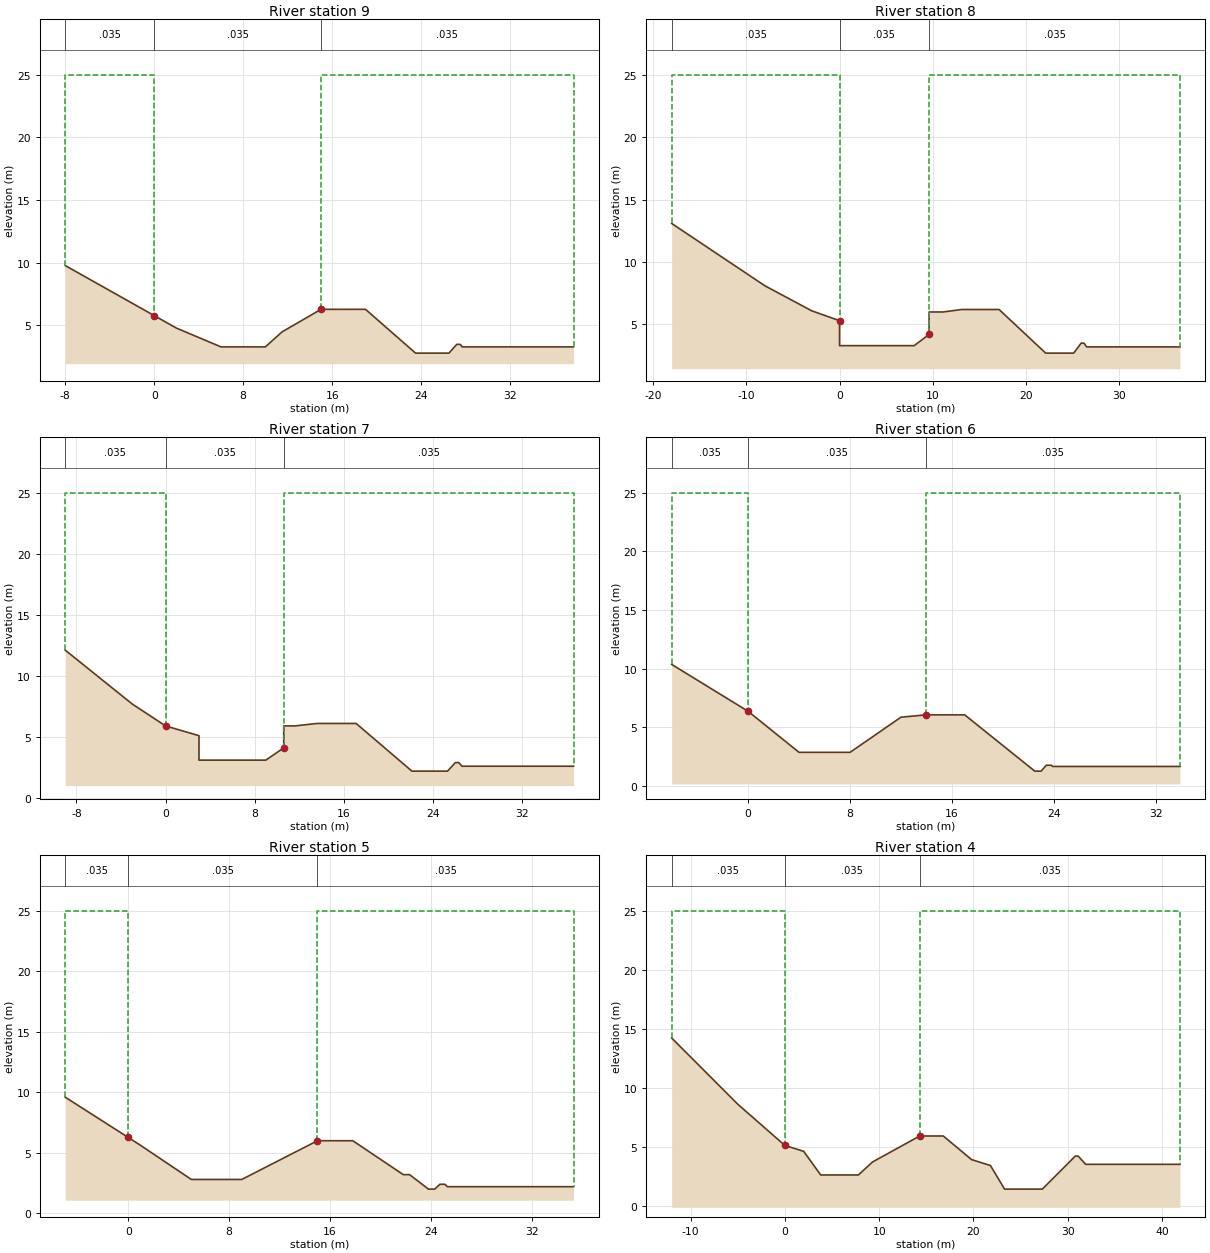
Type RM Length L Ch R = 1 ,9       ,50,50,50
#Sta/Elev= 15
      -8    9.76      -3    7.26       0    5.76       2    4.76       6    3.26
      10    3.26    11.5    4.46      15    6.26      19    6.26    23.5    2.76
    26.5    2.76    27.2    3.46    27.5    3.46    27.7    3.26    37.7    3.26
#Mann= 3 , 0 , 0
      -8    .035       0       0    .035       0      15    .035       0
#XS Ineff= 2 , 0
               0      25      15              25
Permanent Ineff=
       F       F
#Block Obstruct= 2 , 0
                              15
Bank Sta=0,15
XS Rating Curve= 0
Exp/Cntr=.3,.1

Type RM Length L Ch R = 1 ,8       ,50,50,50
#Sta/Elev= 18
     -18   13.08     -13   10.58      -8    8.08      -3    6.08       0    5.28
       0    3.28       8    3.28     9.6    4.18     9.6    5.98    11.1    5.98
    13.1    6.18    17.1    6.18    22.1    2.68    25.1    2.68    25.9    3.48
    26.2    3.48    26.5    3.18    36.5    3.18
#Mann= 3 , 0 , 0
     -18    .035       0       0    .035       0     9.6    .035       0
#XS Ineff= 2 , 0
               0      25     9.6              25
Permanent Ineff=
       F       F
#Block Obstruct= 2 , 0
                             9.6
Bank Sta=0,9.6
XS Rating Curve= 0
Exp/Cntr=.3,.1

Type RM Length L Ch R = 1 ,7       ,50,50,50
#Sta/Elev= 18
      -9   12.13      -6    9.93      -3    7.73       0    5.93       3    5.13
       3    3.13       9    3.13    10.6    4.13    10.6    5.93    11.6    5.93
    13.6    6.13    17.1    6.13    22.1    2.23    25.3    2.23      26    2.93
    26.3    2.93    26.6    2.63    36.6    2.63
#Mann= 3 , 0 , 0
      -9    .035       0       0    .035       0    10.6    .035       0
#XS Ineff= 2 , 0
               0      25    10.6              25
Permanent Ineff=
       F       F
#Block Obstruct= 2 , 0
                            10.6
Bank Sta=0,10.6
XS Rating Curve= 0
Exp/Cntr=.3,.1

Type RM Length L Ch R = 1 ,6       ,50,50,50
#Sta/Elev= 14
      -6   10.37      -3    8.37       0    6.37       4    2.87       8    2.87
      12    5.87      14    6.07      17    6.07    22.5    1.27      23    1.27
    23.4    1.77    23.8    1.77    23.9    1.67    33.9    1.67
#Mann= 3 , 0 , 0
      -6    .035       0       0    .035       0      14    .035       0
#XS Ineff= 2 , 0
               0      25      14              25
Permanent Ineff=
       F       F
#Block Obstruct= 2 , 0
                              14
Bank Sta=0,14
XS Rating Curve= 0
Exp/Cntr=.3,.1

Type RM Length L Ch R = 1 ,5       ,50,50,50
#Sta/Elev= 16
      -5     9.6      -2     7.6       0    6.27       1     5.6       5     2.8
       9     2.8      15       6    17.8       6    21.8     3.2    22.3     3.2
    23.8       2    24.3       2    24.7     2.4    25.1     2.4    25.3     2.2
    35.3     2.2
#Mann= 3 , 0 , 0
      -5    .035       0       0    .035       0      15    .035       0
#XS Ineff= 2 , 0
               0      25      15              25
Permanent Ineff=
       F       F
#Block Obstruct= 2 , 0
                              15
Bank Sta=0,15
XS Rating Curve= 0
Exp/Cntr=.3,.1

Type RM Length L Ch R = 1 ,4       ,50,50,50
#Sta/Elev= 18
     -12   14.23    -8.5   11.43      -5    8.63       0    5.13       2    4.63
     3.8    2.63     7.8    2.63     9.3    3.73    14.3    5.93    16.8    5.93
    19.8    3.93    21.8    3.43    23.3    1.43    27.3    1.43    30.8    4.23
    31.1    4.23    31.9    3.53    41.9    3.53
#Mann= 3 , 0 , 0
     -12    .035       0       0    .035       0    14.3    .035       0
#XS Ineff= 2 , 0
               0      25    14.3              25
Permanent Ineff=
       F       F
#Block Obstruct= 2 , 0
                            14.3
Bank Sta=0,14.3
XS Rating Curve= 0
Exp/Cntr=.3,.1

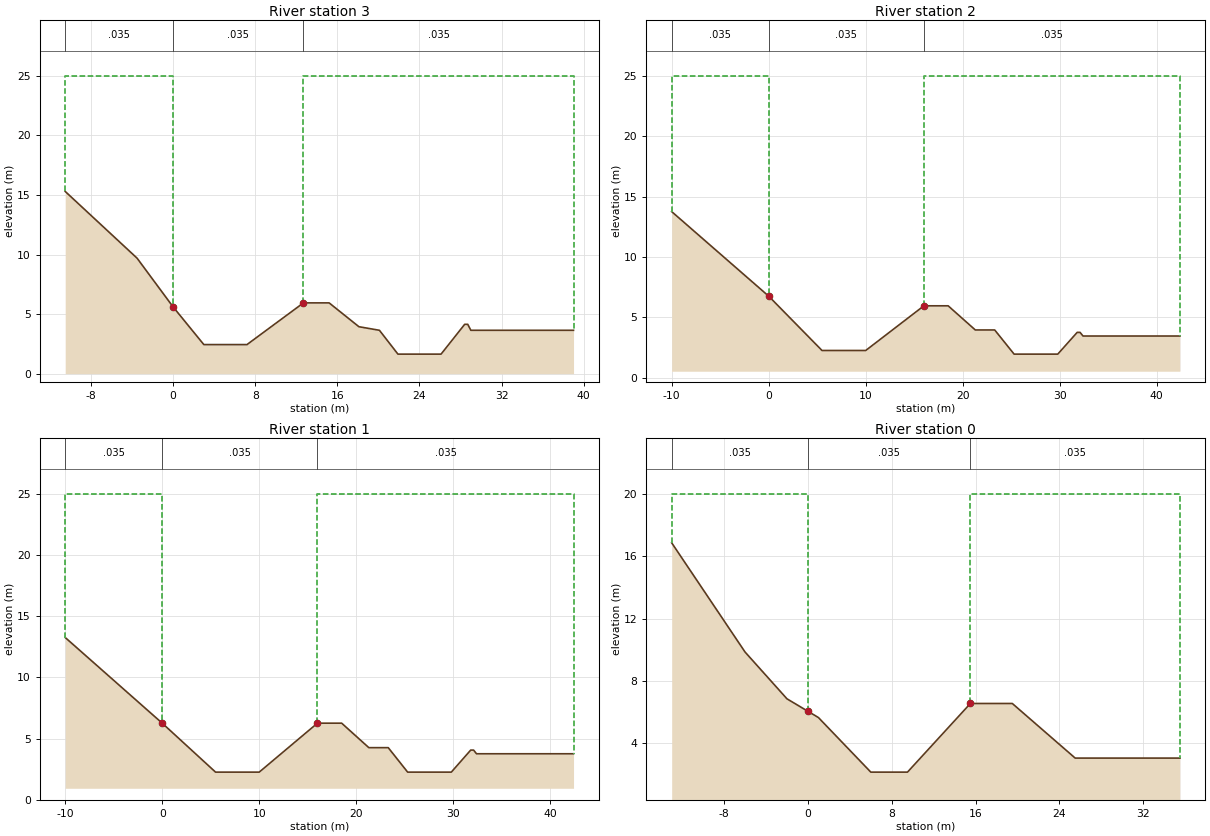
Type RM Length L Ch R = 1 ,3       ,50,50,50
#Sta/Elev= 17
   -10.5    15.3      -7    12.5    -3.5     9.7      -2    7.95       0    5.62
       3    2.45     7.2    2.45    12.7    5.95    15.2    5.95    18.1    3.95
    20.1    3.65    21.9    1.65    26.1    1.65    28.4    4.15    28.7    4.15
      29    3.65      39    3.65
#Mann= 3 , 0 , 0
   -10.5    .035       0       0    .035       0    12.7    .035       0
#XS Ineff= 2 , 0
               0      25    12.7              25
Permanent Ineff=
       F       F
#Block Obstruct= 2 , 0
                            12.7
Bank Sta=0,12.7
XS Rating Curve= 0
Exp/Cntr=.3,.1

Type RM Length L Ch R = 1 ,2       ,50,50,50
#Sta/Elev= 15
     -10   13.76      -5   10.26       0    6.76     5.5    2.26      10    2.26
      16    5.96    18.5    5.96    21.3    3.96    23.3    3.96    25.3    1.96
    29.8    1.96    31.8    3.76    32.1    3.76    32.4    3.46    42.4    3.46
#Mann= 3 , 0 , 0
     -10    .035       0       0    .035       0      16    .035       0
#XS Ineff= 2 , 0
               0      25      16              25
Permanent Ineff=
       F       F
#Block Obstruct= 2 , 0
                              16
Bank Sta=0,16
XS Rating Curve= 0
Exp/Cntr=.3,.1

Type RM Length L Ch R = 1 ,1       ,50,50,50
#Sta/Elev= 15
     -10   13.26      -5    9.76       0    6.26     5.5    2.26      10    2.26
      16    6.26    18.5    6.26    21.3    4.26    23.3    4.26    25.3    2.26
    29.8    2.26    31.8    4.06    32.1    4.06    32.4    3.76    42.4    3.76
#Mann= 3 , 0 , 0
     -10    .035       0       0    .035       0      16    .035       0
#XS Ineff= 2 , 0
               0      25      16              25
Permanent Ineff=
       F       F
#Block Obstruct= 2 , 0
                              16
Bank Sta=0,16
XS Rating Curve= 0
Exp/Cntr=.3,.1

Type RM Length L Ch R = 1 ,0       ,0,0,0
#Sta/Elev= 12
     -13   16.86    -9.5   13.36      -6    9.86      -2    6.86       0    6.06
       1    5.66       6    2.16     9.5    2.16    15.5    6.56    19.5    6.56
    25.5    3.06    35.5    3.06
#Mann= 3 , 0 , 0
     -13    .035       0       0    .035       0    15.5    .035       0
#XS Ineff= 2 , 0
               0      20    15.5              20
Permanent Ineff=
       F       F
#Block Obstruct= 2 , 0
                            15.5
Bank Sta=0,15.5
XS Rating Curve= 0
Exp/Cntr=.3,.1

Chan Stop Cuts=-1