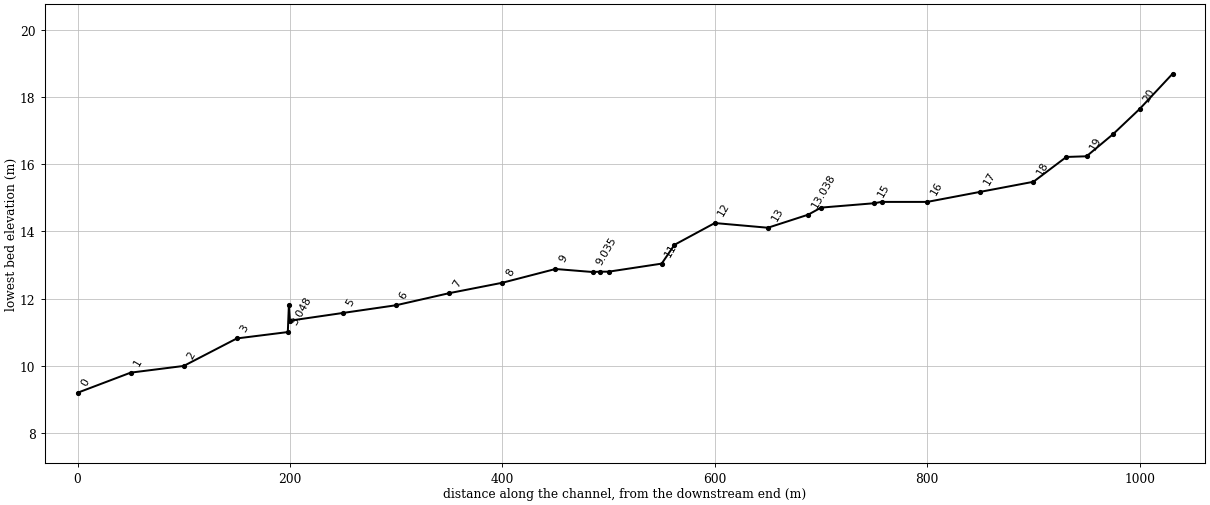
--- degung-ch.prj (project) ---

Proj Title=degung-ch
Current Plan=p01
Default Exp/Contr=.3,.1
SI Units
Geom File=g01
Flow File=f01
Plan File=p01
Y Axis Title=Elevation
X Axis Title(PF)=Main Channel Distance
X Axis Title(XS)=Station
BEGIN DESCRIPTION:
           BACK WATER COMPUTATION
      APPLICATION OF HEC-2 BY Samju Construction Engineering
      degung-ch: 10,20,30,50,80 yr
END DESCRIPTION:
DSS Export Rating Curves= 0
DSS Export Rating Curve Sorted= 0
DSS Export Volume Flow Curves= 0
DXF OffsetX= 0
DXF OffsetY= 0
DXF ScaleX= 1
DXF ScaleY= 10

--- degung-ch.p01 (plan) ---

Plan Title=Imported Plan 01
Version=Version 3.0.1  Mar 2001
Short Identifier=Imported Pla
Geom File=g01
Flow File=f01
Subcritical Flow
K Sum by GR= 0
Std Step Tol= 0.003
Critical Tol= 0.003
Num of Std Step Trials= 20
Max Error Tol= 0.1
Flow Tol Ratio= 0.001
Split Flow NTrial= 30
Split Flow Tol= 0.02
Split Flow Ratio= 0.02
Log Output Level= 0
Friction Slope Method= 1
Unsteady Friction Slope Method= 2
Parabolic Critical Depth
Global Vel Dist= 0 , 0 , 0
Global Log Level= 0
CheckData=True
Encroach Param=-1 ,0,0, 0
Computation Interval=1HOUR
Output Interval=1HOUR
Run HTab= 0
Run UNet= 0
Run PostProcess= 0
UNET Theta= 1
UNET ZTol= 0.02
UNET ZSATol= 0.1
UNET MxIter= 20
UNET MaxInSteps= 20
UNET DtIC= 0
UNET DtMin= 0
UNET MaxCRTS= 20
UNET WFStab= 2
UNET SFStab= 1
UNET WFX= 1
UNET SFX= 1
UNET Convert EG Bridges=-1
UNET Use Existing IB Tables=-1
Instantaneous Interval=1HOUR
Write IC File= 0
Write Velocity= 0
Write Detailed= 0

--- degung-ch.f01 (steady flow) ---

Flow Title=Imported Flow 01
Version=Version 3.0.1  Mar 2001
Number of Profiles= 5
Profile Names=PF 1,PF 2,PF 3,PF 4,PF 5
River Rch & RM=RIVER-1,Reach-1         ,20.031
     180     200     220     230     240
Boundary for River Rch & Prof#=RIVER-1,Reach-1         , 1
Up Type= 0
Dn Type= 3
Dn Slope=.0109
Boundary for River Rch & Prof#=RIVER-1,Reach-1         , 2
Up Type= 0
Dn Type= 3
Dn Slope=.0109
Boundary for River Rch & Prof#=RIVER-1,Reach-1         , 3
Up Type= 0
Dn Type= 3
Dn Slope=.0109
Boundary for River Rch & Prof#=RIVER-1,Reach-1         , 4
Up Type= 0
Dn Type= 3
Dn Slope=.0109
Boundary for River Rch & Prof#=RIVER-1,Reach-1         , 5
Up Type= 0
Dn Type= 3
Dn Slope=.0109
DSS Import GetInterval= 0
DSS Import GetPeak= 0
DSS Import FillOption= 0

--- degung-ch.g01 (geometry) ---

Geom Title=Imported Geom 01
Version=Version 3.0.1  Mar 2001

River Reach=RIVER-1         ,Reach-1
Reach XY= 2
              .5             .95              .5             .05

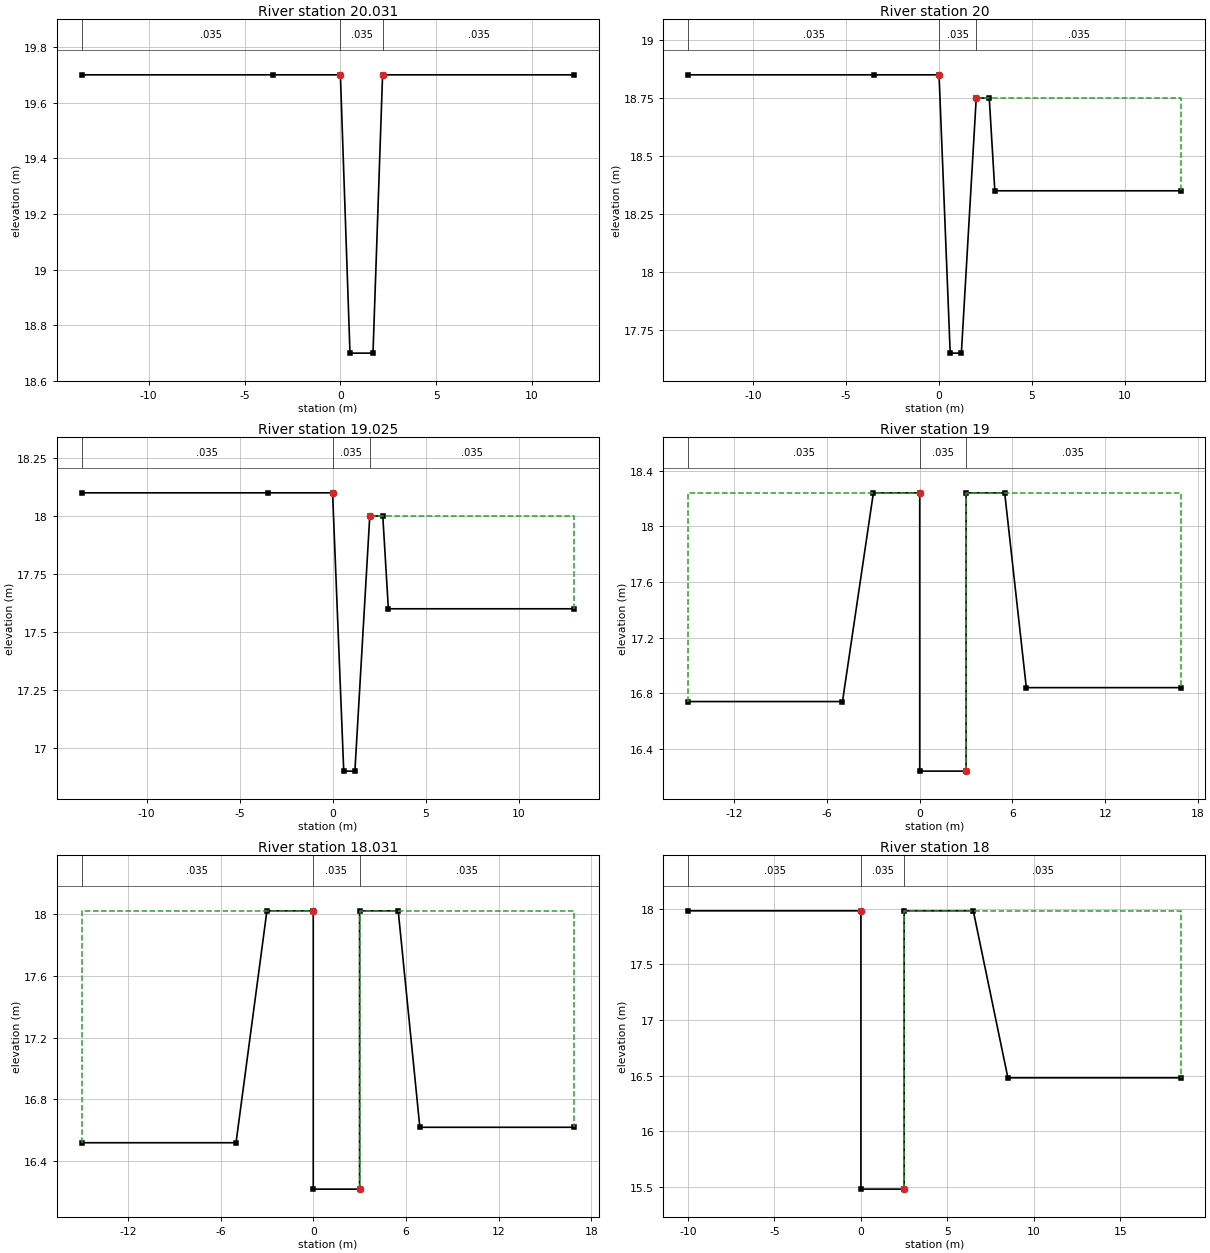
Type RM Length L Ch R = 1 ,20.031  ,31,31,31
#Sta/Elev= 7
   -13.5    19.7    -3.5    19.7       0    19.7      .5    18.7     1.7    18.7
     2.2    19.7    12.2    19.7
#Mann= 3 , 0 , 0
   -13.5    .035       0       0    .035       0     2.2    .035       0
#XS Ineff= 2 , 0
               0    19.7     2.2            19.7
Permanent Ineff=
       F       F
Bank Sta=0,2.2
XS Rating Curve= 0
Exp/Cntr=.3,.1

Type RM Length L Ch R = 1 ,20      ,25,25,25
#Sta/Elev= 9
   -13.5   18.85    -3.5   18.85       0   18.85      .6   17.65     1.2   17.65
       2   18.75     2.7   18.75       3   18.35      13   18.35
#Mann= 3 , 0 , 0
   -13.5    .035       0       0    .035       0       2    .035       0
#XS Ineff= 2 , 0
               0   18.85       2           18.75
Permanent Ineff=
       F       F
Bank Sta=0,2
XS Rating Curve= 0
Exp/Cntr=.3,.1

Type RM Length L Ch R = 1 ,19.025  ,25,25,25
#Sta/Elev= 9
   -13.5    18.1    -3.5    18.1       0    18.1      .6    16.9     1.2    16.9
       2      18     2.7      18       3    17.6      13    17.6
#Mann= 3 , 0 , 0
   -13.5    .035       0       0    .035       0       2    .035       0
#XS Ineff= 2 , 0
               0    18.1       2              18
Permanent Ineff=
       F       F
Bank Sta=0,2
XS Rating Curve= 0
Exp/Cntr=.3,.1

Type RM Length L Ch R = 1 ,19      ,19,19,19
#Sta/Elev= 10
     -15   16.74      -5   16.74      -3   18.24       0   18.24       0   16.24
       3   16.24       3   18.24     5.5   18.24     6.9   16.84    16.9   16.84
#Mann= 3 , 0 , 0
     -15    .035       0       0    .035       0       3    .035       0
#XS Ineff= 2 , 0
               0   18.24       3           18.24
Permanent Ineff=
       F       F
Bank Sta=0,3
XS Rating Curve= 0
Exp/Cntr=.3,.1

Type RM Length L Ch R = 1 ,18.031  ,31,31,31
#Sta/Elev= 10
     -15   16.52      -5   16.52      -3   18.02       0   18.02       0   16.22
       3   16.22       3   18.02     5.5   18.02     6.9   16.62    16.9   16.62
#Mann= 3 , 0 , 0
     -15    .035       0       0    .035       0       3    .035       0
#XS Ineff= 2 , 0
               0   18.02       3           18.02
Permanent Ineff=
       F       F
Bank Sta=0,3
XS Rating Curve= 0
Exp/Cntr=.3,.1

Type RM Length L Ch R = 1 ,18      ,50,50,50
#Sta/Elev= 8
     -10   17.98       0   17.98       0   15.48     2.5   15.48     2.5   17.98
     6.5   17.98     8.5   16.48    18.5   16.48
#Mann= 3 , 0 , 0
     -10    .035       0       0    .035       0     2.5    .035       0
#XS Ineff= 2 , 0
               0   17.98     2.5           17.98
Permanent Ineff=
       F       F
Bank Sta=0,2.5
XS Rating Curve= 0
Exp/Cntr=.3,.1

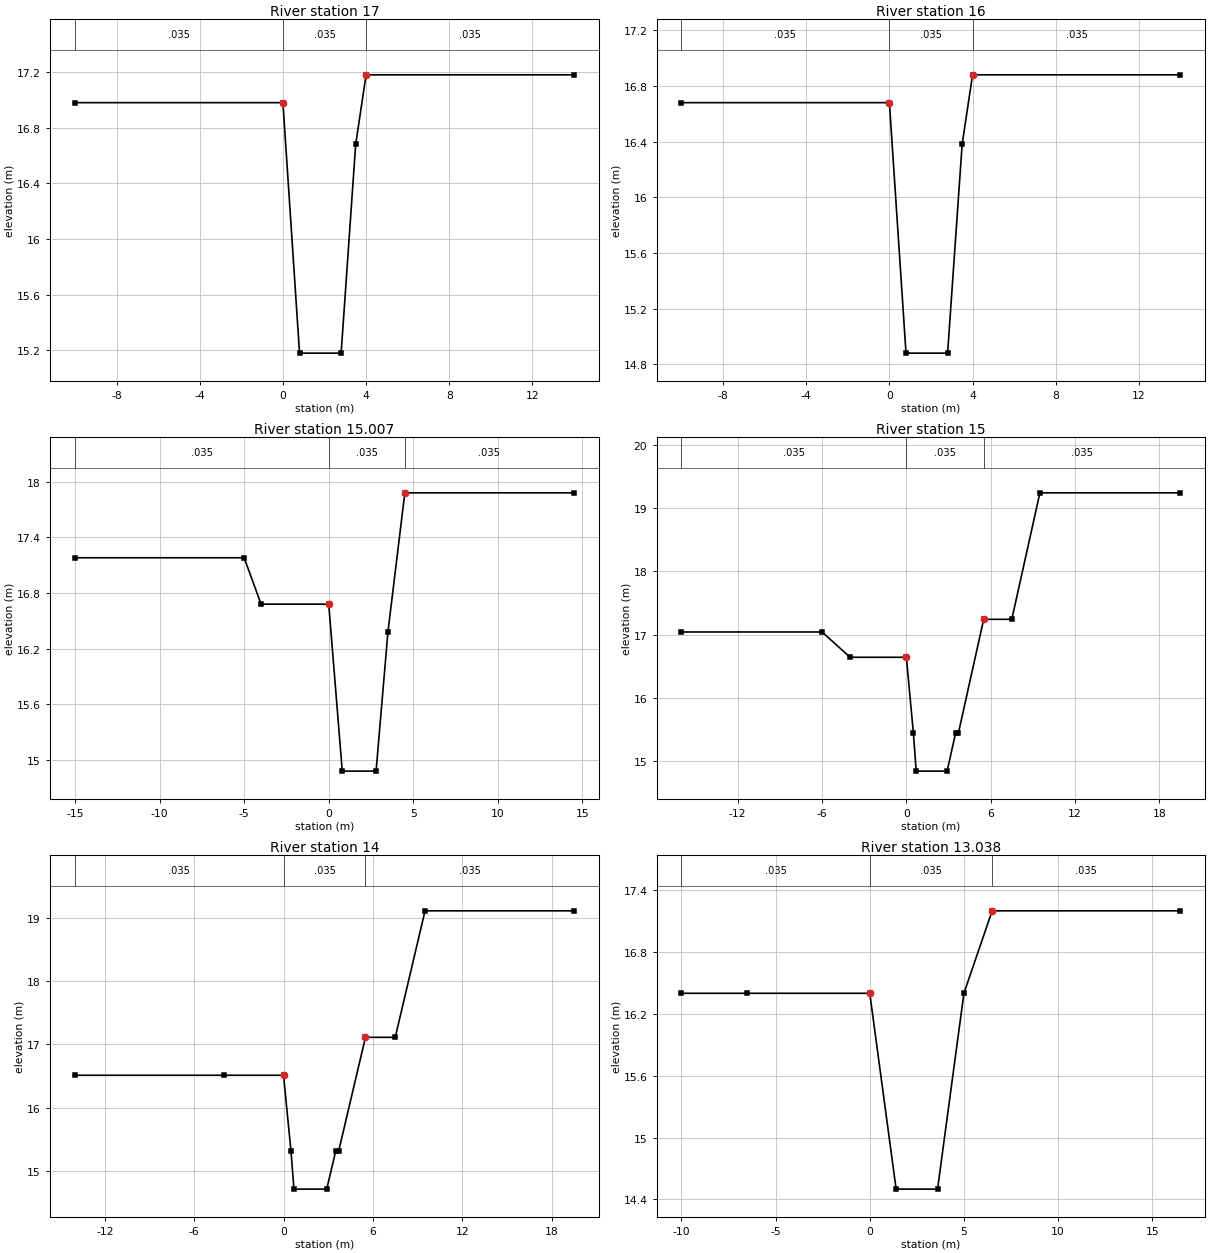
Type RM Length L Ch R = 1 ,17      ,50,50,50
#Sta/Elev= 7
     -10   16.98       0   16.98      .8   15.18     2.8   15.18     3.5   16.68
       4   17.18      14   17.18
#Mann= 3 , 0 , 0
     -10    .035       0       0    .035       0       4    .035       0
#XS Ineff= 2 , 0
               0   16.98       4           17.18
Permanent Ineff=
       F       F
Bank Sta=0,4
XS Rating Curve= 0
Exp/Cntr=.3,.1

Type RM Length L Ch R = 1 ,16      ,43,43,43
#Sta/Elev= 7
     -10   16.68       0   16.68      .8   14.88     2.8   14.88     3.5   16.38
       4   16.88      14   16.88
#Mann= 3 , 0 , 0
     -10    .035       0       0    .035       0       4    .035       0
#XS Ineff= 2 , 0
               0   16.68       4           16.88
Permanent Ineff=
       F       F
Bank Sta=0,4
XS Rating Curve= 0
Exp/Cntr=.3,.1

Type RM Length L Ch R = 1 ,15.007  ,7,7,7
#Sta/Elev= 9
     -15   17.18      -5   17.18      -4   16.68       0   16.68      .8   14.88
     2.8   14.88     3.5   16.38     4.5   17.88    14.5   17.88
#Mann= 3 , 0 , 0
     -15    .035       0       0    .035       0     4.5    .035       0
#XS Ineff= 2 , 0
               0   16.68     4.5           17.88
Permanent Ineff=
       F       F
Bank Sta=0,4.5
XS Rating Curve= 0
Exp/Cntr=.3,.1

Type RM Length L Ch R = 1 ,15      ,50,50,50
#Sta/Elev= 13
     -16   17.04      -6   17.04      -4   16.64       0   16.64      .5   15.44
      .7   14.84     2.9   14.84     3.5   15.44     3.7   15.44     5.5   17.24
     7.5   17.24     9.5   19.24    19.5   19.24
#Mann= 3 , 0 , 0
     -16    .035       0       0    .035       0     5.5    .035       0
#XS Ineff= 2 , 0
               0   16.64     5.5           17.24
Permanent Ineff=
       F       F
Bank Sta=0,5.5
XS Rating Curve= 0
Exp/Cntr=.3,.1

Type RM Length L Ch R = 1 ,14      ,12,12,12
#Sta/Elev= 12
     -14   16.51      -4   16.51       0   16.51      .5   15.31      .7   14.71
     2.9   14.71     3.5   15.31     3.7   15.31     5.5   17.11     7.5   17.11
     9.5   19.11    19.5   19.11
#Mann= 3 , 0 , 0
     -14    .035       0       0    .035       0     5.5    .035       0
#XS Ineff= 2 , 0
               0   16.51     5.5           17.11
Permanent Ineff=
       F       F
Bank Sta=0,5.5
XS Rating Curve= 0
Exp/Cntr=.3,.1

Type RM Length L Ch R = 1 ,13.038  ,38,38,38
#Sta/Elev= 8
     -10    16.4    -6.5    16.4       0    16.4     1.4    14.5     3.6    14.5
       5    16.4     6.5    17.2    16.5    17.2
#Mann= 3 , 0 , 0
     -10    .035       0       0    .035       0     6.5    .035       0
#XS Ineff= 2 , 0
       0       0    16.4     6.5       0    17.2
Permanent Ineff=
       F       F
Bank Sta=0,6.5
XS Rating Curve= 0
Exp/Cntr=.3,.1

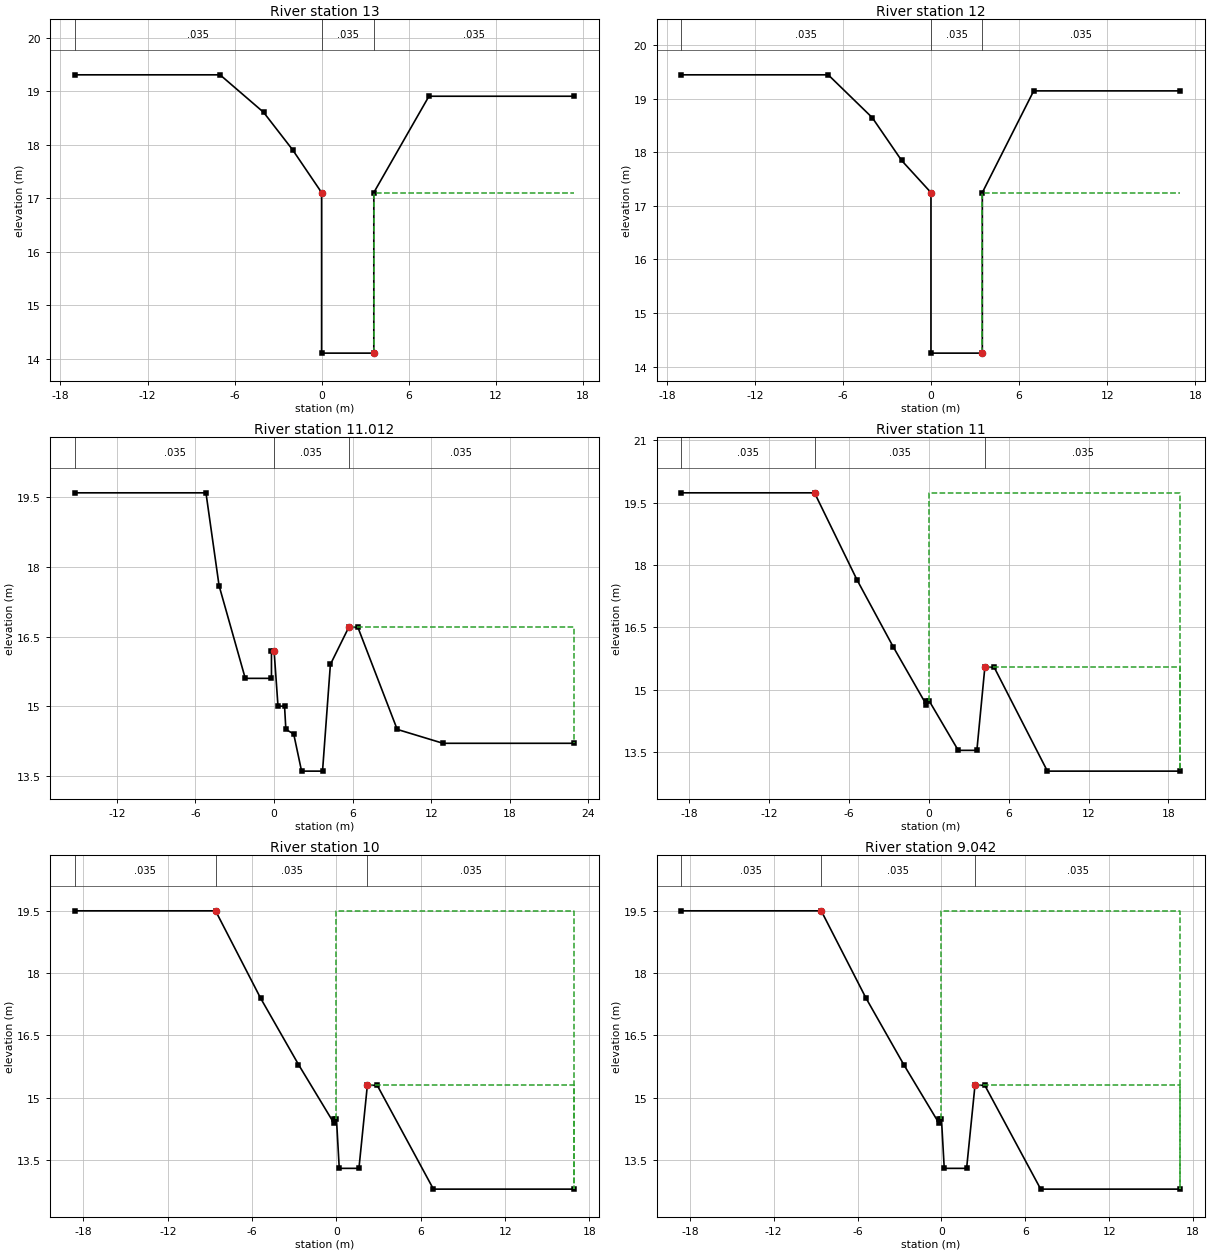
Type RM Length L Ch R = 1 ,13      ,50,50,50
#Sta/Elev= 10
     -17   19.31      -7   19.31      -4   18.61      -2   17.91       0   17.11
       0   14.11     3.6   14.11     3.6   17.11     7.4   18.91    17.4   18.91
#Mann= 3 , 0 , 0
     -17    .035       0       0    .035       0     3.6    .035       0
#XS Ineff= 2 , 0
               0   17.11     3.6           17.11
Permanent Ineff=
       F       F
Bank Sta=0,3.6
XS Rating Curve= 0
Exp/Cntr=.3,.1

Type RM Length L Ch R = 1 ,12      ,38,38,38
#Sta/Elev= 10
     -17   19.45      -7   19.45      -4   18.65      -2   17.85       0   17.25
       0   14.25     3.5   14.25     3.5   17.25       7   19.15      17   19.15
#Mann= 3 , 0 , 0
     -17    .035       0       0    .035       0     3.5    .035       0
#XS Ineff= 2 , 0
               0   17.25     3.5           17.25
Permanent Ineff=
       F       F
Bank Sta=0,3.5
XS Rating Curve= 0
Exp/Cntr=.3,.1

Type RM Length L Ch R = 1 ,11.012  ,12,12,12
#Sta/Elev= 19
   -15.2    19.6    -5.2    19.6    -4.2    17.6    -2.2    15.6     -.2    15.6
     -.2    16.2       0    16.2      .3      15      .8      15      .9    14.5
     1.5    14.4     2.1    13.6     3.7    13.6     4.3    15.9     5.7    16.7
     6.4    16.7     9.4    14.5    12.9    14.2    22.9    14.2
#Mann= 3 , 0 , 0
   -15.2    .035       0       0    .035       0     5.7    .035       0
#XS Ineff= 2 , 0
               0    16.2     5.7            16.7
Permanent Ineff=
       F       F
Bank Sta=0,5.7
XS Rating Curve= 0
Exp/Cntr=.3,.1

Type RM Length L Ch R = 1 ,11      ,50,50,50
#Sta/Elev= 13
   -18.6   19.74    -8.6   19.74    -5.4   17.64    -2.7   16.04     -.2   14.64
     -.2   14.74       0   14.74     2.2   13.54     3.6   13.54     4.2   15.54
     4.9   15.54     8.9   13.04    18.9   13.04
#Mann= 3 , 0 , 0
   -18.6    .035       0    -8.6    .035       0     4.2    .035       0
#XS Ineff= 2 , 0
       0    -8.6   19.74     4.2       0   15.54
Permanent Ineff=
       F       F
Bank Sta=-8.6,4.2
XS Rating Curve= 0
Exp/Cntr=.3,.1

Type RM Length L Ch R = 1 ,10      ,8,8,8
#Sta/Elev= 13
   -18.6    19.5    -8.6    19.5    -5.4    17.4    -2.7    15.8     -.2    14.4
     -.2    14.5       0    14.5      .2    13.3     1.6    13.3     2.2    15.3
     2.9    15.3     6.9    12.8    16.9    12.8
#Mann= 3 , 0 , 0
   -18.6    .035       0    -8.6    .035       0     2.2    .035       0
#XS Ineff= 2 , 0
       0    -8.6    19.5     2.2       0    15.3
Permanent Ineff=
       F       F
Bank Sta=-8.6,2.2
XS Rating Curve= 0
Exp/Cntr=.3,.1

Type RM Length L Ch R = 1 ,9.042   ,7,7,7
#Sta/Elev= 13
   -18.6    19.5    -8.6    19.5    -5.4    17.4    -2.7    15.8     -.2    14.4
     -.2    14.5       0    14.5      .2    13.3     1.8    13.3     2.4    15.3
     3.1    15.3     7.1    12.8    17.1    12.8
#Mann= 3 , 0 , 0
   -18.6    .035       0    -8.6    .035       0     2.4    .035       0
#XS Ineff= 2 , 0
       0    -8.6    19.5     2.4       0    15.3
Permanent Ineff=
       F       F
Bank Sta=-8.6,2.4
XS Rating Curve= 0
Exp/Cntr=.3,.1

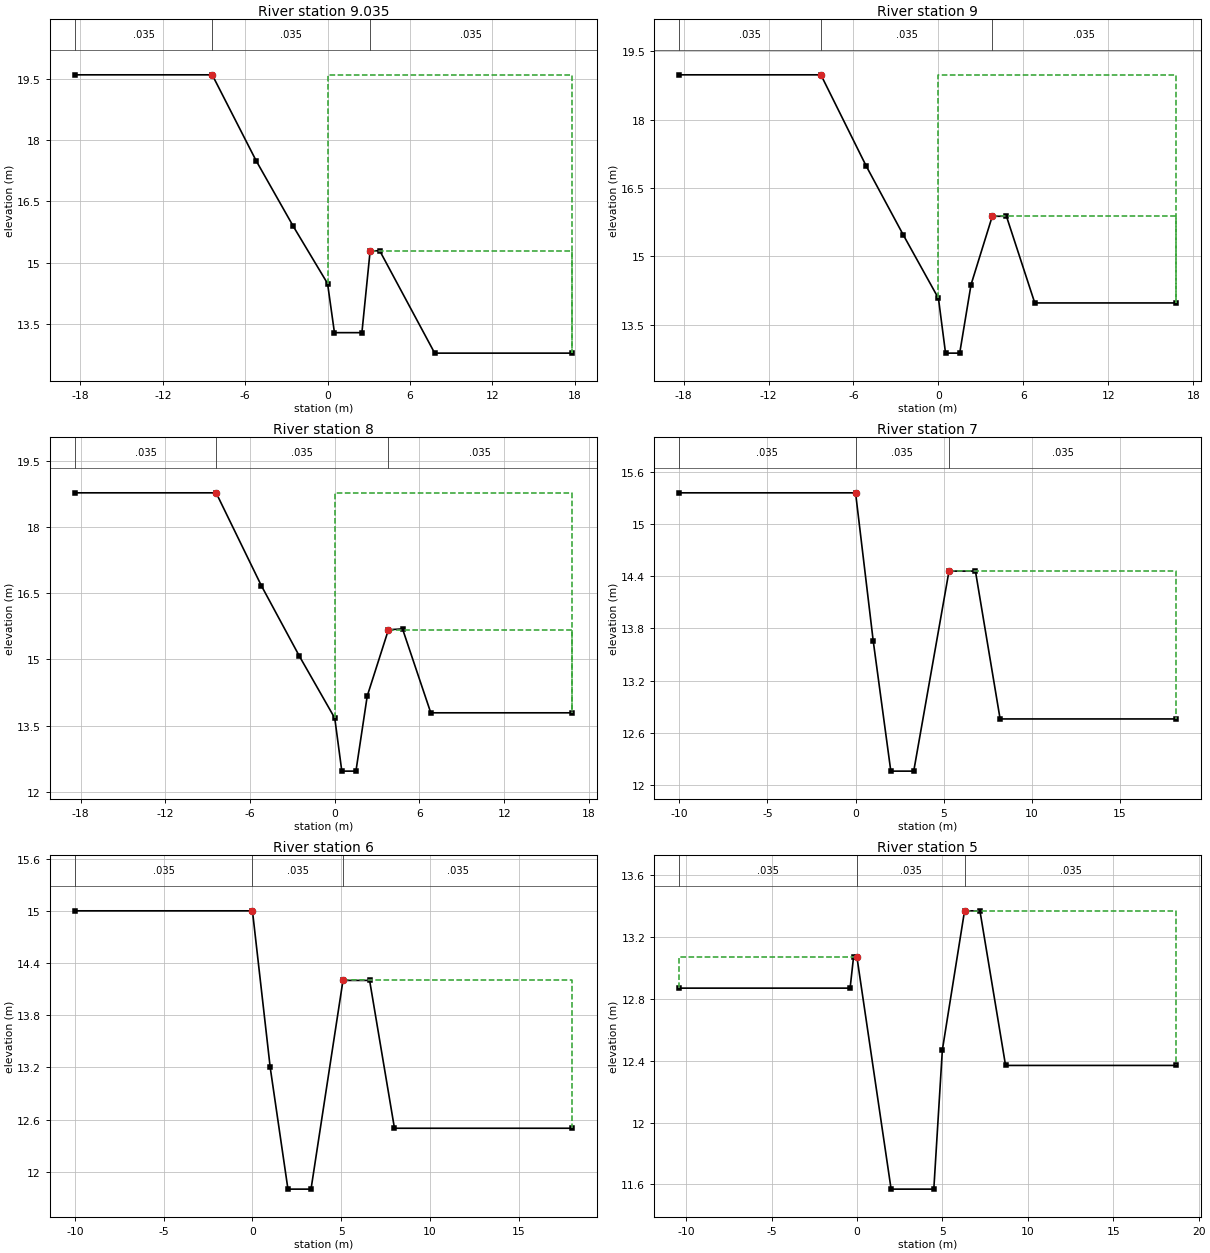
Type RM Length L Ch R = 1 ,9.035   ,35,35,35
#Sta/Elev= 11
   -18.4   19.59    -8.4   19.59    -5.2   17.49    -2.5   15.89       0   14.49
      .5   13.29     2.5   13.29     3.1   15.29     3.8   15.29     7.8   12.79
    17.8   12.79
#Mann= 3 , 0 , 0
   -18.4    .035       0    -8.4    .035       0     3.1    .035       0
#XS Ineff= 2 , 0
       0    -8.4   19.59     3.1       0   15.29
Permanent Ineff=
       F       F
Bank Sta=-8.4,3.1
XS Rating Curve= 0
Exp/Cntr=.3,.1

Type RM Length L Ch R = 1 ,9       ,50,50,50
#Sta/Elev= 12
   -18.3   18.98    -8.3   18.98    -5.1   16.98    -2.5   15.48       0   14.08
      .5   12.88     1.5   12.88     2.3   14.38     3.8   15.88     4.8   15.88
     6.8   13.98    16.8   13.98
#Mann= 3 , 0 , 0
   -18.3    .035       0    -8.3    .035       0     3.8    .035       0
#XS Ineff= 2 , 0
       0    -8.3   18.98     3.8       0   15.88
Permanent Ineff=
       F       F
Bank Sta=-8.3,3.8
XS Rating Curve= 0
Exp/Cntr=.3,.1

Type RM Length L Ch R = 1 ,8       ,50,50,50
#Sta/Elev= 12
   -18.4   18.77    -8.4   18.77    -5.2   16.67    -2.5   15.07       0   13.67
      .5   12.47     1.5   12.47     2.3   14.17     3.8   15.67     4.8   15.69
     6.8   13.79    16.8   13.79
#Mann= 3 , 0 , 0
   -18.4    .035       0    -8.4    .035       0     3.8    .035       0
#XS Ineff= 2 , 0
       0    -8.4   18.77     3.8       0   15.67
Permanent Ineff=
       F       F
Bank Sta=-8.4,3.8
XS Rating Curve= 0
Exp/Cntr=.3,.1

Type RM Length L Ch R = 1 ,7       ,50,50,50
#Sta/Elev= 9
     -10   15.36       0   15.36       1   13.66       2   12.16     3.3   12.16
     5.3   14.46     6.8   14.46     8.2   12.76    18.2   12.76
#Mann= 3 , 0 , 0
     -10    .035       0       0    .035       0     5.3    .035       0
#XS Ineff= 2 , 0
               0   15.36     5.3           14.46
Permanent Ineff=
       F       F
Bank Sta=0,5.3
XS Rating Curve= 0
Exp/Cntr=.3,.1

Type RM Length L Ch R = 1 ,6       ,50,50,50
#Sta/Elev= 9
     -10      15       0      15       1    13.2       2    11.8     3.3    11.8
     5.1    14.2     6.6    14.2       8    12.5      18    12.5
#Mann= 3 , 0 , 0
     -10    .035       0       0    .035       0     5.1    .035       0
#XS Ineff= 2 , 0
               0      15     5.1            14.2
Permanent Ineff=
       F       F
Bank Sta=0,5.1
XS Rating Curve= 0
Exp/Cntr=.3,.1

Type RM Length L Ch R = 1 ,5       ,50,50,50
#Sta/Elev= 11
   -10.4   12.87     -.4   12.87     -.2   13.07       0   13.07       2   11.57
     4.5   11.57       5   12.47     6.3   13.37     7.2   13.37     8.7   12.37
    18.7   12.37
#Mann= 3 , 0 , 0
   -10.4    .035       0       0    .035       0     6.3    .035       0
#XS Ineff= 2 , 0
               0   13.07     6.3           13.37
Permanent Ineff=
       F       F
Bank Sta=0,6.3
XS Rating Curve= 0
Exp/Cntr=.3,.1

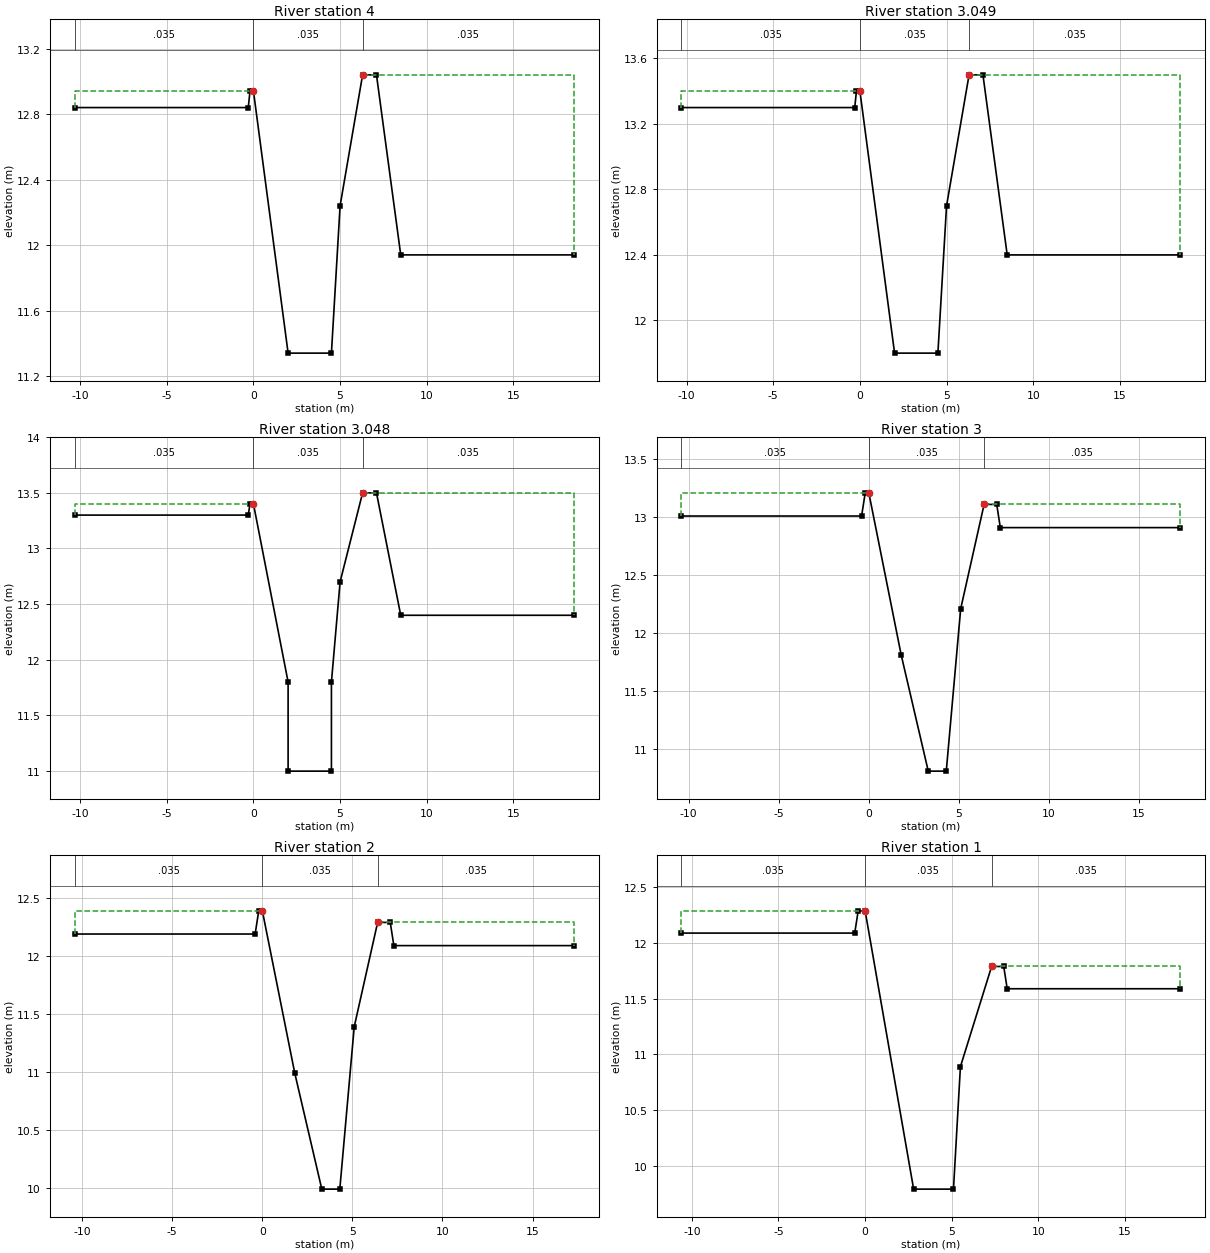
Type RM Length L Ch R = 1 ,4       ,1,1,1
#Sta/Elev= 11
   -10.3   12.84     -.3   12.84     -.2   12.94       0   12.94       2   11.34
     4.5   11.34       5   12.24     6.3   13.04     7.1   13.04     8.5   11.94
    18.5   11.94
#Mann= 3 , 0 , 0
   -10.3    .035       0       0    .035       0     6.3    .035       0
#XS Ineff= 2 , 0
               0   12.94     6.3           13.04
Permanent Ineff=
       F       F
Bank Sta=0,6.3
XS Rating Curve= 0
Exp/Cntr=.3,.1

Type RM Length L Ch R = 1 ,3.049   ,1,1,1
#Sta/Elev= 11
   -10.3    13.3     -.3    13.3     -.2    13.4       0    13.4       2    11.8
     4.5    11.8       5    12.7     6.3    13.5     7.1    13.5     8.5    12.4
    18.5    12.4
#Mann= 3 , 0 , 0
   -10.3    .035       0       0    .035       0     6.3    .035       0
#XS Ineff= 2 , 0
               0    13.4     6.3            13.5
Permanent Ineff=
       F       F
Bank Sta=0,6.3
XS Rating Curve= 0
Exp/Cntr=.3,.1

Type RM Length L Ch R = 1 ,3.048   ,48,48,48
#Sta/Elev= 13
   -10.3    13.3     -.3    13.3     -.2    13.4       0    13.4       2    11.8
       2      11     4.5      11     4.5    11.8       5    12.7     6.3    13.5
     7.1    13.5     8.5    12.4    18.5    12.4
#Mann= 3 , 0 , 0
   -10.3    .035       0       0    .035       0     6.3    .035       0
#XS Ineff= 2 , 0
               0    13.4     6.3            13.5
Permanent Ineff=
       F       F
Bank Sta=0,6.3
XS Rating Curve= 0
Exp/Cntr=.3,.1

Type RM Length L Ch R = 1 ,3       ,50,50,50
#Sta/Elev= 12
   -10.4   13.01     -.4   13.01     -.2   13.21       0   13.21     1.8   11.81
     3.3   10.81     4.3   10.81     5.1   12.21     6.4   13.11     7.1   13.11
     7.3   12.91    17.3   12.91
#Mann= 3 , 0 , 0
   -10.4    .035       0       0    .035       0     6.4    .035       0
#XS Ineff= 2 , 0
               0   13.21     6.4           13.11
Permanent Ineff=
       F       F
Bank Sta=0,6.4
XS Rating Curve= 0
Exp/Cntr=.3,.1

Type RM Length L Ch R = 1 ,2       ,50,50,50
#Sta/Elev= 12
   -10.4   12.19     -.4   12.19     -.2   12.39       0   12.39     1.8   10.99
     3.3    9.99     4.3    9.99     5.1   11.39     6.4   12.29     7.1   12.29
     7.3   12.09    17.3   12.09
#Mann= 3 , 0 , 0
   -10.4    .035       0       0    .035       0     6.4    .035       0
#XS Ineff= 2 , 0
               0   12.39     6.4           12.29
Permanent Ineff=
       F       F
Bank Sta=0,6.4
XS Rating Curve= 0
Exp/Cntr=.3,.1

Type RM Length L Ch R = 1 ,1       ,50,50,50
#Sta/Elev= 11
   -10.6   12.09     -.6   12.09     -.4   12.29       0   12.29     2.8    9.79
     5.1    9.79     5.5   10.89     7.3   11.79       8   11.79     8.2   11.59
    18.2   11.59
#Mann= 3 , 0 , 0
   -10.6    .035       0       0    .035       0     7.3    .035       0
#XS Ineff= 2 , 0
               0   12.29     7.3           11.79
Permanent Ineff=
       F       F
Bank Sta=0,7.3
XS Rating Curve= 0
Exp/Cntr=.3,.1

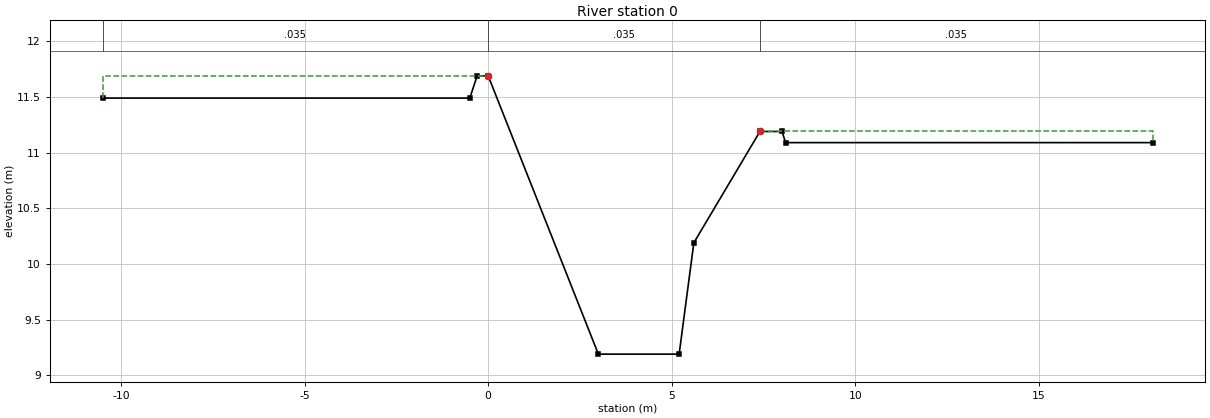
Type RM Length L Ch R = 1 ,0       ,0,0,0
#Sta/Elev= 11
   -10.5   11.49     -.5   11.49     -.3   11.69       0   11.69       3    9.19
     5.2    9.19     5.6   10.19     7.4   11.19       8   11.19     8.1   11.09
    18.1   11.09
#Mann= 3 , 0 , 0
   -10.5    .035       0       0    .035       0     7.4    .035       0
#XS Ineff= 2 , 0
               0   11.69     7.4           11.19
Permanent Ineff=
       F       F
Bank Sta=0,7.4
XS Rating Curve= 0
Exp/Cntr=.3,.1

Chan Stop Cuts=-1