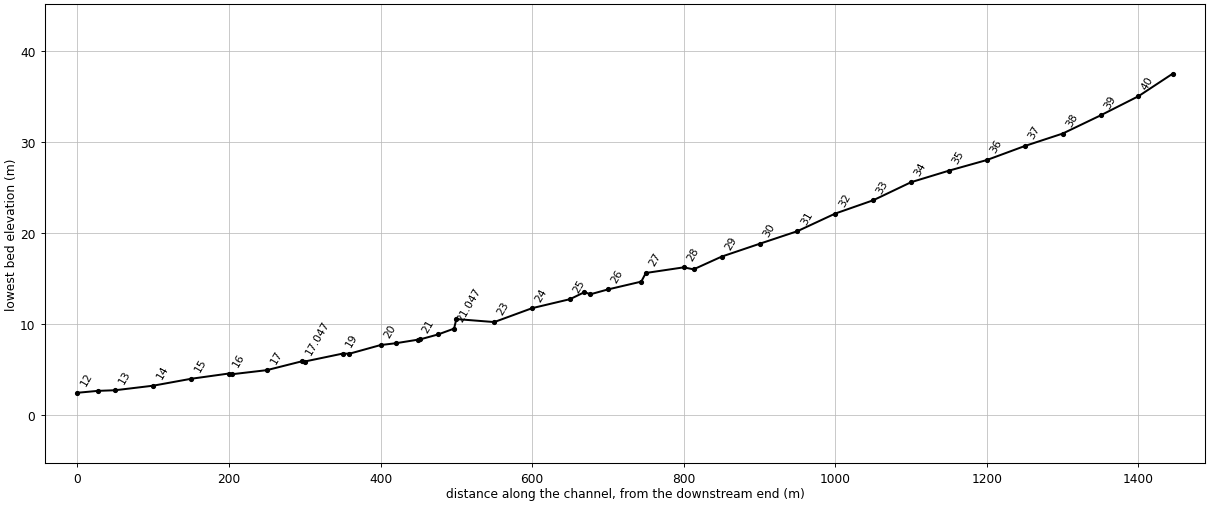
--- skr.prj (project) ---

Proj Title=sikuri
Current Plan=p01
Default Exp/Contr=.3,.1
SI Units
Geom File=g01
Flow File=f01
Plan File=p01
Y Axis Title=Elevation
X Axis Title(PF)=Main Channel Distance
X Axis Title(XS)=Station
BEGIN DESCRIPTION:
           BACK WATER COMPUTATION
      APPLICATION OF HEC-2 BY Samju Construction Engineering
      sigaere-ch: 30,50,80,100,150³âºóµµ °³¼öÀü
END DESCRIPTION:
DSS Export Rating Curves= 0
DSS Export Rating Curve Sorted= 0
DSS Export Volume Flow Curves= 0
DXF OffsetX= 0
DXF OffsetY= 0
DXF ScaleX= 1
DXF ScaleY= 10

--- skr.p01 (plan) ---

Plan Title=Imported Plan 01
Version=Version 3.0.1  Mar 2001
Short Identifier=Imported Pla
Geom File=g01
Flow File=f01
Subcritical Flow
K Sum by GR= 0
Std Step Tol= 0.003
Critical Tol= 0.003
Num of Std Step Trials= 20
Max Error Tol= 0.1
Flow Tol Ratio= 0.001
Split Flow NTrial= 30
Split Flow Tol= 0.02
Split Flow Ratio= 0.02
Log Output Level= 0
Friction Slope Method= 1
Unsteady Friction Slope Method= 2
Parabolic Critical Depth
Global Vel Dist= 0 , 0 , 0
Global Log Level= 0
CheckData=True
Encroach Param=-1 ,0,0, 0
Computation Interval=1HOUR
Output Interval=1HOUR
Run HTab= 0
Run UNet= 0
Run PostProcess= 0
UNET Theta= 1
UNET ZTol= 0.02
UNET ZSATol= 0.1
UNET MxIter= 20
UNET MaxInSteps= 20
UNET DtIC= 0
UNET DtMin= 0
UNET MaxCRTS= 20
UNET WFStab= 2
UNET SFStab= 1
UNET WFX= 1
UNET SFX= 1
UNET Convert EG Bridges=-1
UNET Use Existing IB Tables=-1
Instantaneous Interval=1HOUR
Write IC File= 0
Write Velocity= 0
Write Detailed= 0

--- skr.f01 (steady flow) ---

Flow Title=Imported Flow 01
Version=Version 3.0.1  Mar 2001
Number of Profiles= 5
Profile Names=10yr,20ry,30ry,50yr,80yr
River Rch & RM=RIVER-1,Reach-1         ,40.045
   10.52   11.59   12.23   13.02   13.75
River Rch & RM=RIVER-1,Reach-1         ,20
    12.6    13.9   14.66   15.62    16.5
River Rch & RM=SAGEORI,SAGEORI         ,40.045
   10.52   11.59   12.23   13.02   13.75
River Rch & RM=SAGEORI,SAGEORI         ,20
    12.6    13.9   14.66   15.62    16.5
Boundary for River Rch & Prof#=SAGEORI,SAGEORI         , 1
Up Type= 0
Dn Type= 3
Dn Slope=.019
Boundary for River Rch & Prof#=SAGEORI,SAGEORI         , 2
Up Type= 0
Dn Type= 3
Dn Slope=.019
Boundary for River Rch & Prof#=SAGEORI,SAGEORI         , 3
Up Type= 0
Dn Type= 3
Dn Slope=.019
Boundary for River Rch & Prof#=SAGEORI,SAGEORI         , 4
Up Type= 0
Dn Type= 3
Dn Slope=.019
Boundary for River Rch & Prof#=SAGEORI,SAGEORI         , 5
Up Type= 0
Dn Type= 3
Dn Slope=.019
DSS Import GetInterval= 0
DSS Import GetPeak= 0
DSS Import FillOption= 0

--- skr.g01 (geometry) ---

Geom Title=Imported Geom 01
Version=Version 3.0.1  Mar 2001

River Reach=SAGEORI         ,SAGEORI
Reach XY= 2
              .5             .95              .5             .05

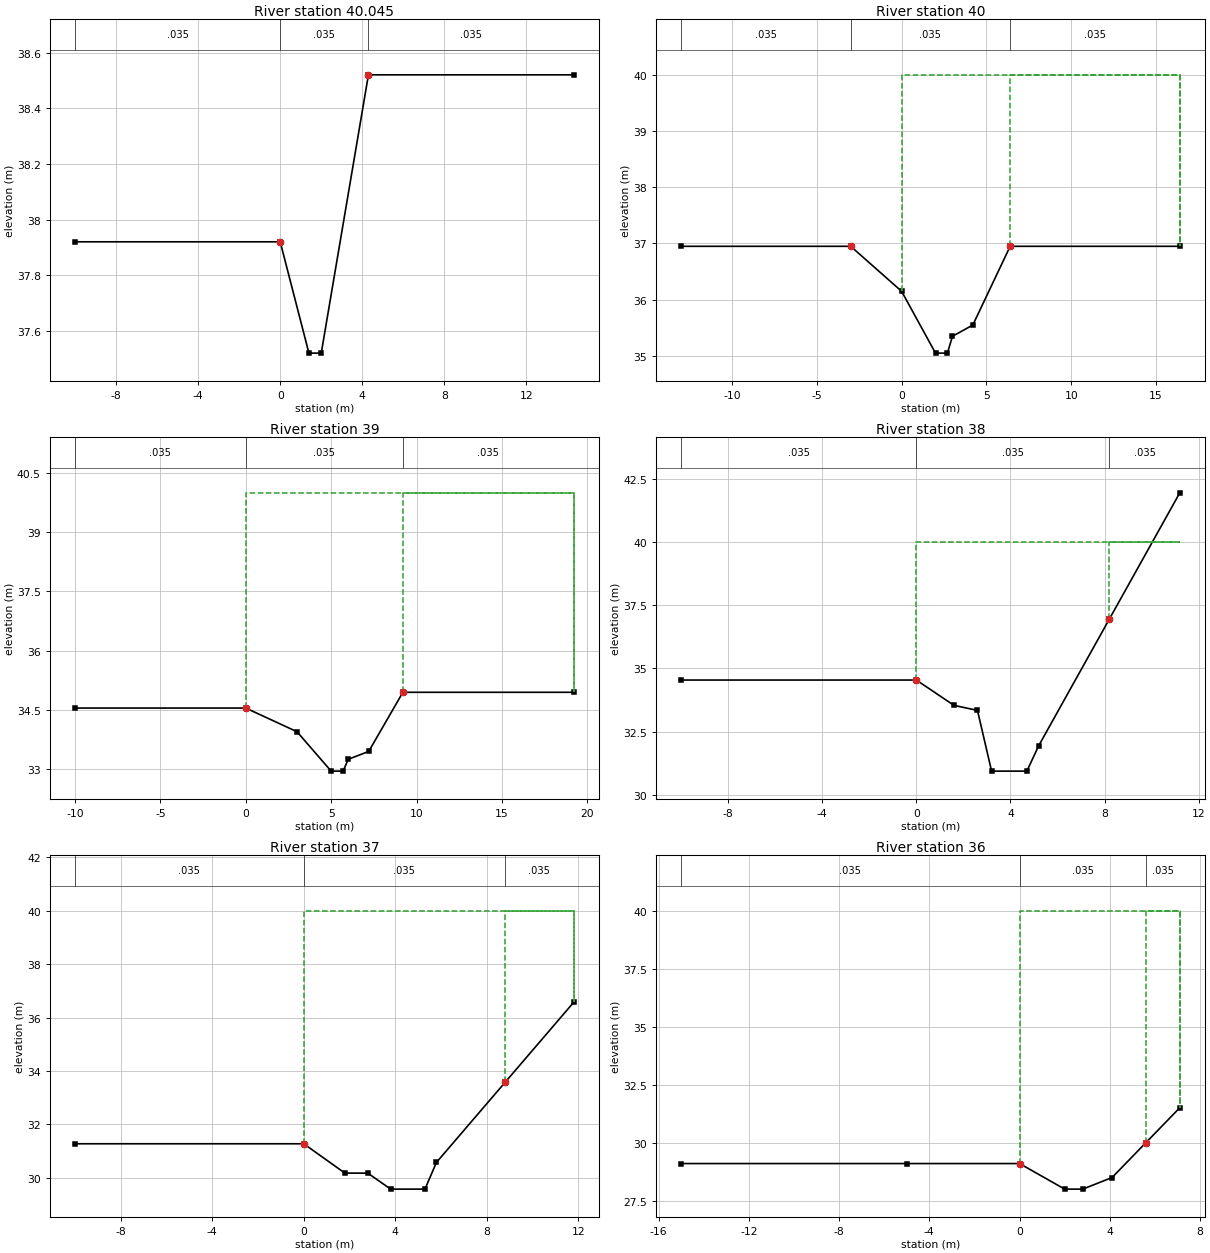
Type RM Length L Ch R = 1 ,40.045  ,45,45,45
#Sta/Elev= 6
     -10   37.92       0   37.92     1.4   37.52       2   37.52     4.3   38.52
    14.3   38.52
#Mann= 3 , 0 , 0
     -10    .035       0       0    .035       0     4.3    .035       0
#XS Ineff= 2 , 0
       0       0      50     4.3       0      50
Permanent Ineff=
       F       F
#Block Obstruct= 2 , 0
                             4.3
Bank Sta=0,4.3
XS Rating Curve= 0
Exp/Cntr=.3,.1

Type RM Length L Ch R = 1 ,40      ,50,50,50
#Sta/Elev= 9
     -13   36.95      -3   36.95       0   36.15       2   35.05     2.7   35.05
       3   35.35     4.2   35.55     6.4   36.95    16.4   36.95
#Mann= 3 , 0 , 0
     -13    .035       0      -3    .035       0     6.4    .035       0
#XS Ineff= 2 , 0
       0      -3      40     6.4       0      40
Permanent Ineff=
       F       F
#Block Obstruct= 2 , 0
                             6.4
Bank Sta=-3,6.4
XS Rating Curve= 0
Exp/Cntr=.3,.1

Type RM Length L Ch R = 1 ,39      ,50,50,50
#Sta/Elev= 9
     -10   34.54       0   34.54       3   33.94       5   32.94     5.7   32.94
       6   33.24     7.2   33.44     9.2   34.94    19.2   34.94
#Mann= 3 , 0 , 0
     -10    .035       0       0    .035       0     9.2    .035       0
#XS Ineff= 2 , 0
       0       0      40     9.2       0      40
Permanent Ineff=
       F       F
#Block Obstruct= 2 , 0
                             9.2
Bank Sta=0,9.2
XS Rating Curve= 0
Exp/Cntr=.3,.1

Type RM Length L Ch R = 1 ,38      ,50,50,50
#Sta/Elev= 9
     -10   34.54       0   34.54     1.6   33.54     2.6   33.34     3.2   30.94
     4.7   30.94     5.2   31.94     8.2   36.94    11.2   41.94
#Mann= 3 , 0 , 0
     -10    .035       0       0    .035       0     8.2    .035       0
#XS Ineff= 2 , 0
       0       0      40     8.2       0      40
Permanent Ineff=
       F       F
#Block Obstruct= 2 , 0
                             8.2
Bank Sta=0,8.2
XS Rating Curve= 0
Exp/Cntr=.3,.1

Type RM Length L Ch R = 1 ,37      ,50,50,50
#Sta/Elev= 9
     -10   31.27       0   31.27     1.8   30.17     2.8   30.17     3.8   29.57
     5.3   29.57     5.8   30.57     8.8   33.57    11.8   36.57
#Mann= 3 , 0 , 0
     -10    .035       0       0    .035       0     8.8    .035       0
#XS Ineff= 2 , 0
       0       0      40     8.8       0      40
Permanent Ineff=
       F       F
#Block Obstruct= 2 , 0
                             8.8
Bank Sta=0,8.8
XS Rating Curve= 0
Exp/Cntr=.3,.1

Type RM Length L Ch R = 1 ,36      ,50,50,50
#Sta/Elev= 8
     -15   29.13      -5   29.13       0   29.13       2   28.03     2.8   28.03
     4.1   28.53     5.6   30.03     7.1   31.53
#Mann= 3 , 0 , 0
     -15    .035       0       0    .035       0     5.6    .035       0
#XS Ineff= 2 , 0
       0       0      40     5.6       0      40
Permanent Ineff=
       F       F
#Block Obstruct= 2 , 0
                             5.6
Bank Sta=0,5.6
XS Rating Curve= 0
Exp/Cntr=.3,.1

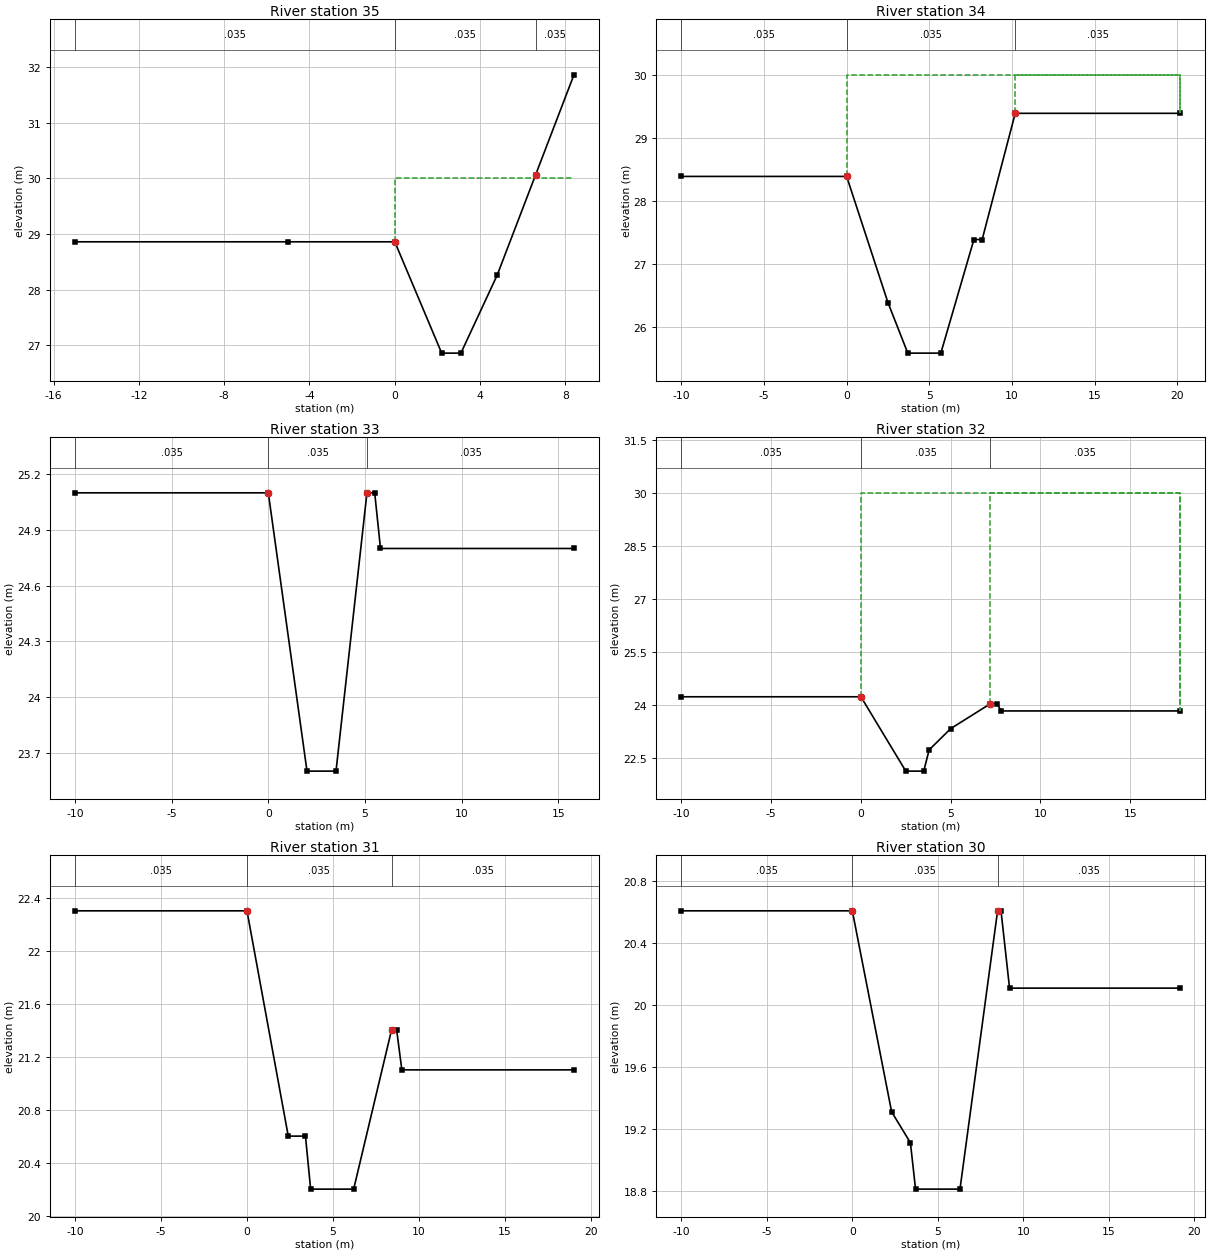
Type RM Length L Ch R = 1 ,35      ,50,50,50
#Sta/Elev= 8
     -15   28.86      -5   28.86       0   28.86     2.2   26.86     3.1   26.86
     4.8   28.26     6.6   30.06     8.4   31.86
#Mann= 3 , 0 , 0
     -15    .035       0       0    .035       0     6.6    .035       0
#XS Ineff= 2 , 0
       0       0      30     6.6       0      30
Permanent Ineff=
       F       F
#Block Obstruct= 2 , 0
                             6.6
Bank Sta=0,6.6
XS Rating Curve= 0
Exp/Cntr=.3,.1

Type RM Length L Ch R = 1 ,34      ,50,50,50
#Sta/Elev= 9
     -10   28.39       0   28.39     2.5   26.39     3.7   25.59     5.7   25.59
     7.7   27.39     8.2   27.39    10.2   29.39    20.2   29.39
#Mann= 3 , 0 , 0
     -10    .035       0       0    .035       0    10.2    .035       0
#XS Ineff= 2 , 0
       0       0      30    10.2       0      30
Permanent Ineff=
       F       F
#Block Obstruct= 2 , 0
                            10.2
Bank Sta=0,10.2
XS Rating Curve= 0
Exp/Cntr=.3,.1

Type RM Length L Ch R = 1 ,33      ,50,50,50
#Sta/Elev= 8
     -10    25.1       0    25.1       2    23.6     3.5    23.6     5.1    25.1
     5.5    25.1     5.8    24.8    15.8    24.8
#Mann= 3 , 0 , 0
     -10    .035       0       0    .035       0     5.1    .035       0
#XS Ineff= 2 , 0
       0       0      30     5.1       0      30
Permanent Ineff=
       F       F
#Block Obstruct= 2 , 0
                             5.1
Bank Sta=0,5.1
XS Rating Curve= 0
Exp/Cntr=.3,.1

Type RM Length L Ch R = 1 ,32      ,50,50,50
#Sta/Elev= 10
     -10   24.24       0   24.24     2.5   22.14     3.5   22.14     3.8   22.74
       5   23.34     7.2   24.04     7.6   24.04     7.8   23.84    17.8   23.84
#Mann= 3 , 0 , 0
     -10    .035       0       0    .035       0     7.2    .035       0
#XS Ineff= 2 , 0
       0       0      30     7.2       0      30
Permanent Ineff=
       F       F
#Block Obstruct= 2 , 0
                             7.2
Bank Sta=0,7.2
XS Rating Curve= 0
Exp/Cntr=.3,.1

Type RM Length L Ch R = 1 ,31      ,50,50,50
#Sta/Elev= 10
     -10    22.3       0    22.3     2.4    20.6     3.4    20.6     3.7    20.2
     6.2    20.2     8.4    21.4     8.7    21.4       9    21.1      19    21.1
#Mann= 3 , 0 , 0
     -10    .035       0       0    .035       0     8.4    .035       0
#XS Ineff= 2 , 0
       0       0      30     8.4       0      30
Permanent Ineff=
       F       F
#Block Obstruct= 2 , 0
                             8.4
Bank Sta=0,8.4
XS Rating Curve= 0
Exp/Cntr=.3,.1

Type RM Length L Ch R = 1 ,30      ,50,50,50
#Sta/Elev= 10
     -10   20.61       0   20.61     2.3   19.31     3.4   19.11     3.7   18.81
     6.3   18.81     8.5   20.61     8.7   20.61     9.2   20.11    19.2   20.11
#Mann= 3 , 0 , 0
     -10    .035       0       0    .035       0     8.5    .035       0
#XS Ineff= 2 , 0
       0       0      30     8.5       0      30
Permanent Ineff=
       F       F
#Block Obstruct= 2 , 0
                             8.5
Bank Sta=0,8.5
XS Rating Curve= 0
Exp/Cntr=.3,.1

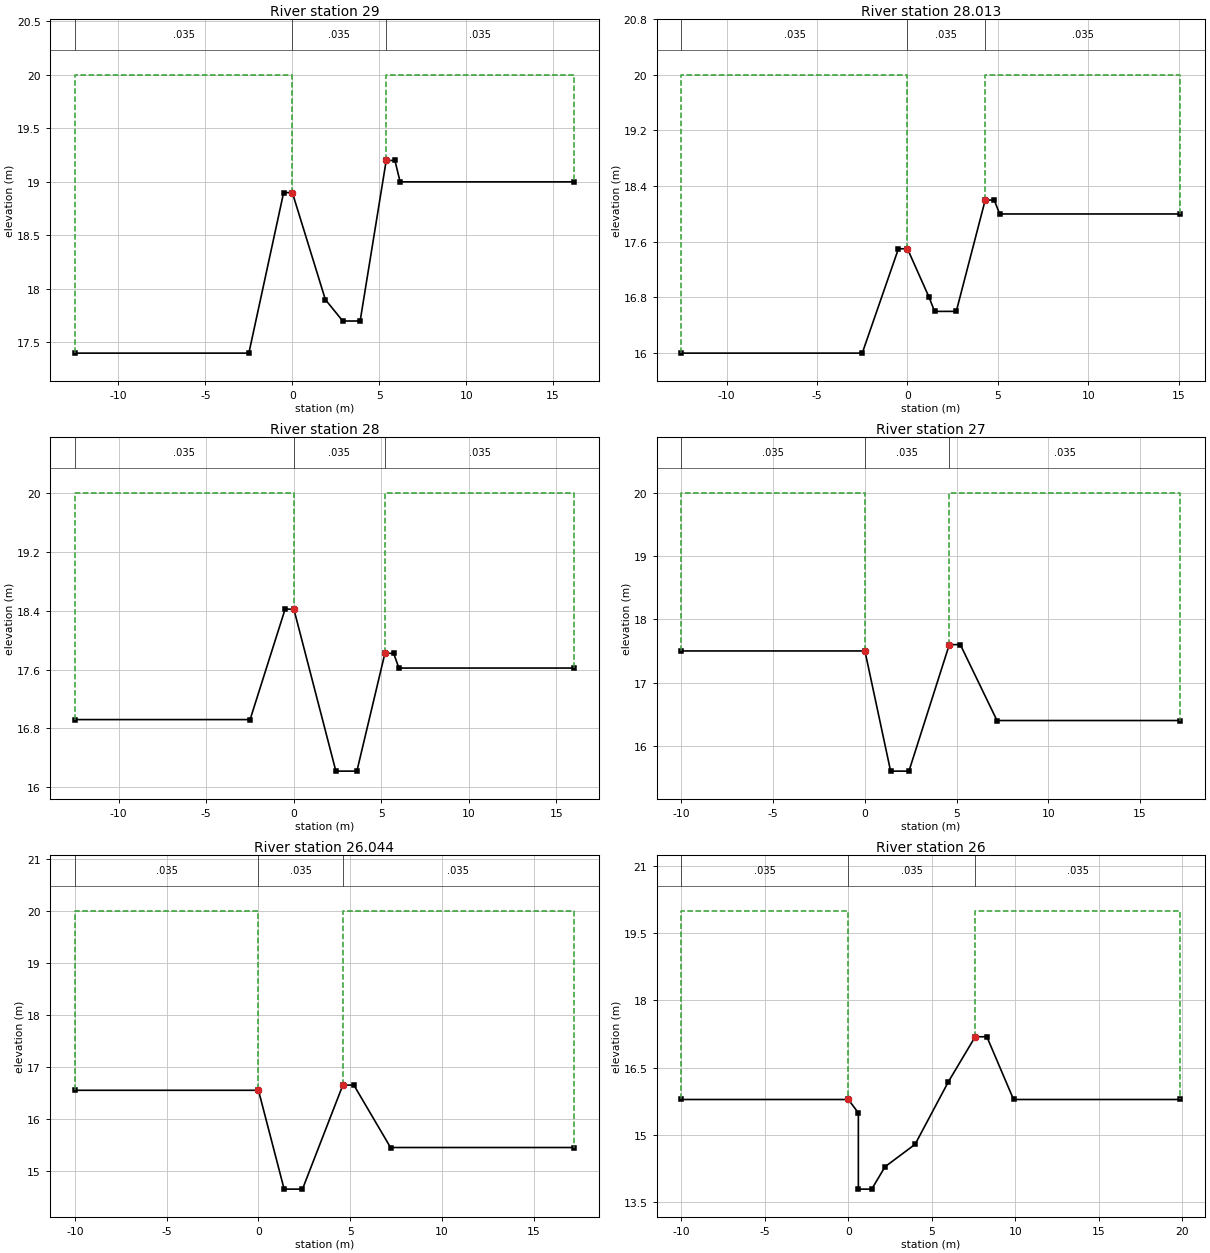
Type RM Length L Ch R = 1 ,29      ,37,37,37
#Sta/Elev= 11
   -12.5    17.4    -2.5    17.4     -.5    18.9       0    18.9     1.9    17.9
     2.9    17.7     3.9    17.7     5.4    19.2     5.9    19.2     6.2      19
    16.2      19
#Mann= 3 , 0 , 0
   -12.5    .035       0       0    .035       0     5.4    .035       0
#XS Ineff= 2 , 0
               0      20     5.4              20
Permanent Ineff=
       F       F
#Block Obstruct= 2 , 0
                             5.4
Bank Sta=0,5.4
XS Rating Curve= 0
Exp/Cntr=.3,.1

Type RM Length L Ch R = 1 ,28.013  ,13,13,13
#Sta/Elev= 11
   -12.5      16    -2.5      16     -.5    17.5       0    17.5     1.2    16.8
     1.5    16.6     2.7    16.6     4.3    18.2     4.8    18.2     5.1      18
    15.1      18
#Mann= 3 , 0 , 0
   -12.5    .035       0       0    .035       0     4.3    .035       0
#XS Ineff= 2 , 0
               0      20     4.3              20
Permanent Ineff=
       F       F
#Block Obstruct= 2 , 0
                             4.3
Bank Sta=0,4.3
XS Rating Curve= 0
Exp/Cntr=.3,.1

Type RM Length L Ch R = 1 ,28      ,50,50,50
#Sta/Elev= 10
   -12.5   16.92    -2.5   16.92     -.5   18.42       0   18.42     2.4   16.22
     3.6   16.22     5.2   17.82     5.7   17.82       6   17.62      16   17.62
#Mann= 3 , 0 , 0
   -12.5    .035       0       0    .035       0     5.2    .035       0
#XS Ineff= 2 , 0
               0      20     5.2              20
Permanent Ineff=
       F       F
#Block Obstruct= 2 , 0
                             5.2
Bank Sta=0,5.2
XS Rating Curve= 0
Exp/Cntr=.3,.1

Type RM Length L Ch R = 1 ,27      ,6,6,6
#Sta/Elev= 8
     -10    17.5       0    17.5     1.4    15.6     2.4    15.6     4.6    17.6
     5.2    17.6     7.2    16.4    17.2    16.4
#Mann= 3 , 0 , 0
     -10    .035       0       0    .035       0     4.6    .035       0
#XS Ineff= 2 , 0
               0      20     4.6              20
Permanent Ineff=
       F       F
#Block Obstruct= 2 , 0
                             4.6
Bank Sta=0,4.6
XS Rating Curve= 0
Exp/Cntr=.3,.1

Type RM Length L Ch R = 1 ,26.044  ,44,44,44
#Sta/Elev= 8
     -10   16.55       0   16.55     1.4   14.65     2.4   14.65     4.6   16.65
     5.2   16.65     7.2   15.45    17.2   15.45
#Mann= 3 , 0 , 0
     -10    .035       0       0    .035       0     4.6    .035       0
#XS Ineff= 2 , 0
               0      20     4.6              20
Permanent Ineff=
       F       F
#Block Obstruct= 2 , 0
                             4.6
Bank Sta=0,4.6
XS Rating Curve= 0
Exp/Cntr=.3,.1

Type RM Length L Ch R = 1 ,26      ,23,23,23
#Sta/Elev= 12
     -10   15.79       0   15.79      .6   15.49      .6   13.79     1.4   13.79
     2.2   14.29       4   14.79       6   16.19     7.6   17.19     8.3   17.19
     9.9   15.79    19.9   15.79
#Mann= 3 , 0 , 0
     -10    .035       0       0    .035       0     7.6    .035       0
#XS Ineff= 2 , 0
               0      20     7.6              20
Permanent Ineff=
       F       F
#Block Obstruct= 2 , 0
                             7.6
Bank Sta=0,7.6
XS Rating Curve= 0
Exp/Cntr=.3,.1

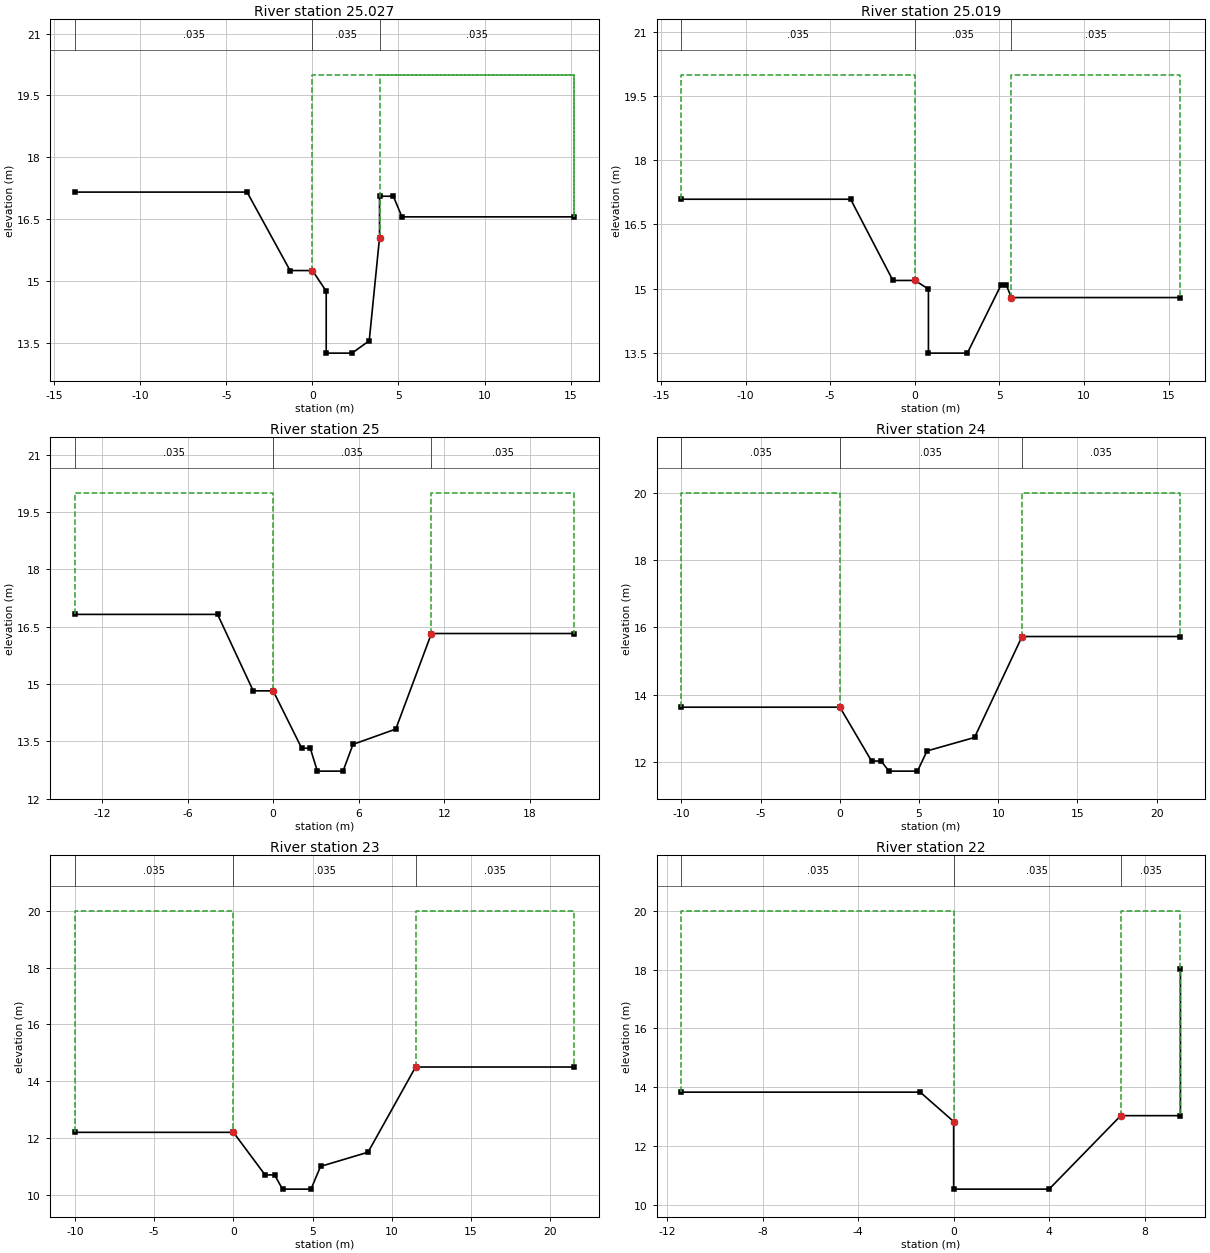
Type RM Length L Ch R = 1 ,25.027  ,8,8,8
#Sta/Elev= 13
   -13.8   17.16    -3.8   17.16    -1.3   15.26       0   15.26      .8   14.76
      .8   13.26     2.3   13.26     3.3   13.56     3.9   16.06     3.9   17.06
     4.7   17.06     5.2   16.56    15.2   16.56
#Mann= 3 , 0 , 0
   -13.8    .035       0       0    .035       0     3.9    .035       0
#XS Ineff= 2 , 0
       0       0      20     3.9       0      20
Permanent Ineff=
       F       F
#Block Obstruct= 2 , 0
       0                     3.9       0
Bank Sta=0,3.9
XS Rating Curve= 0
Exp/Cntr=.3,.1

Type RM Length L Ch R = 1 ,25.019  ,19,19,19
#Sta/Elev= 11
   -13.8   17.09    -3.8   17.09    -1.3   15.19       0   15.19      .8   14.99
      .8   13.49     3.1   13.49     5.1   15.09     5.4   15.09     5.7   14.79
    15.7   14.79
#Mann= 3 , 0 , 0
   -13.8    .035       0       0    .035       0     5.7    .035       0
#XS Ineff= 2 , 0
               0      20     5.7              20
Permanent Ineff=
       F       F
#Block Obstruct= 2 , 0
                             5.7
Bank Sta=0,5.7
XS Rating Curve= 0
Exp/Cntr=.3,.1

Type RM Length L Ch R = 1 ,25      ,50,50,50
#Sta/Elev= 12
   -13.9   16.82    -3.9   16.82    -1.4   14.82       0   14.82       2   13.32
     2.6   13.32     3.1   12.72     4.9   12.72     5.6   13.42     8.6   13.82
    11.1   16.32    21.1   16.32
#Mann= 3 , 0 , 0
   -13.9    .035       0       0    .035       0    11.1    .035       0
#XS Ineff= 2 , 0
               0      20    11.1              20
Permanent Ineff=
       F       F
#Block Obstruct= 2 , 0
                            11.1
Bank Sta=0,11.1
XS Rating Curve= 0
Exp/Cntr=.3,.1

Type RM Length L Ch R = 1 ,24      ,50,50,50
#Sta/Elev= 10
     -10   13.63       0   13.63       2   12.03     2.6   12.03     3.1   11.73
     4.9   11.73     5.5   12.33     8.5   12.73    11.5   15.73    21.5   15.73
#Mann= 3 , 0 , 0
     -10    .035       0       0    .035       0    11.5    .035       0
#XS Ineff= 2 , 0
               0      20    11.5              20
Permanent Ineff=
       F       F
#Block Obstruct= 2 , 0
                            11.5
Bank Sta=0,11.5
XS Rating Curve= 0
Exp/Cntr=.3,.1

Type RM Length L Ch R = 1 ,23      ,50,50,50
#Sta/Elev= 10
     -10    12.2       0    12.2       2    10.7     2.6    10.7     3.1    10.2
     4.9    10.2     5.5      11     8.5    11.5    11.5    14.5    21.5    14.5
#Mann= 3 , 0 , 0
     -10    .035       0       0    .035       0    11.5    .035       0
#XS Ineff= 2 , 0
               0      20    11.5              20
Permanent Ineff=
       F       F
#Block Obstruct= 2 , 0
                            11.5
Bank Sta=0,11.5
XS Rating Curve= 0
Exp/Cntr=.3,.1

Type RM Length L Ch R = 1 ,22      ,3,3,3
#Sta/Elev= 8
   -11.4   13.83    -1.4   13.83       0   12.83       0   10.53       4   10.53
       7   13.03     9.5   13.03     9.5   18.03
#Mann= 3 , 0 , 0
   -11.4    .035       0       0    .035       0       7    .035       0
#XS Ineff= 2 , 0
               0      20       7              20
Permanent Ineff=
       F       F
#Block Obstruct= 2 , 0
                               7
Bank Sta=0,7
XS Rating Curve= 0
Exp/Cntr=.3,.1

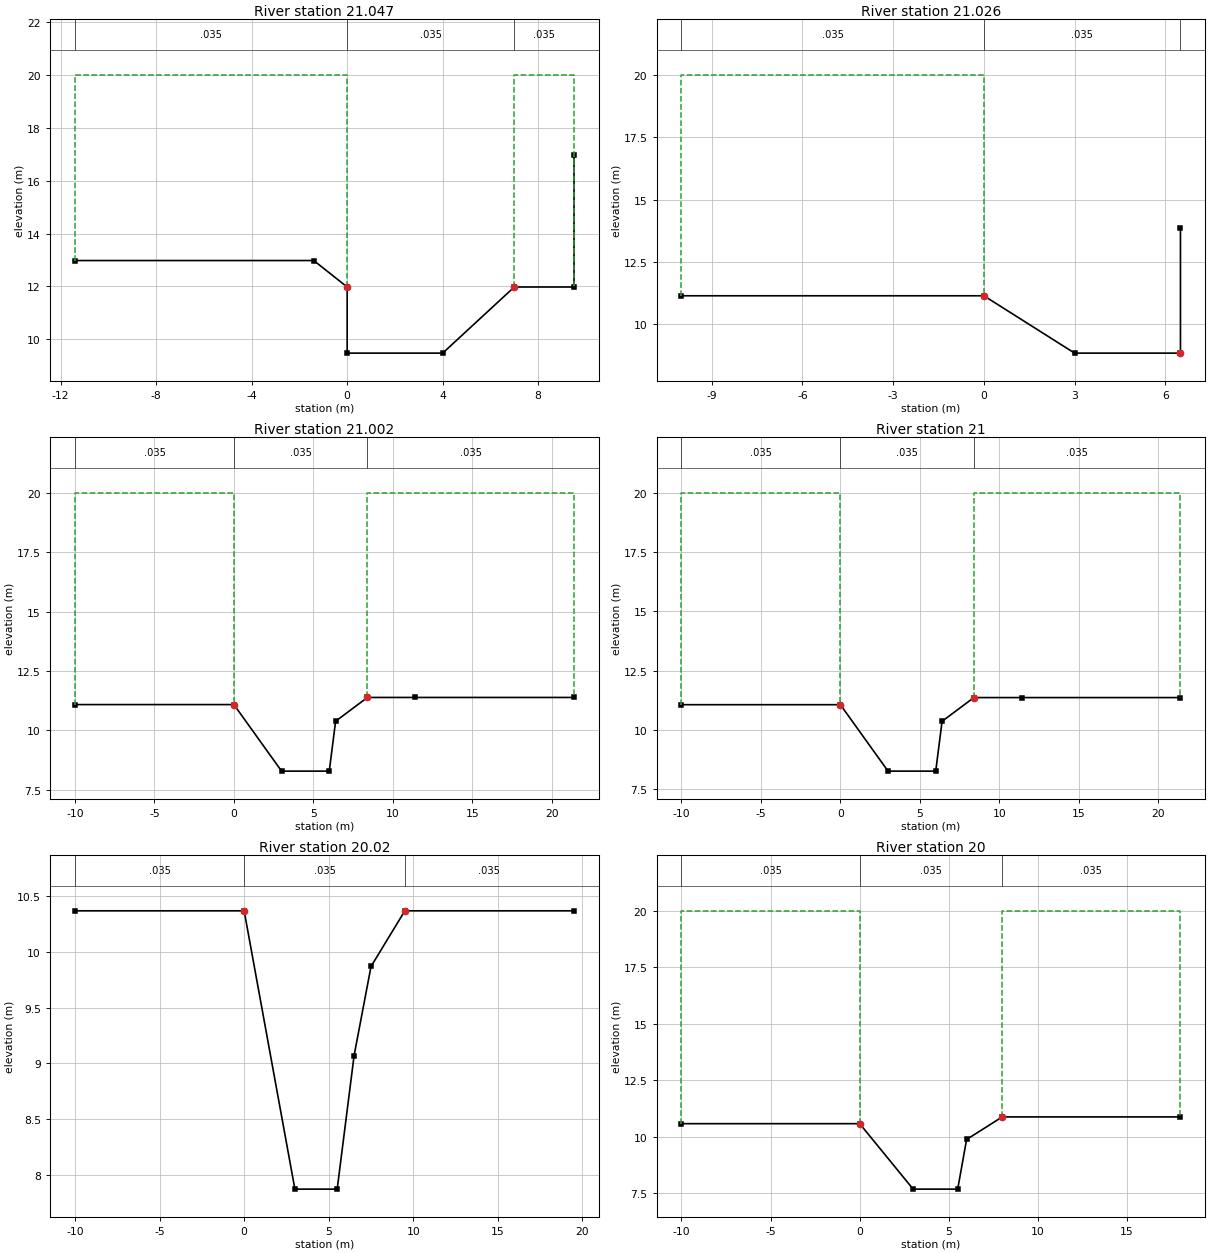
Type RM Length L Ch R = 1 ,21.047  ,21,21,21
#Sta/Elev= 8
   -11.4   12.98    -1.4   12.98       0   11.98       0    9.48       4    9.48
       7   11.98     9.5   11.98     9.5   16.98
#Mann= 3 , 0 , 0
   -11.4    .035       0       0    .035       0       7    .035       0
#XS Ineff= 2 , 0
               0      20       7              20
Permanent Ineff=
       F       F
#Block Obstruct= 2 , 0
                               7
Bank Sta=0,7
XS Rating Curve= 0
Exp/Cntr=.3,.1

Type RM Length L Ch R = 1 ,21.026  ,24,24,24
#Sta/Elev= 5
     -10   11.14       0   11.14       3    8.84     6.5    8.84     6.5   13.84
#Mann= 3 , 0 , 0
     -10    .035       0       0    .035       0     6.5    .035       0
#XS Ineff= 2 , 0
               0      20     6.5              20
Permanent Ineff=
       F       F
#Block Obstruct= 2 , 0
                             6.5
Bank Sta=0,6.5
XS Rating Curve= 0
Exp/Cntr=.3,.1

Type RM Length L Ch R = 1 ,21.002  ,2,2,2
#Sta/Elev= 8
     -10   11.09       0   11.09       3    8.29       6    8.29     6.4   10.39
     8.4   11.39    11.4   11.39    21.4   11.39
#Mann= 3 , 0 , 0
     -10    .035       0       0    .035       0     8.4    .035       0
#XS Ineff= 2 , 0
               0      20     8.4              20
Permanent Ineff=
       F       F
#Block Obstruct= 2 , 0
                             8.4
Bank Sta=0,8.4
XS Rating Curve= 0
Exp/Cntr=.3,.1

Type RM Length L Ch R = 1 ,21      ,30,30,30
#Sta/Elev= 8
     -10   11.07       0   11.07       3    8.27       6    8.27     6.4   10.37
     8.4   11.37    11.4   11.37    21.4   11.37
#Mann= 3 , 0 , 0
     -10    .035       0       0    .035       0     8.4    .035       0
#XS Ineff= 2 , 0
               0      20     8.4              20
Permanent Ineff=
       F       F
#Block Obstruct= 2 , 0
                             8.4
Bank Sta=0,8.4
XS Rating Curve= 0
Exp/Cntr=.3,.1

Type RM Length L Ch R = 1 ,20.02   ,20,20,20
#Sta/Elev= 8
     -10   10.37       0   10.37       3    7.87     5.5    7.87     6.5    9.07
     7.5    9.87     9.5   10.37    19.5   10.37
#Mann= 3 , 0 , 0
     -10    .035       0       0    .035       0     9.5    .035       0
#XS Ineff= 2 , 0
               0      20     9.5              20
Permanent Ineff=
       F       F
#Block Obstruct= 2 , 0
                             9.5
Bank Sta=0,9.5
XS Rating Curve= 0
Exp/Cntr=.3,.1

Type RM Length L Ch R = 1 ,20      ,41,41,41
#Sta/Elev= 7
     -10   10.57       0   10.57       3    7.67     5.5    7.67       6    9.87
       8   10.87      18   10.87
#Mann= 3 , 0 , 0
     -10    .035       0       0    .035       0       8    .035       0
#XS Ineff= 2 , 0
               0      20       8              20
Permanent Ineff=
       F       F
#Block Obstruct= 2 , 0
                               8
Bank Sta=0,8
XS Rating Curve= 0
Exp/Cntr=.3,.1

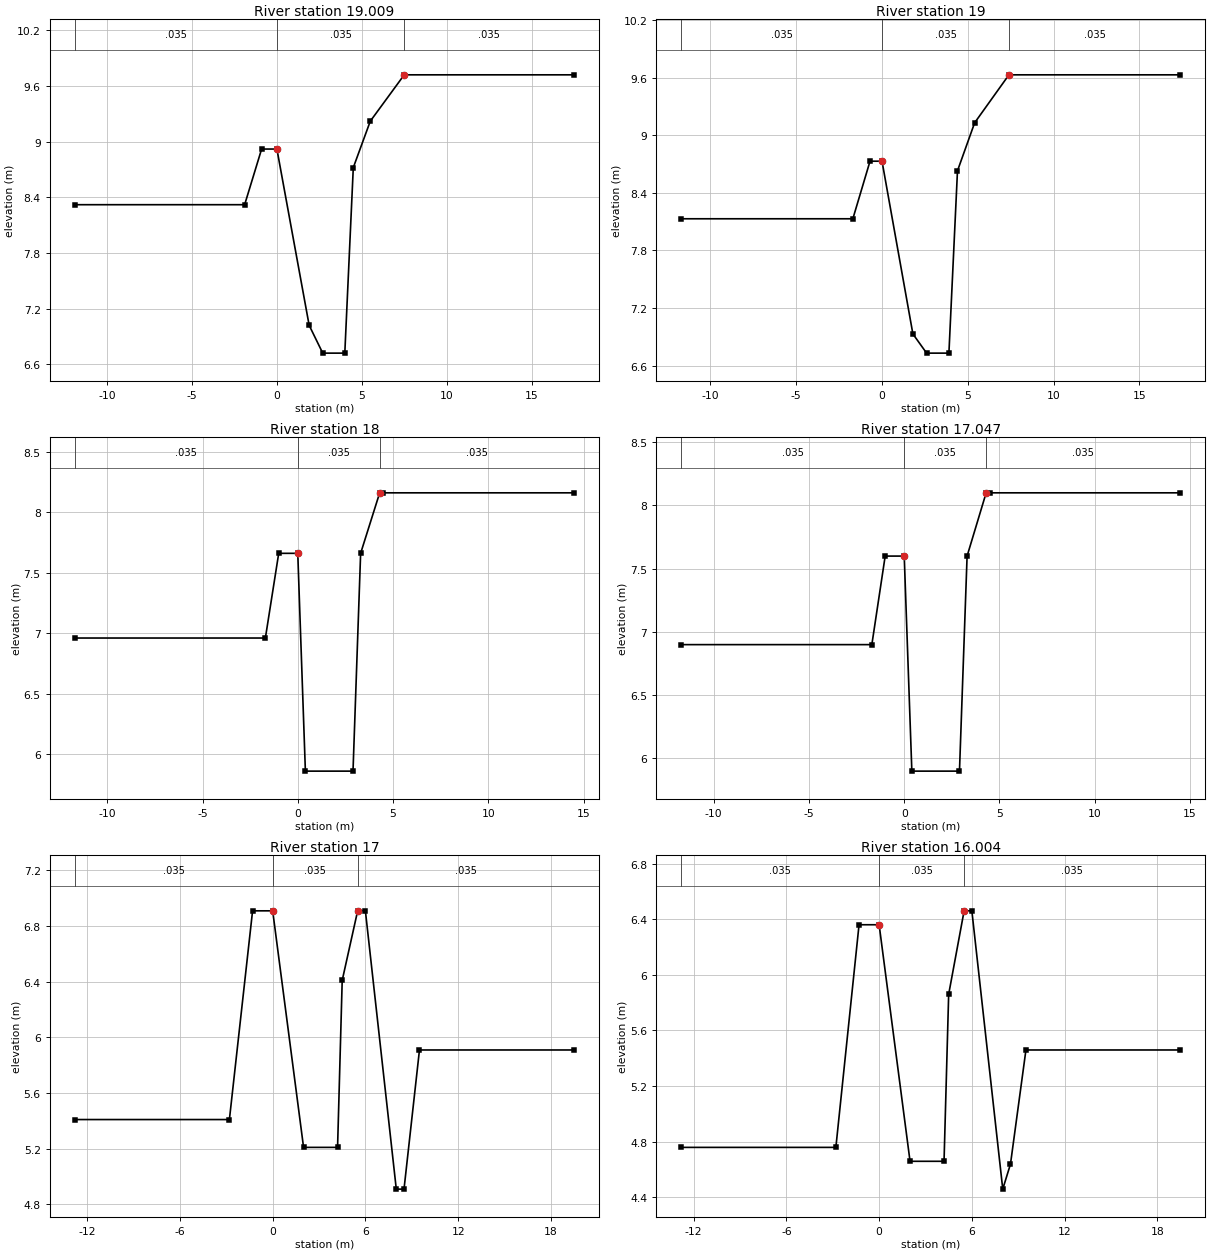
Type RM Length L Ch R = 1 ,19.009  ,9,9,9
#Sta/Elev= 11
   -11.9    8.32    -1.9    8.32     -.9    8.92       0    8.92     1.9    7.02
     2.7    6.72       4    6.72     4.5    8.72     5.5    9.22     7.5    9.72
    17.5    9.72
#Mann= 3 , 0 , 0
   -11.9    .035       0       0    .035       0     7.5    .035       0
#XS Ineff= 2 , 0
               0      20     7.5              20
Permanent Ineff=
       F       F
#Block Obstruct= 2 , 0
                             7.5
Bank Sta=0,7.5
XS Rating Curve= 0
Exp/Cntr=.3,.1

Type RM Length L Ch R = 1 ,19      ,50,50,50
#Sta/Elev= 11
   -11.7    8.13    -1.7    8.13     -.7    8.73       0    8.73     1.8    6.93
     2.6    6.73     3.9    6.73     4.4    8.63     5.4    9.13     7.4    9.63
    17.4    9.63
#Mann= 3 , 0 , 0
   -11.7    .035       0       0    .035       0     7.4    .035       0
#XS Ineff= 2 , 0
               0      20     7.4              20
Permanent Ineff=
       F       F
#Block Obstruct= 2 , 0
                             7.4
Bank Sta=0,7.4
XS Rating Curve= 0
Exp/Cntr=.3,.1

Type RM Length L Ch R = 1 ,18      ,3,3,3
#Sta/Elev= 10
   -11.7    6.96    -1.7    6.96      -1    7.66       0    7.66      .4    5.86
     2.9    5.86     3.3    7.66     4.3    8.16     4.5    8.16    14.5    8.16
#Mann= 3 , 0 , 0
   -11.7    .035       0       0    .035       0     4.3    .035       0
#XS Ineff= 2 , 0
               0      20     4.3              20
Permanent Ineff=
       F       F
#Block Obstruct= 2 , 0
                             4.3
Bank Sta=0,4.3
XS Rating Curve= 0
Exp/Cntr=.3,.1

Type RM Length L Ch R = 1 ,17.047  ,47,47,47
#Sta/Elev= 10
   -11.7     6.9    -1.7     6.9      -1     7.6       0     7.6      .4     5.9
     2.9     5.9     3.3     7.6     4.3     8.1     4.5     8.1    14.5     8.1
#Mann= 3 , 0 , 0
   -11.7    .035       0       0    .035       0     4.3    .035       0
#XS Ineff= 2 , 0
               0      20     4.3              20
Permanent Ineff=
       F       F
#Block Obstruct= 2 , 0
                             4.3
Bank Sta=0,4.3
XS Rating Curve= 0
Exp/Cntr=.3,.1

Type RM Length L Ch R = 1 ,17      ,46,46,46
#Sta/Elev= 13
   -12.8    5.41    -2.8    5.41    -1.3    6.91       0    6.91       2    5.21
     4.2    5.21     4.5    6.41     5.5    6.91       6    6.91       8    4.91
     8.5    4.91     9.5    5.91    19.5    5.91
#Mann= 3 , 0 , 0
   -12.8    .035       0       0    .035       0     5.5    .035       0
#XS Ineff= 2 , 0
               0      20     5.5              20
Permanent Ineff=
       F       F
#Block Obstruct= 2 , 0
                             5.5
Bank Sta=0,5.5
XS Rating Curve= 0
Exp/Cntr=.3,.1

Type RM Length L Ch R = 1 ,16.004  ,4,4,4
#Sta/Elev= 13
   -12.8    4.76    -2.8    4.76    -1.3    6.36       0    6.36       2    4.66
     4.2    4.66     4.5    5.86     5.5    6.46       6    6.46       8    4.46
     8.5    4.64     9.5    5.46    19.5    5.46
#Mann= 3 , 0 , 0
   -12.8    .035       0       0    .035       0     5.5    .035       0
#XS Ineff= 2 , 0
               0      20     5.5              20
Permanent Ineff=
       F       F
#Block Obstruct= 2 , 0
                             5.5
Bank Sta=0,5.5
XS Rating Curve= 0
Exp/Cntr=.3,.1

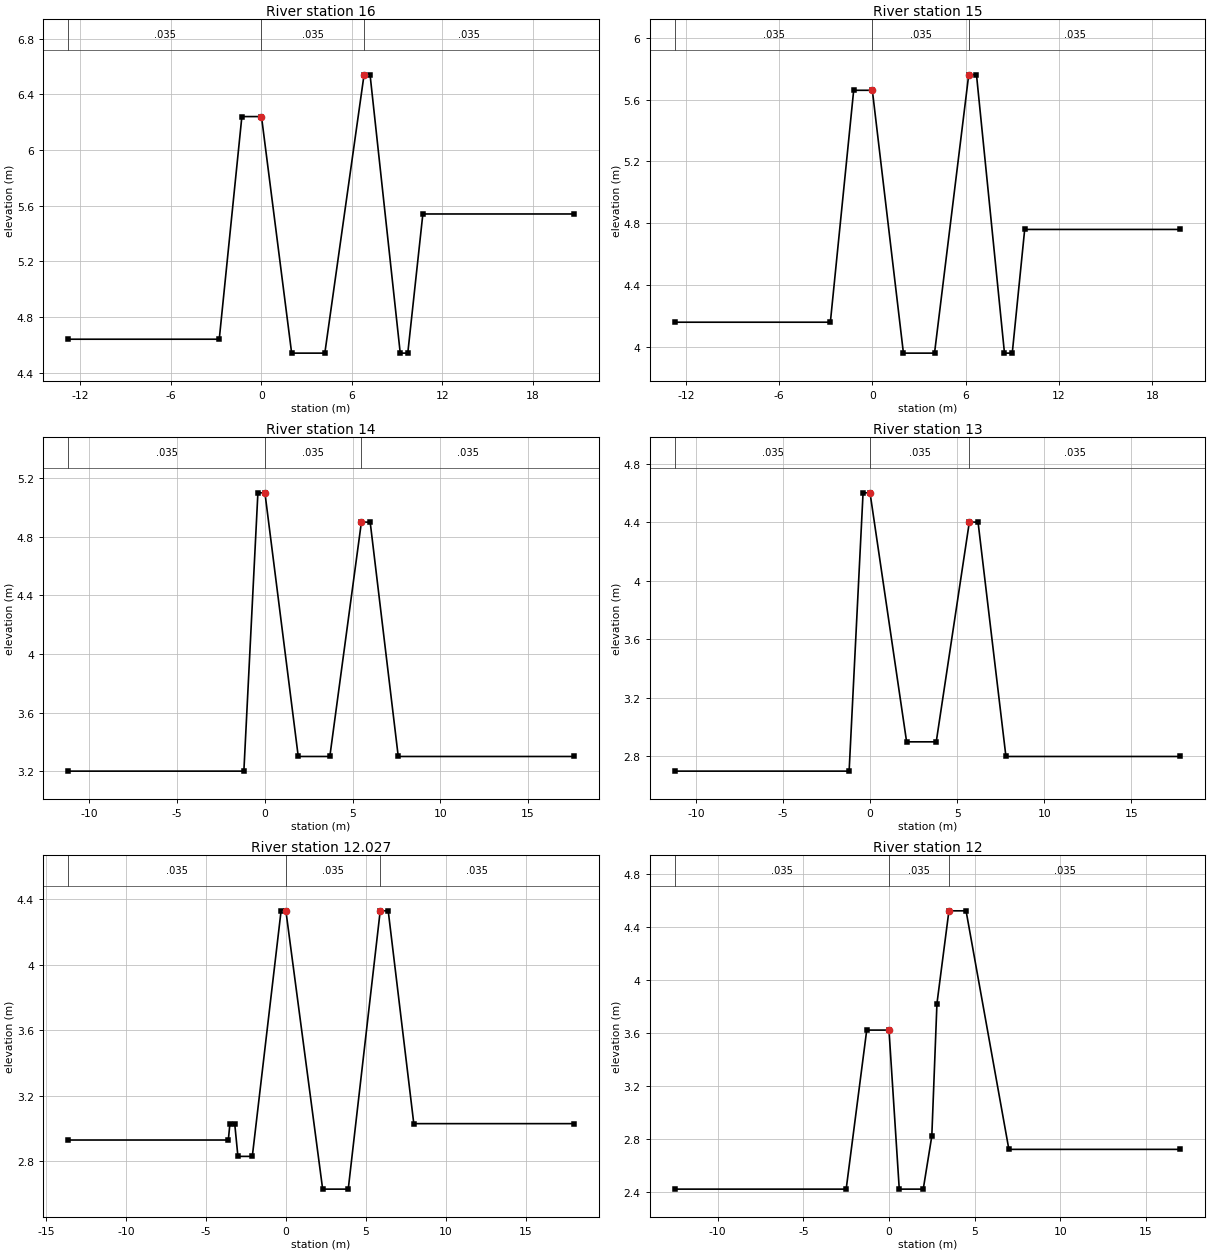
Type RM Length L Ch R = 1 ,16      ,50,50,50
#Sta/Elev= 12
   -12.8    4.64    -2.8    4.64    -1.3    6.24       0    6.24       2    4.54
     4.2    4.54     6.8    6.54     7.2    6.54     9.2    4.54     9.7    4.54
    10.7    5.54    20.7    5.54
#Mann= 3 , 0 , 0
   -12.8    .035       0       0    .035       0     6.8    .035       0
#XS Ineff= 2 , 0
               0      20     6.8              20
Permanent Ineff=
       F       F
#Block Obstruct= 2 , 0
                             6.8
Bank Sta=0,6.8
XS Rating Curve= 0
Exp/Cntr=.3,.1

Type RM Length L Ch R = 1 ,15      ,50,50,50
#Sta/Elev= 12
   -12.7    4.16    -2.7    4.16    -1.2    5.66       0    5.66       2    3.96
       4    3.96     6.2    5.76     6.7    5.76     8.5    3.96       9    3.96
     9.8    4.76    19.8    4.76
#Mann= 3 , 0 , 0
   -12.7    .035       0       0    .035       0     6.2    .035       0
#XS Ineff= 2 , 0
               0      20     6.2              20
Permanent Ineff=
       F       F
#Block Obstruct= 2 , 0
                             6.2
Bank Sta=0,6.2
XS Rating Curve= 0
Exp/Cntr=.3,.1

Type RM Length L Ch R = 1 ,14      ,50,50,50
#Sta/Elev= 10
   -11.2     3.2    -1.2     3.2     -.4     5.1       0     5.1     1.9     3.3
     3.7     3.3     5.5     4.9       6     4.9     7.6     3.3    17.6     3.3
#Mann= 3 , 0 , 0
   -11.2    .035       0       0    .035       0     5.5    .035       0
#XS Ineff= 2 , 0
               0      20     5.5              20
Permanent Ineff=
       F       F
#Block Obstruct= 2 , 0
                             5.5
Bank Sta=0,5.5
XS Rating Curve= 0
Exp/Cntr=.3,.1

Type RM Length L Ch R = 1 ,13      ,23,23,23
#Sta/Elev= 10
   -11.2     2.7    -1.2     2.7     -.4     4.6       0     4.6     2.1     2.9
     3.8     2.9     5.7     4.4     6.2     4.4     7.8     2.8    17.8     2.8
#Mann= 3 , 0 , 0
   -11.2    .035       0       0    .035       0     5.7    .035       0
#XS Ineff= 2 , 0
               0      20     5.7              20
Permanent Ineff=
       F       F
#Block Obstruct= 2 , 0
                             5.7
Bank Sta=0,5.7
XS Rating Curve= 0
Exp/Cntr=.3,.1

Type RM Length L Ch R = 1 ,12.027  ,27,27,27
#Sta/Elev= 14
   -13.6    2.93    -3.6    2.93    -3.5    3.03    -3.2    3.03      -3    2.83
    -2.1    2.83     -.3    4.33       0    4.33     2.3    2.63     3.9    2.63
     5.9    4.33     6.4    4.33       8    3.03      18    3.03
#Mann= 3 , 0 , 0
   -13.6    .035       0       0    .035       0     5.9    .035       0
#XS Ineff= 2 , 0
               0      20     5.9              20
Permanent Ineff=
       F       F
#Block Obstruct= 2 , 0
                             5.9
Bank Sta=0,5.9
XS Rating Curve= 0
Exp/Cntr=.3,.1

Type RM Length L Ch R = 1 ,12      ,37,37,37
#Sta/Elev= 12
   -12.5    2.42    -2.5    2.42    -1.3    3.62       0    3.62      .6    2.42
       2    2.42     2.5    2.82     2.8    3.82     3.5    4.52     4.5    4.52
       7    2.72      17    2.72
#Mann= 3 , 0 , 0
   -12.5    .035       0       0    .035       0     3.5    .035       0
#XS Ineff= 2 , 0
               0      20     3.5              20
Permanent Ineff=
       F       F
#Block Obstruct= 2 , 0
                             3.5
Bank Sta=0,3.5
XS Rating Curve= 0
Exp/Cntr=.3,.1