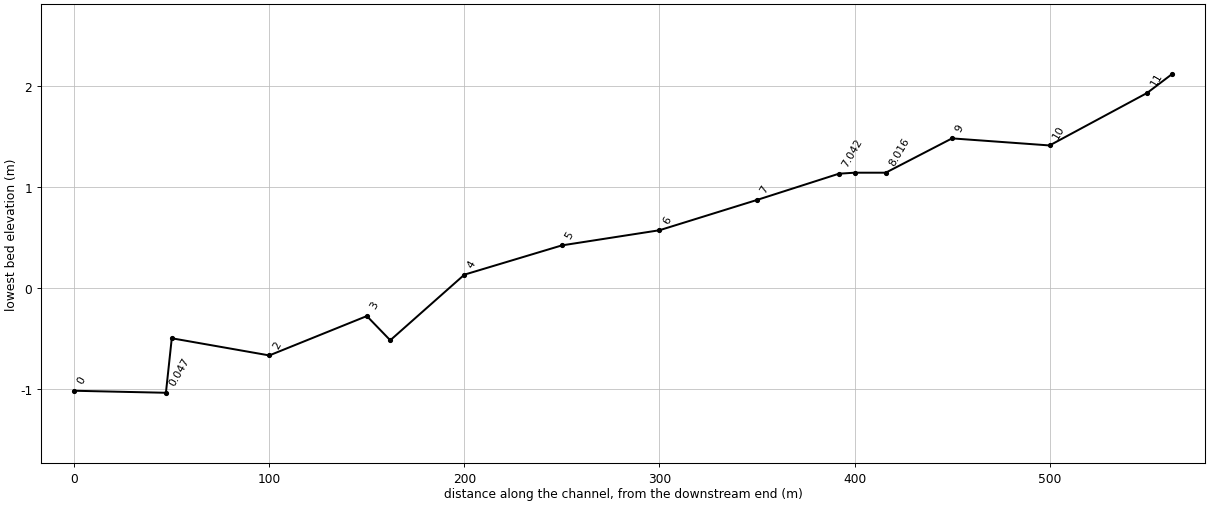
HEC-RAS study skr.prj: sikuri

--- skr.g01 (geometry) --- (continued)

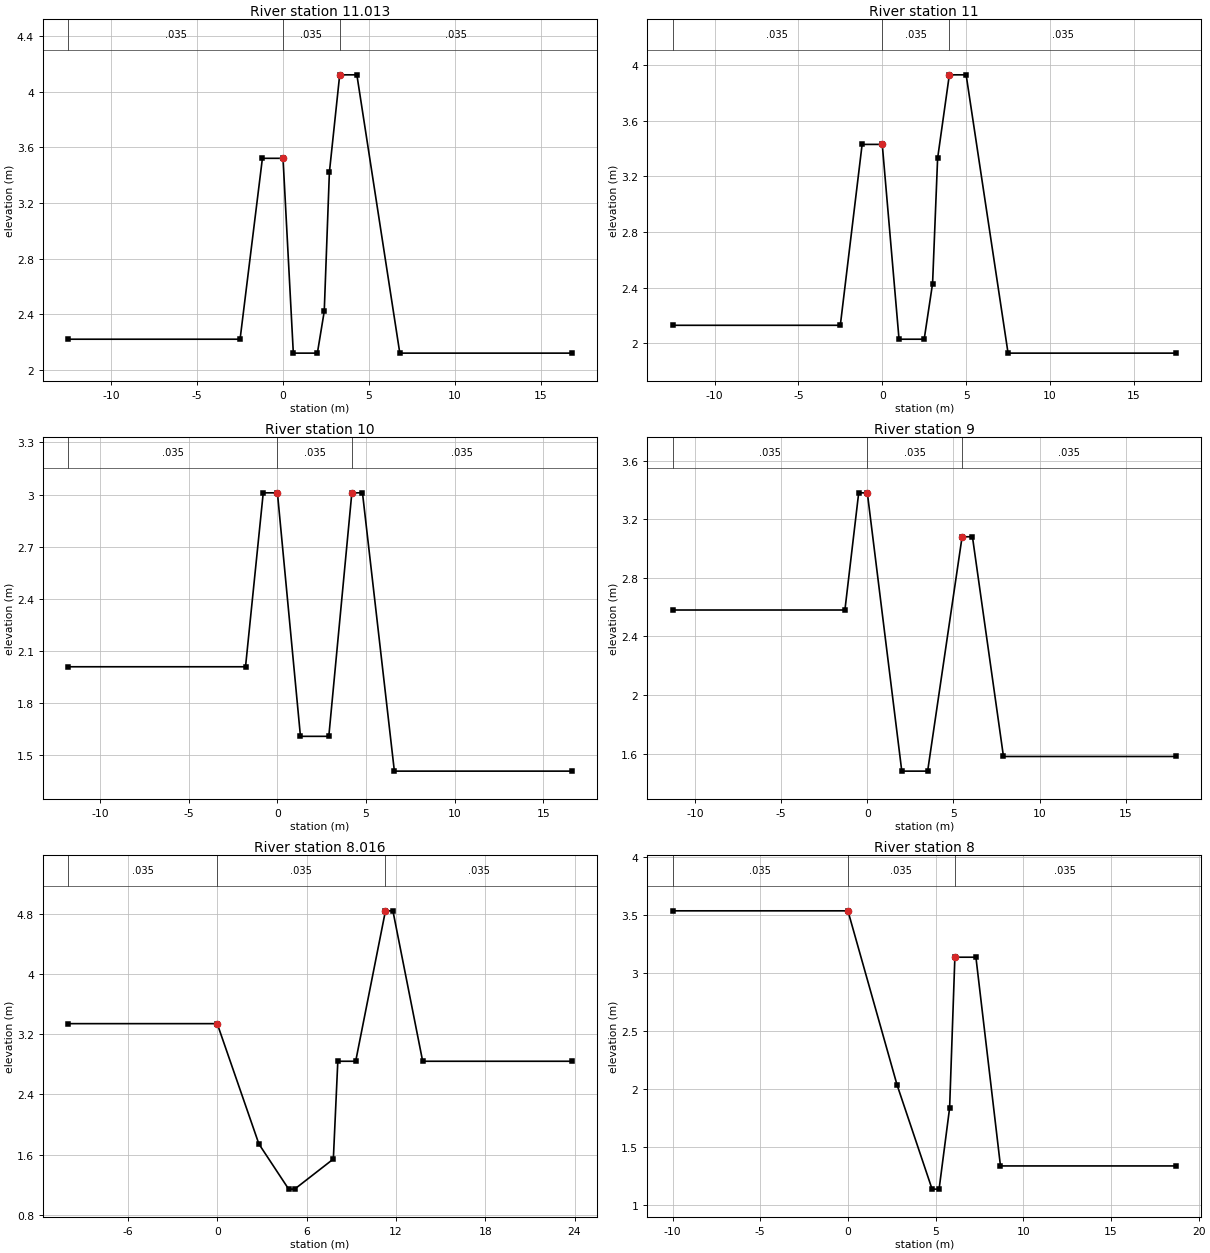
Type RM Length L Ch R = 1 ,11.013  ,13,13,13
#Sta/Elev= 12
   -12.5    2.22    -2.5    2.22    -1.2    3.52       0    3.52      .6    2.12
       2    2.12     2.4    2.42     2.7    3.42     3.3    4.12     4.3    4.12
     6.8    2.12    16.8    2.12
#Mann= 3 , 0 , 0
   -12.5    .035       0       0    .035       0     3.3    .035       0
#XS Ineff= 2 , 0
               0      20     3.3              20
Permanent Ineff=
       F       F
#Block Obstruct= 2 , 0
                             3.3
Bank Sta=0,3.3
XS Rating Curve= 0
Exp/Cntr=.3,.1

Type RM Length L Ch R = 1 ,11      ,50,50,50
#Sta/Elev= 12
   -12.5    2.13    -2.5    2.13    -1.2    3.43       0    3.43       1    2.03
     2.5    2.03       3    2.43     3.3    3.33       4    3.93       5    3.93
     7.5    1.93    17.5    1.93
#Mann= 3 , 0 , 0
   -12.5    .035       0       0    .035       0       4    .035       0
#XS Ineff= 2 , 0
               0      20       4              20
Permanent Ineff=
       F       F
#Block Obstruct= 2 , 0
                               4
Bank Sta=0,4
XS Rating Curve= 0
Exp/Cntr=.3,.1

Type RM Length L Ch R = 1 ,10      ,50,50,50
#Sta/Elev= 10
   -11.8    2.01    -1.8    2.01     -.8    3.01       0    3.01     1.3    1.61
     2.9    1.61     4.2    3.01     4.8    3.01     6.6    1.41    16.6    1.41
#Mann= 3 , 0 , 0
   -11.8    .035       0       0    .035       0     4.2    .035       0
#XS Ineff= 2 , 0
               0      20     4.2              20
Permanent Ineff=
       F       F
#Block Obstruct= 2 , 0
                             4.2
Bank Sta=0,4.2
XS Rating Curve= 0
Exp/Cntr=.3,.1

Type RM Length L Ch R = 1 ,9       ,34,34,34
#Sta/Elev= 10
   -11.3    2.58    -1.3    2.58     -.5    3.38       0    3.38       2    1.48
     3.5    1.48     5.5    3.08     6.1    3.08     7.9    1.58    17.9    1.58
#Mann= 3 , 0 , 0
   -11.3    .035       0       0    .035       0     5.5    .035       0
#XS Ineff= 2 , 0
               0      20     5.5              20
Permanent Ineff=
       F       F
#Block Obstruct= 2 , 0
                             5.5
Bank Sta=0,5.5
XS Rating Curve= 0
Exp/Cntr=.3,.1

Type RM Length L Ch R = 1 ,8.016   ,16,16,16
#Sta/Elev= 12
     -10    3.34       0    3.34     2.8    1.74     4.8    1.14     5.2    1.14
     7.8    1.54     8.1    2.84     9.3    2.84    11.3    4.84    11.8    4.84
    13.8    2.84    23.8    2.84
#Mann= 3 , 0 , 0
     -10    .035       0       0    .035       0    11.3    .035       0
#XS Ineff= 2 , 0
               0      20    11.3              20
Permanent Ineff=
       F       F
#Block Obstruct= 2 , 0
                            11.3
Bank Sta=0,11.3
XS Rating Curve= 0
Exp/Cntr=.3,.1

Type RM Length L Ch R = 1 ,8       ,8,8,8
#Sta/Elev= 10
     -10    3.54       0    3.54     2.8    2.04     4.8    1.14     5.2    1.14
     5.8    1.84     6.1    3.14     7.3    3.14     8.7    1.34    18.7    1.34
#Mann= 3 , 0 , 0
     -10    .035       0       0    .035       0     6.1    .035       0
#XS Ineff= 2 , 0
               0      20     6.1              20
Permanent Ineff=
       F       F
#Block Obstruct= 2 , 0
                             6.1
Bank Sta=0,6.1
XS Rating Curve= 0
Exp/Cntr=.3,.1

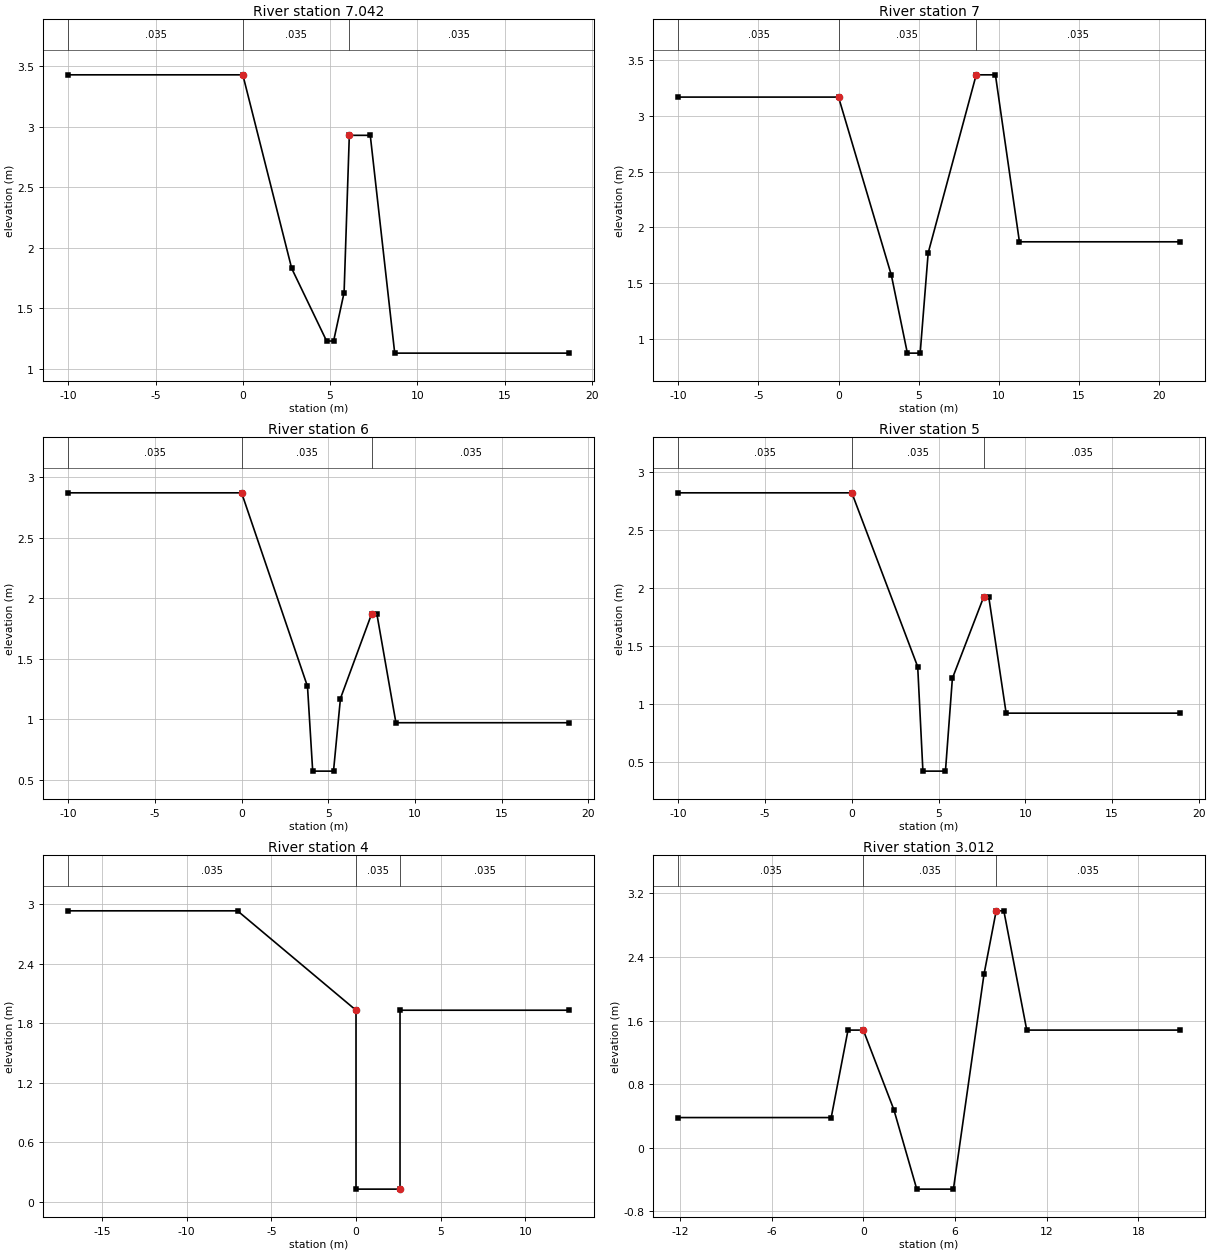
Type RM Length L Ch R = 1 ,7.042   ,42,42,42
#Sta/Elev= 10
     -10    3.43       0    3.43     2.8    1.83     4.8    1.23     5.2    1.23
     5.8    1.63     6.1    2.93     7.3    2.93     8.7    1.13    18.7    1.13
#Mann= 3 , 0 , 0
     -10    .035       0       0    .035       0     6.1    .035       0
#XS Ineff= 2 , 0
               0      20     6.1              20
Permanent Ineff=
       F       F
#Block Obstruct= 2 , 0
                             6.1
Bank Sta=0,6.1
XS Rating Curve= 0
Exp/Cntr=.3,.1

Type RM Length L Ch R = 1 ,7       ,50,50,50
#Sta/Elev= 10
     -10    3.17       0    3.17     3.3    1.57     4.3     .87     5.1     .87
     5.6    1.77     8.6    3.37     9.8    3.37    11.3    1.87    21.3    1.87
#Mann= 3 , 0 , 0
     -10    .035       0       0    .035       0     8.6    .035       0
#XS Ineff= 2 , 0
               0      20     8.6              20
Permanent Ineff=
       F       F
#Block Obstruct= 2 , 0
                             8.6
Bank Sta=0,8.6
XS Rating Curve= 0
Exp/Cntr=.3,.1

Type RM Length L Ch R = 1 ,6       ,50,50,50
#Sta/Elev= 10
     -10    2.87       0    2.87     3.8    1.27     4.1     .57     5.3     .57
     5.7    1.17     7.5    1.87     7.8    1.87     8.9     .97    18.9     .97
#Mann= 3 , 0 , 0
     -10    .035       0       0    .035       0     7.5    .035       0
#XS Ineff= 2 , 0
               0      20     7.5              20
Permanent Ineff=
       F       F
#Block Obstruct= 2 , 0
                             7.5
Bank Sta=0,7.5
XS Rating Curve= 0
Exp/Cntr=.3,.1

Type RM Length L Ch R = 1 ,5       ,50,50,50
#Sta/Elev= 10
     -10    2.82       0    2.82     3.8    1.32     4.1     .42     5.4     .42
     5.8    1.22     7.6    1.92     7.9    1.92     8.9     .92    18.9     .92
#Mann= 3 , 0 , 0
     -10    .035       0       0    .035       0     7.6    .035       0
#XS Ineff= 2 , 0
               0      20     7.6              20
Permanent Ineff=
       F       F
#Block Obstruct= 2 , 0
                             7.6
Bank Sta=0,7.6
XS Rating Curve= 0
Exp/Cntr=.3,.1

Type RM Length L Ch R = 1 ,4       ,38,38,38
#Sta/Elev= 7
     -17    2.93      -7    2.93       0    1.93       0     .13     2.6     .13
     2.6    1.93    12.6    1.93
#Mann= 3 , 0 , 0
     -17    .035       0       0    .035       0     2.6    .035       0
#XS Ineff= 2 , 0
               0      20     2.6              20
Permanent Ineff=
       F       F
#Block Obstruct= 2 , 0
                             7.6
Bank Sta=0,2.6
XS Rating Curve= 0
Exp/Cntr=.3,.1

Type RM Length L Ch R = 1 ,3.012   ,12,12,12
#Sta/Elev= 12
   -12.1     .38    -2.1     .38      -1    1.48       0    1.48       2     .48
     3.5    -.52     5.9    -.52     7.9    2.18     8.7    2.98     9.2    2.98
    10.7    1.48    20.7    1.48
#Mann= 3 , 0 , 0
   -12.1    .035       0       0    .035       0     8.7    .035       0
#XS Ineff= 2 , 0
       0       0      20     8.7       0      20
Permanent Ineff=
       F       F
#Block Obstruct= 2 , 0
       0                     8.7       0
Bank Sta=0,8.7
XS Rating Curve= 0
Exp/Cntr=.3,.1

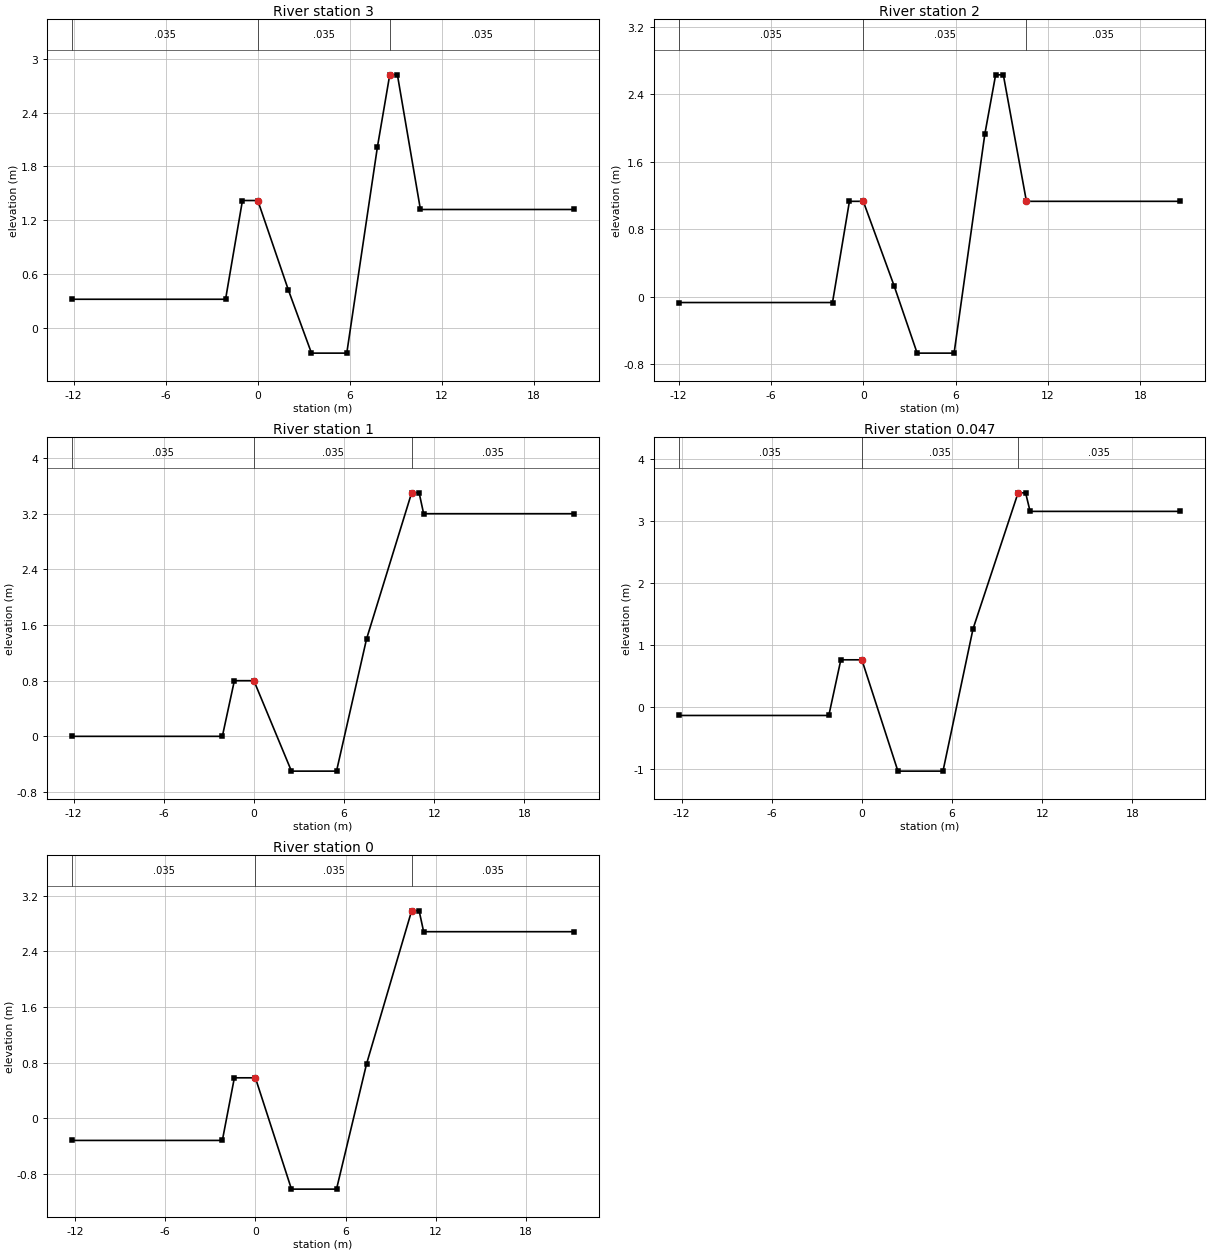
Type RM Length L Ch R = 1 ,3       ,50,50,50
#Sta/Elev= 12
   -12.1     .32    -2.1     .32      -1    1.42       0    1.42       2     .42
     3.5    -.28     5.8    -.28     7.8    2.02     8.6    2.82     9.1    2.82
    10.6    1.32    20.6    1.32
#Mann= 3 , 0 , 0
   -12.1    .035       0       0    .035       0     8.6    .035       0
#XS Ineff= 2 , 0
               0      20     8.6              20
Permanent Ineff=
       F       F
#Block Obstruct= 2 , 0
                             8.6
Bank Sta=0,8.6
XS Rating Curve= 0
Exp/Cntr=.3,.1

Type RM Length L Ch R = 1 ,2       ,50,50,50
#Sta/Elev= 12
     -12    -.07      -2    -.07     -.9    1.13       0    1.13       2     .13
     3.5    -.67     5.9    -.67     7.9    1.93     8.6    2.63     9.1    2.63
    10.6    1.13    20.6    1.13
#Mann= 3 , 0 , 0
     -12    .035       0       0    .035       0    10.6    .035       0
#XS Ineff= 2 , 0
               0      20    10.6              20
Permanent Ineff=
       F       F
#Block Obstruct= 2 , 0
                            10.6
Bank Sta=0,10.6
XS Rating Curve= 0
Exp/Cntr=.3,.1

Type RM Length L Ch R = 1 ,1       ,3,3,3
#Sta/Elev= 11
   -12.1       0    -2.1       0    -1.3      .8       0      .8     2.5     -.5
     5.5     -.5     7.5     1.4    10.5     3.5      11     3.5    11.3     3.2
    21.3     3.2
#Mann= 3 , 0 , 0
   -12.1    .035       0       0    .035       0    10.5    .035       0
#XS Ineff= 2 , 0
               0      20    10.5              20
Permanent Ineff=
       F       F
#Block Obstruct= 2 , 0
                            10.5
Bank Sta=0,10.5
XS Rating Curve= 0
Exp/Cntr=.3,.1

Type RM Length L Ch R = 1 ,0.047   ,47,47,47
#Sta/Elev= 11
   -12.2    -.14    -2.2    -.14    -1.4     .76       0     .76     2.4   -1.04
     5.4   -1.04     7.4    1.26    10.4    3.46    10.9    3.46    11.2    3.16
    21.2    3.16
#Mann= 3 , 0 , 0
   -12.2    .035       0       0    .035       0    10.4    .035       0
#XS Ineff= 2 , 0
               0      20    10.4              20
Permanent Ineff=
       F       F
#Block Obstruct= 2 , 0
                            10.4
Bank Sta=0,10.4
XS Rating Curve= 0
Exp/Cntr=.3,.1

Type RM Length L Ch R = 1 ,0       ,0,0,0
#Sta/Elev= 11
   -12.2    -.32    -2.2    -.32    -1.4     .58       0     .58     2.4   -1.02
     5.4   -1.02     7.4     .78    10.4    2.98    10.9    2.98    11.2    2.68
    21.2    2.68
#Mann= 3 , 0 , 0
   -12.2    .035       0       0    .035       0    10.4    .035       0
#XS Ineff= 2 , 0
               0      20    10.4              20
Permanent Ineff=
       F       F
#Block Obstruct= 2 , 0
                            10.4
Bank Sta=0,10.4
XS Rating Curve= 0
Exp/Cntr=.3,.1

Chan Stop Cuts=-1