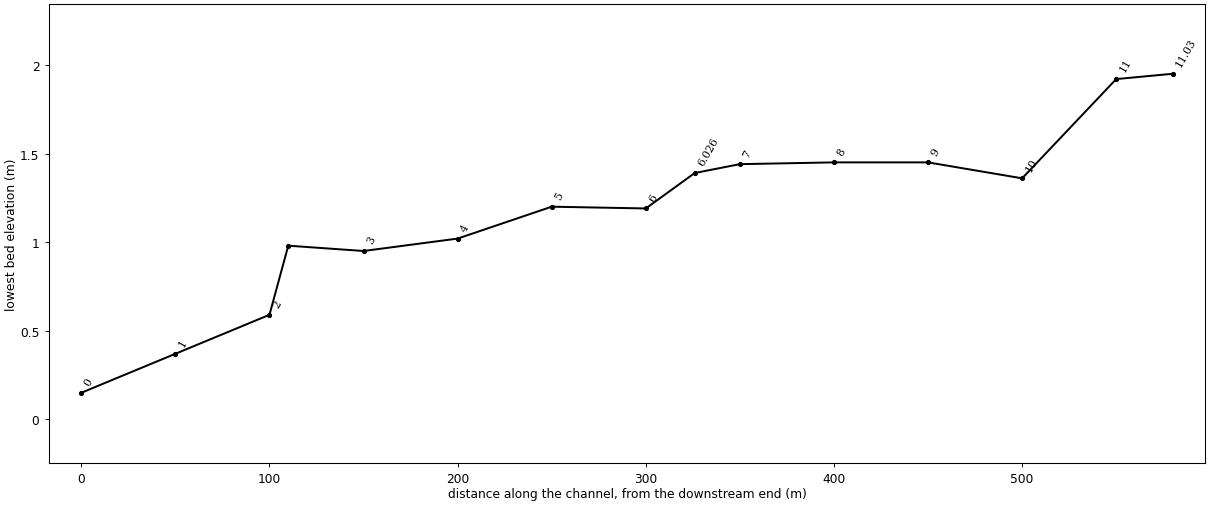
--- gomandol-ch.prj (project) ---

Proj Title=gomandol-ch
Current Plan=p01
Default Exp/Contr=.3,.1
SI Units
Geom File=g01
Flow File=f01
Plan File=p01
Y Axis Title=Elevation
X Axis Title(PF)=Main Channel Distance
X Axis Title(XS)=Station
BEGIN DESCRIPTION:
           BACK WATER COMPUTATION
      APPLICATION OF HEC-2 BY Samju Construction Engineering
      gomandol-ch: 10,20,30,50,80 yr
END DESCRIPTION:
DSS Export Rating Curves= 0
DSS Export Rating Curve Sorted= 0
DSS Export Volume Flow Curves= 0
DXF OffsetX= 0
DXF OffsetY= 0
DXF ScaleX= 1
DXF ScaleY= 10

--- gomandol-ch.p01 (plan) ---

Plan Title=Imported Plan 01
Version=Version 3.0.1  Mar 2001
Short Identifier=Imported Pla
Geom File=g01
Flow File=f01
Subcritical Flow
K Sum by GR= 0
Std Step Tol= 0.003
Critical Tol= 0.003
Num of Std Step Trials= 20
Max Error Tol= 0.1
Flow Tol Ratio= 0.001
Split Flow NTrial= 30
Split Flow Tol= 0.02
Split Flow Ratio= 0.02
Log Output Level= 0
Friction Slope Method= 1
Unsteady Friction Slope Method= 2
Parabolic Critical Depth
Global Vel Dist= 0 , 0 , 0
Global Log Level= 0
CheckData=True
Encroach Param=-1 ,0,0, 0
Computation Interval=1HOUR
Output Interval=1HOUR
Run HTab= 0
Run UNet= 0
Run PostProcess= 0
UNET Theta= 1
UNET ZTol= 0.02
UNET ZSATol= 0.1
UNET MxIter= 20
UNET MaxInSteps= 20
UNET DtIC= 0
UNET DtMin= 0
UNET MaxCRTS= 20
UNET WFStab= 2
UNET SFStab= 1
UNET WFX= 1
UNET SFX= 1
UNET Convert EG Bridges=-1
UNET Use Existing IB Tables=-1
Instantaneous Interval=1HOUR
Write IC File= 0
Write Velocity= 0
Write Detailed= 0

--- gomandol-ch.f01 (steady flow) ---

Flow Title=Imported Flow 01
Version=Version 3.0.1  Mar 2001
Number of Profiles= 5
Profile Names=PF 1,PF 2,PF 3,PF 4,PF 5
River Rch & RM=RIVER-1,Reach-1         ,11.03
     180     200     220     230     240
River Rch & RM=GOMANDOL,GOMANDOL        ,11.03
     180     200     220     230     240
Boundary for River Rch & Prof#=GOMANDOL,GOMANDOL        , 1
Up Type= 0
Dn Type= 3
Dn Slope=.0109
Boundary for River Rch & Prof#=GOMANDOL,GOMANDOL        , 2
Up Type= 0
Dn Type= 3
Dn Slope=.0109
Boundary for River Rch & Prof#=GOMANDOL,GOMANDOL        , 3
Up Type= 0
Dn Type= 3
Dn Slope=.0109
Boundary for River Rch & Prof#=GOMANDOL,GOMANDOL        , 4
Up Type= 0
Dn Type= 3
Dn Slope=.0109
Boundary for River Rch & Prof#=GOMANDOL,GOMANDOL        , 5
Up Type= 0
Dn Type= 3
Dn Slope=.0109
DSS Import GetInterval= 0
DSS Import GetPeak= 0
DSS Import FillOption= 0

--- gomandol-ch.g01 (geometry) ---

Geom Title=Imported Geom 01
Version=Version 3.0.1  Mar 2001

River Reach=GOMANDOL        ,GOMANDOL
Reach XY= 2
              .5             .95              .5             .05

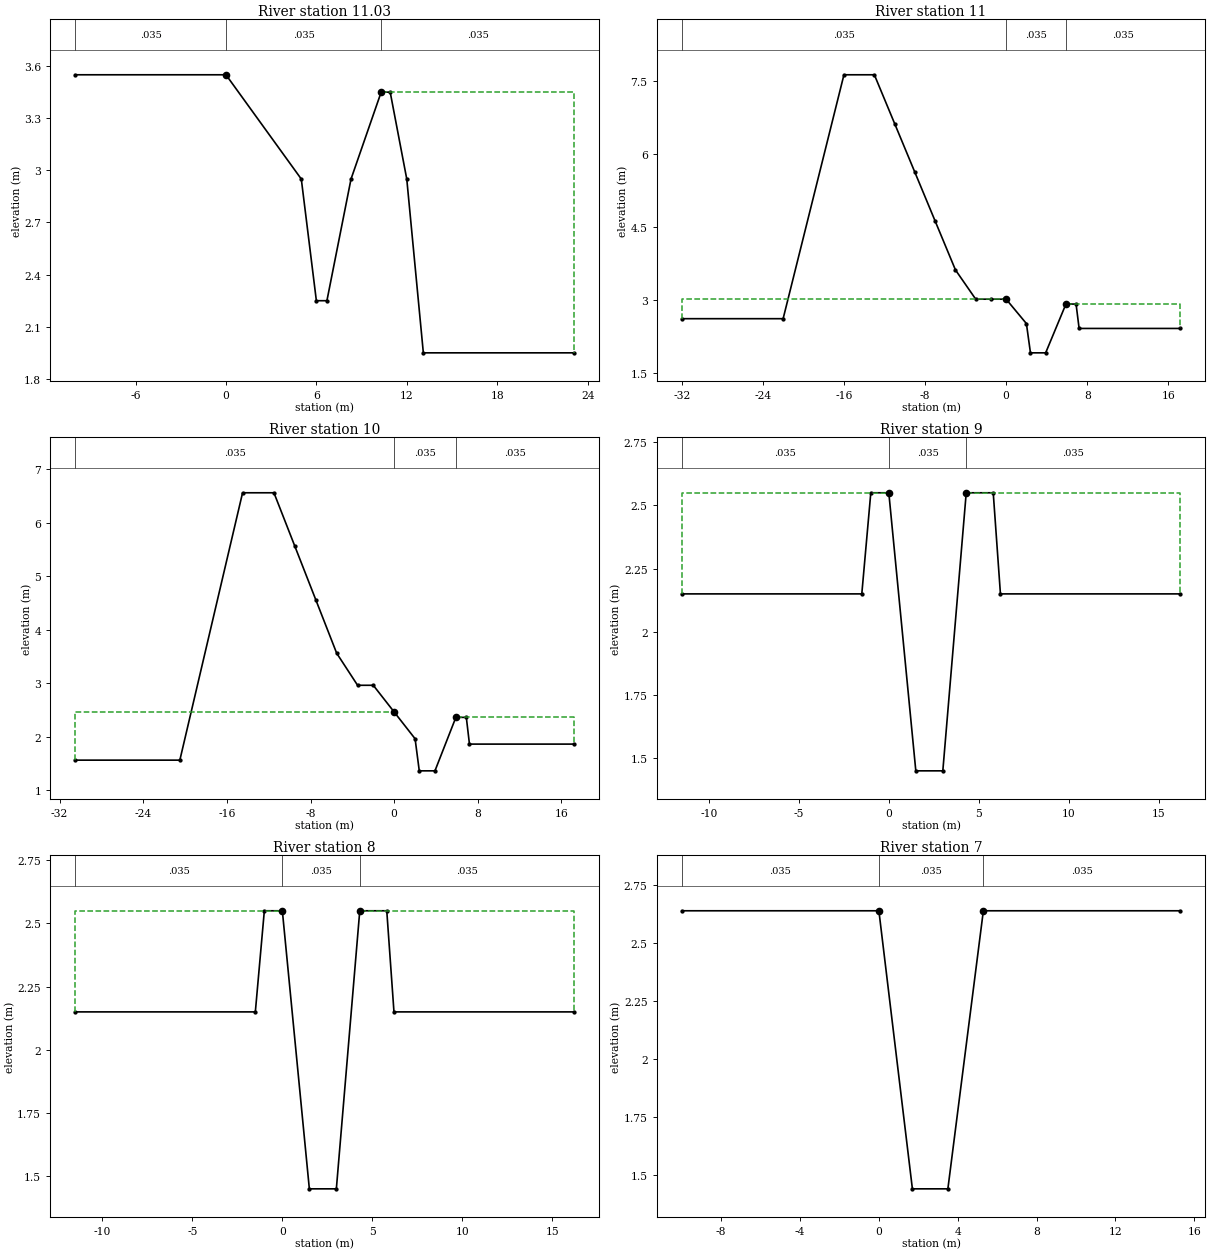
Type RM Length L Ch R = 1 ,11.03   ,30,30,30
#Sta/Elev= 11
     -10    3.55       0    3.55       5    2.95       6    2.25     6.7    2.25
     8.3    2.95    10.3    3.45    10.9    3.45      12    2.95    13.1    1.95
    23.1    1.95
#Mann= 3 , 0 , 0
     -10    .035       0       0    .035       0    10.3    .035       0
#XS Ineff= 2 , 0
               0    3.55    10.3            3.45
Permanent Ineff=
       F       F
Bank Sta=0,10.3
XS Rating Curve= 0
Exp/Cntr=.3,.1

Type RM Length L Ch R = 1 ,11      ,50,50,50
#Sta/Elev= 18
     -32    2.62     -22    2.62     -16    7.62     -13    7.62     -11    6.62
      -9    5.62      -7    4.62      -5    3.62      -3    3.02    -1.5    3.02
       0    3.02       2    2.52     2.4    1.92     3.9    1.92     5.9    2.92
     6.9    2.92     7.2    2.42    17.2    2.42
#Mann= 3 , 0 , 0
     -32    .035       0       0    .035       0     5.9    .035       0
#XS Ineff= 2 , 0
               0    3.02     5.9            2.92
Permanent Ineff=
       F       F
Bank Sta=0,5.9
XS Rating Curve= 0
Exp/Cntr=.3,.1

Type RM Length L Ch R = 1 ,10      ,50,50,50
#Sta/Elev= 17
   -30.5    1.56   -20.5    1.56   -14.5    6.56   -11.5    6.56    -9.5    5.56
    -7.5    4.56    -5.5    3.56    -3.5    2.96      -2    2.96       0    2.46
       2    1.96     2.4    1.36     3.9    1.36     5.9    2.36     6.9    2.36
     7.2    1.86    17.2    1.86
#Mann= 3 , 0 , 0
   -30.5    .035       0       0    .035       0     5.9    .035       0
#XS Ineff= 2 , 0
               0    2.46     5.9            2.36
Permanent Ineff=
       F       F
Bank Sta=0,5.9
XS Rating Curve= 0
Exp/Cntr=.3,.1

Type RM Length L Ch R = 1 ,9       ,50,50,50
#Sta/Elev= 10
   -11.5    2.15    -1.5    2.15      -1    2.55       0    2.55     1.5    1.45
       3    1.45     4.3    2.55     5.8    2.55     6.2    2.15    16.2    2.15
#Mann= 3 , 0 , 0
   -11.5    .035       0       0    .035       0     4.3    .035       0
#XS Ineff= 2 , 0
               0    2.55     4.3            2.55
Permanent Ineff=
       F       F
Bank Sta=0,4.3
XS Rating Curve= 0
Exp/Cntr=.3,.1

Type RM Length L Ch R = 1 ,8       ,50,50,50
#Sta/Elev= 10
   -11.5    2.15    -1.5    2.15      -1    2.55       0    2.55     1.5    1.45
       3    1.45     4.3    2.55     5.8    2.55     6.2    2.15    16.2    2.15
#Mann= 3 , 0 , 0
   -11.5    .035       0       0    .035       0     4.3    .035       0
#XS Ineff= 2 , 0
               0    2.55     4.3            2.55
Permanent Ineff=
       F       F
Bank Sta=0,4.3
XS Rating Curve= 0
Exp/Cntr=.3,.1

Type RM Length L Ch R = 1 ,7       ,24,24,24
#Sta/Elev= 6
     -10    2.64       0    2.64     1.7    1.44     3.5    1.44     5.3    2.64
    15.3    2.64
#Mann= 3 , 0 , 0
     -10    .035       0       0    .035       0     5.3    .035       0
#XS Ineff= 2 , 0
               0    2.64     5.3            2.64
Permanent Ineff=
       F       F
Bank Sta=0,5.3
XS Rating Curve= 0
Exp/Cntr=.3,.1

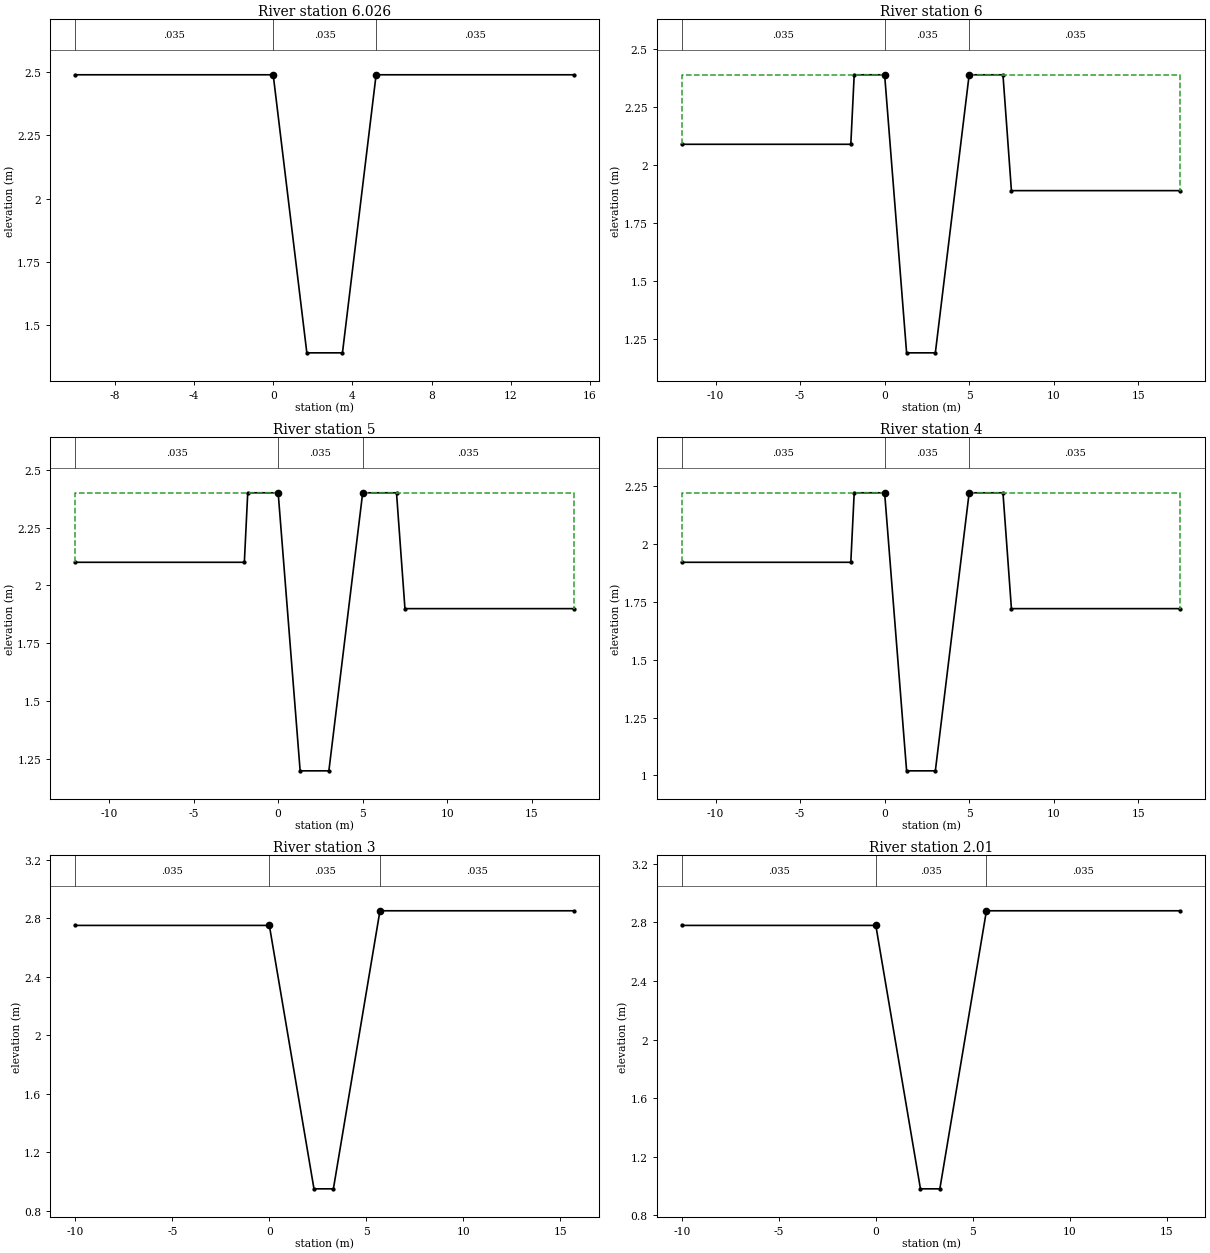
Type RM Length L Ch R = 1 ,6.026   ,26,26,26
#Sta/Elev= 6
     -10    2.49       0    2.49     1.7    1.39     3.5    1.39     5.2    2.49
    15.2    2.49
#Mann= 3 , 0 , 0
     -10    .035       0       0    .035       0     5.2    .035       0
#XS Ineff= 2 , 0
               0    2.49     5.2            2.49
Permanent Ineff=
       F       F
Bank Sta=0,5.2
XS Rating Curve= 0
Exp/Cntr=.3,.1

Type RM Length L Ch R = 1 ,6       ,50,50,50
#Sta/Elev= 10
     -12    2.09      -2    2.09    -1.8    2.39       0    2.39     1.3    1.19
       3    1.19       5    2.39       7    2.39     7.5    1.89    17.5    1.89
#Mann= 3 , 0 , 0
     -12    .035       0       0    .035       0       5    .035       0
#XS Ineff= 2 , 0
               0    2.39       5            2.39
Permanent Ineff=
       F       F
Bank Sta=0,5
XS Rating Curve= 0
Exp/Cntr=.3,.1

Type RM Length L Ch R = 1 ,5       ,50,50,50
#Sta/Elev= 10
     -12     2.1      -2     2.1    -1.8     2.4       0     2.4     1.3     1.2
       3     1.2       5     2.4       7     2.4     7.5     1.9    17.5     1.9
#Mann= 3 , 0 , 0
     -12    .035       0       0    .035       0       5    .035       0
#XS Ineff= 2 , 0
               0     2.4       5             2.4
Permanent Ineff=
       F       F
Bank Sta=0,5
XS Rating Curve= 0
Exp/Cntr=.3,.1

Type RM Length L Ch R = 1 ,4       ,50,50,50
#Sta/Elev= 10
     -12    1.92      -2    1.92    -1.8    2.22       0    2.22     1.3    1.02
       3    1.02       5    2.22       7    2.22     7.5    1.72    17.5    1.72
#Mann= 3 , 0 , 0
     -12    .035       0       0    .035       0       5    .035       0
#XS Ineff= 2 , 0
               0    2.22       5            2.22
Permanent Ineff=
       F       F
Bank Sta=0,5
XS Rating Curve= 0
Exp/Cntr=.3,.1

Type RM Length L Ch R = 1 ,3       ,40,40,40
#Sta/Elev= 6
     -10    2.75       0    2.75     2.3     .95     3.3     .95     5.7    2.85
    15.7    2.85
#Mann= 3 , 0 , 0
     -10    .035       0       0    .035       0     5.7    .035       0
#XS Ineff= 2 , 0
               0    2.75     5.7            2.85
Permanent Ineff=
       F       F
Bank Sta=0,5.7
XS Rating Curve= 0
Exp/Cntr=.3,.1

Type RM Length L Ch R = 1 ,2.01    ,10,10,10
#Sta/Elev= 6
     -10    2.78       0    2.78     2.3     .98     3.3     .98     5.7    2.88
    15.7    2.88
#Mann= 3 , 0 , 0
     -10    .035       0       0    .035       0     5.7    .035       0
#XS Ineff= 2 , 0
               0    2.78     5.7            2.88
Permanent Ineff=
       F       F
Bank Sta=0,5.7
XS Rating Curve= 0
Exp/Cntr=.3,.1

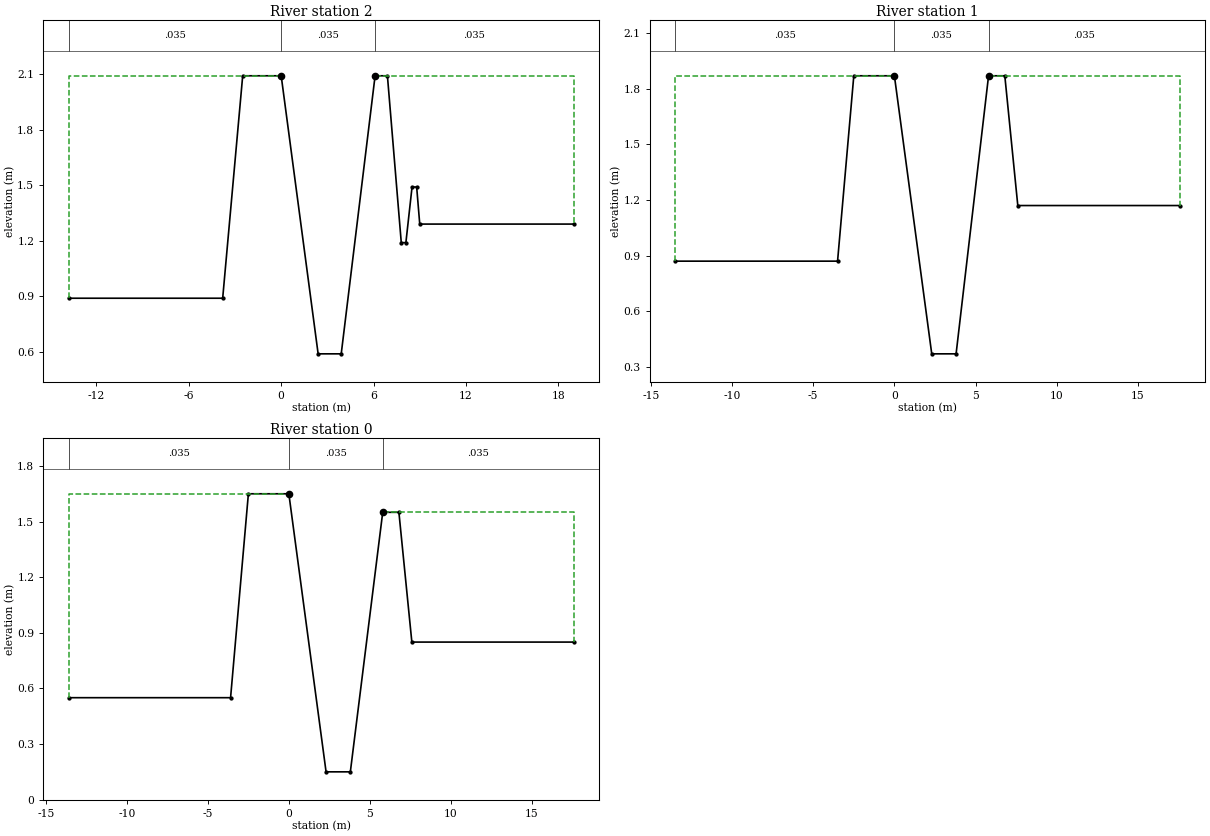
Type RM Length L Ch R = 1 ,2       ,50,50,50
#Sta/Elev= 14
   -13.8     .89    -3.8     .89    -2.5    2.09       0    2.09     2.4     .59
     3.9     .59     6.1    2.09     6.9    2.09     7.8    1.19     8.1    1.19
     8.5    1.49     8.8    1.49       9    1.29      19    1.29
#Mann= 3 , 0 , 0
   -13.8    .035       0       0    .035       0     6.1    .035       0
#XS Ineff= 2 , 0
               0    2.09     6.1            2.09
Permanent Ineff=
       F       F
Bank Sta=0,6.1
XS Rating Curve= 0
Exp/Cntr=.3,.1

Type RM Length L Ch R = 1 ,1       ,50,50,50
#Sta/Elev= 10
   -13.5     .87    -3.5     .87    -2.5    1.87       0    1.87     2.3     .37
     3.8     .37     5.8    1.87     6.8    1.87     7.6    1.17    17.6    1.17
#Mann= 3 , 0 , 0
   -13.5    .035       0       0    .035       0     5.8    .035       0
#XS Ineff= 2 , 0
               0    1.87     5.8            1.87
Permanent Ineff=
       F       F
Bank Sta=0,5.8
XS Rating Curve= 0
Exp/Cntr=.3,.1

Type RM Length L Ch R = 1 ,0       ,0,0,0
#Sta/Elev= 10
   -13.6     .55    -3.6     .55    -2.5    1.65       0    1.65     2.3     .15
     3.8     .15     5.8    1.55     6.8    1.55     7.6     .85    17.6     .85
#Mann= 3 , 0 , 0
   -13.6    .035       0       0    .035       0     5.8    .035       0
#XS Ineff= 2 , 0
               0    1.65     5.8            1.55
Permanent Ineff=
       F       F
Bank Sta=0,5.8
XS Rating Curve= 0
Exp/Cntr=.3,.1

Chan Stop Cuts=-1