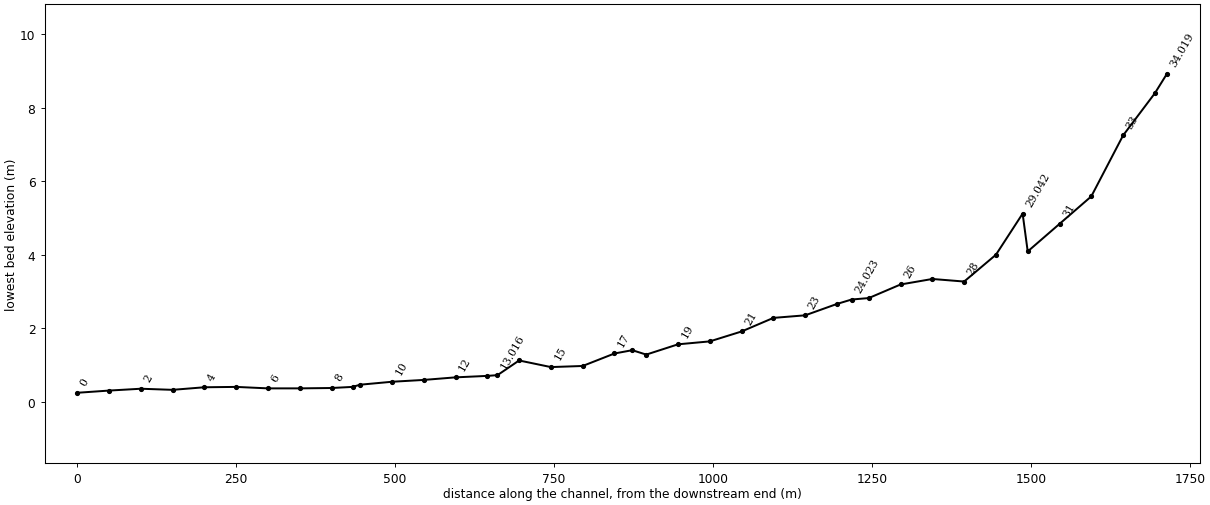
--- son.prj (project) ---

Proj Title=sonbaraki
Current Plan=p01
Default Exp/Contr=.3,.1
SI Units
Geom File=g01
Flow File=f01
Plan File=p01
Y Axis Title=Elevation
X Axis Title(PF)=Main Channel Distance
X Axis Title(XS)=Station
BEGIN DESCRIPTION:
           BACK WATER COMPUTATION
      APPLICATION OF HEC-2 BY Samju Construction Engineering
      sonbaragi-ch: 10,20,30,50,80 yr
END DESCRIPTION:
DSS Export Rating Curves= 0
DSS Export Rating Curve Sorted= 0
DSS Export Volume Flow Curves= 0
DXF OffsetX= 0
DXF OffsetY= 0
DXF ScaleX= 1
DXF ScaleY= 10

--- son.p01 (plan) ---

Plan Title=Imported Plan 01
Version=Version 3.0.1  Mar 2001
Short Identifier=Imported Pla
Geom File=g01
Flow File=f01
Subcritical Flow
K Sum by GR= 0
Std Step Tol= 0.003
Critical Tol= 0.003
Num of Std Step Trials= 20
Max Error Tol= 0.1
Flow Tol Ratio= 0.001
Split Flow NTrial= 30
Split Flow Tol= 0.02
Split Flow Ratio= 0.02
Log Output Level= 0
Friction Slope Method= 1
Unsteady Friction Slope Method= 2
Parabolic Critical Depth
Global Vel Dist= 0 , 0 , 0
Global Log Level= 0
CheckData=True
Encroach Param=-1 ,0,0, 0
Computation Interval=1HOUR
Output Interval=1HOUR
Run HTab= 0
Run UNet= 0
Run PostProcess= 0
UNET Theta= 1
UNET ZTol= 0.02
UNET ZSATol= 0.1
UNET MxIter= 20
UNET MaxInSteps= 20
UNET DtIC= 0
UNET DtMin= 0
UNET MaxCRTS= 20
UNET WFStab= 2
UNET SFStab= 1
UNET WFX= 1
UNET SFX= 1
UNET Convert EG Bridges=-1
UNET Use Existing IB Tables=-1
Instantaneous Interval=1HOUR
Write IC File= 0
Write Velocity= 0
Write Detailed= 0

--- son.f01 (steady flow) ---

Flow Title=Imported Flow 01
Version=Version 3.0.1  Mar 2001
Number of Profiles= 5
Profile Names=10yr,20yr,30yr,50yr,80yr
River Rch & RM=RIVER-1,Reach-1         ,34.019
    9.76   10.75   11.33   12.06   12.73
River Rch & RM=RIVER-1,Reach-1         ,10
   13.48   14.86   15.66   16.68   17.61
River Rch & RM=SONBARAKI,SONBARAKI       ,34.019
    9.76   10.75   11.33   12.06   12.73
River Rch & RM=SONBARAKI,SONBARAKI       ,10
   13.48   14.86   15.66   16.68   17.61
Boundary for River Rch & Prof#=SONBARAKI,SONBARAKI       , 1
Up Type= 0
Dn Type= 3
Dn Slope=.004
Boundary for River Rch & Prof#=SONBARAKI,SONBARAKI       , 2
Up Type= 0
Dn Type= 3
Dn Slope=.004
Boundary for River Rch & Prof#=SONBARAKI,SONBARAKI       , 3
Up Type= 0
Dn Type= 3
Dn Slope=.004
Boundary for River Rch & Prof#=SONBARAKI,SONBARAKI       , 4
Up Type= 0
Dn Type= 3
Dn Slope=.004
Boundary for River Rch & Prof#=SONBARAKI,SONBARAKI       , 5
Up Type= 0
Dn Type= 3
Dn Slope=.004
DSS Import GetInterval= 0
DSS Import GetPeak= 0
DSS Import FillOption= 0

--- son.g01 (geometry) ---

Geom Title=Imported Geom 01
Version=Version 3.0.1  Mar 2001

River Reach=SONBARAKI       ,SONBARAKI
Reach XY= 2
              .5             .95              .5             .05

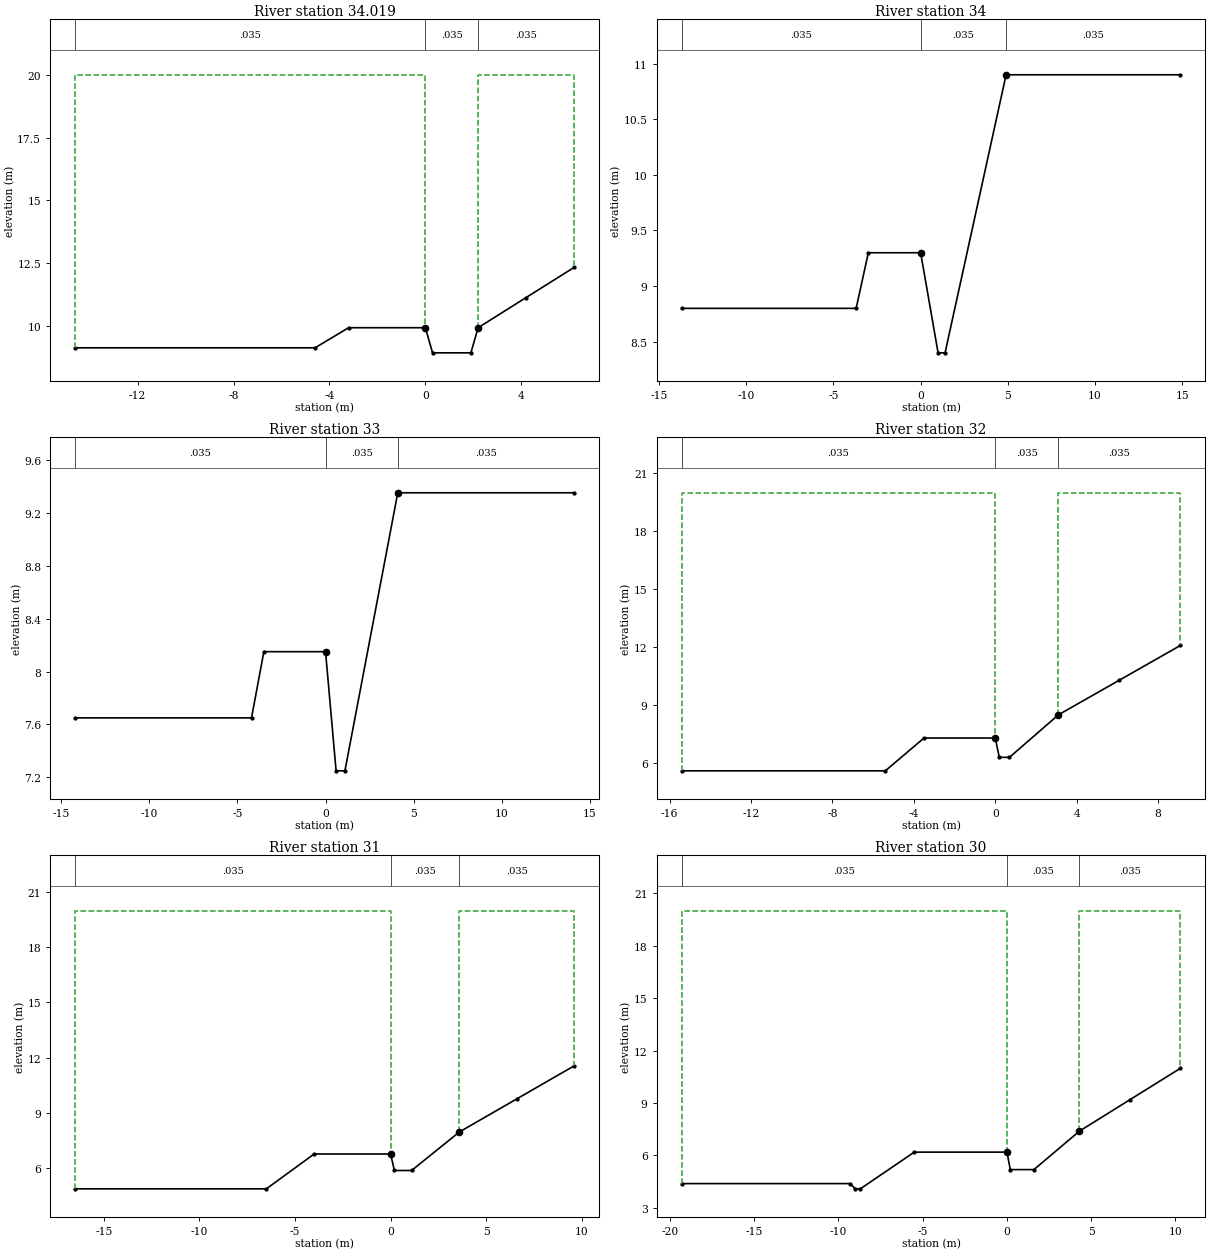
Type RM Length L Ch R = 1 ,34.019  ,19,19,19
#Sta/Elev= 9
   -14.6    9.13    -4.6    9.13    -3.2    9.93       0    9.93      .3    8.93
     1.9    8.93     2.2    9.93     4.2   11.13     6.2   12.33
#Mann= 3 , 0 , 0
   -14.6    .035       0       0    .035       0     2.2    .035       0
#XS Ineff= 2 , 0
               0      20     2.2              20
Permanent Ineff=
       F       F
#Block Obstruct= 2 , 0
                             2.2
Bank Sta=0,2.2
XS Rating Curve= 0
Exp/Cntr=.3,.1

Type RM Length L Ch R = 1 ,34      ,50,50,50
#Sta/Elev= 8
   -13.7     8.8    -3.7     8.8      -3     9.3       0     9.3       1     8.4
     1.4     8.4     4.9    10.9    14.9    10.9
#Mann= 3 , 0 , 0
   -13.7    .035       0       0    .035       0     4.9    .035       0
#XS Ineff= 2 , 0
               0      20     4.9              20
Permanent Ineff=
       F       F
#Block Obstruct= 2 , 0
                             4.9
Bank Sta=0,4.9
XS Rating Curve= 0
Exp/Cntr=.3,.1

Type RM Length L Ch R = 1 ,33      ,50,50,50
#Sta/Elev= 8
   -14.2    7.65    -4.2    7.65    -3.5    8.15       0    8.15      .6    7.25
     1.1    7.25     4.1    9.35    14.1    9.35
#Mann= 3 , 0 , 0
   -14.2    .035       0       0    .035       0     4.1    .035       0
#XS Ineff= 2 , 0
               0      20     4.1              20
Permanent Ineff=
       F       F
#Block Obstruct= 2 , 0
                             4.1
Bank Sta=0,4.1
XS Rating Curve= 0
Exp/Cntr=.3,.1

Type RM Length L Ch R = 1 ,32      ,50,50,50
#Sta/Elev= 9
   -15.4    5.59    -5.4    5.59    -3.5    7.29       0    7.29      .2    6.29
      .7    6.29     3.1    8.49     6.1   10.29     9.1   12.09
#Mann= 3 , 0 , 0
   -15.4    .035       0       0    .035       0     3.1    .035       0
#XS Ineff= 2 , 0
               0      20     3.1              20
Permanent Ineff=
       F       F
#Block Obstruct= 2 , 0
                             3.1
Bank Sta=0,3.1
XS Rating Curve= 0
Exp/Cntr=.3,.1

Type RM Length L Ch R = 1 ,31      ,50,50,50
#Sta/Elev= 9
   -16.5    4.84    -6.5    4.84      -4    6.74       0    6.74      .2    5.84
     1.1    5.84     3.6    7.94     6.6    9.74     9.6   11.54
#Mann= 3 , 0 , 0
   -16.5    .035       0       0    .035       0     3.6    .035       0
#XS Ineff= 2 , 0
               0      20     3.6              20
Permanent Ineff=
       F       F
#Block Obstruct= 2 , 0
                             3.6
Bank Sta=0,3.6
XS Rating Curve= 0
Exp/Cntr=.3,.1

Type RM Length L Ch R = 1 ,30      ,8,8,8
#Sta/Elev= 11
   -19.3    4.39    -9.3    4.39      -9    4.09    -8.7    4.09    -5.5    6.19
       0    6.19      .2    5.19     1.6    5.19     4.3    7.39     7.3    9.19
    10.3   10.99
#Mann= 3 , 0 , 0
   -19.3    .035       0       0    .035       0     4.3    .035       0
#XS Ineff= 2 , 0
               0      20     4.3              20
Permanent Ineff=
       F       F
#Block Obstruct= 2 , 0
                             4.3
Bank Sta=0,4.3
XS Rating Curve= 0
Exp/Cntr=.3,.1

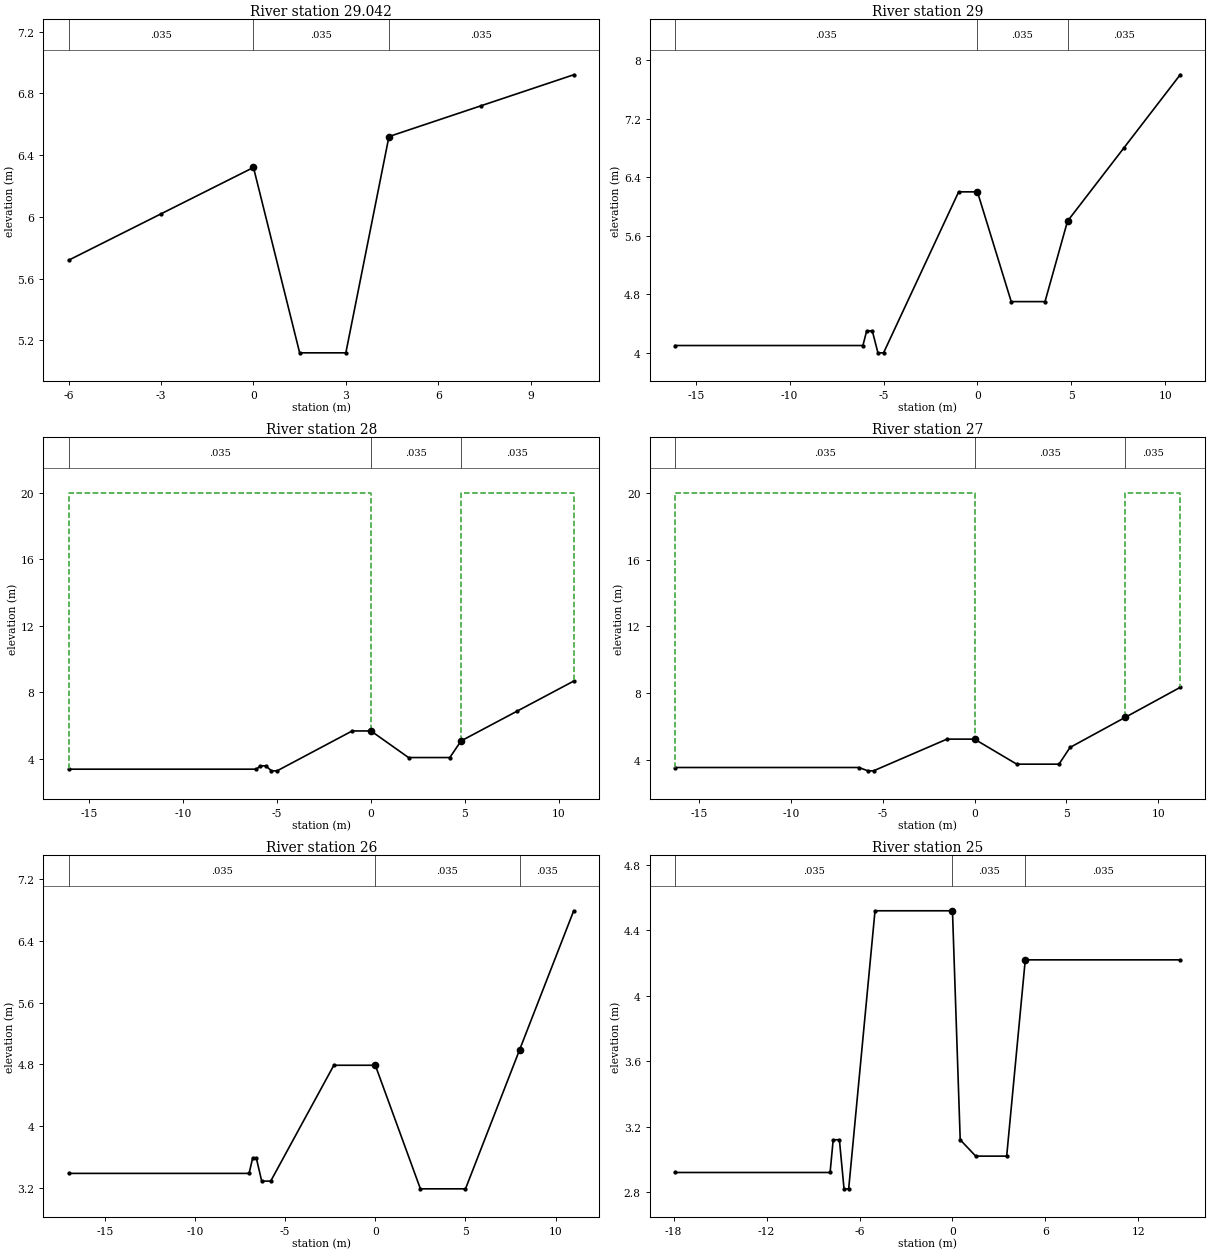
Type RM Length L Ch R = 1 ,29.042  ,42,42,42
#Sta/Elev= 8
      -6    5.72      -3    6.02       0    6.32     1.5    5.12       3    5.12
     4.4    6.52     7.4    6.72    10.4    6.92
#Mann= 3 , 0 , 0
      -6    .035       0       0    .035       0     4.4    .035       0
#XS Ineff= 2 , 0
               0      20     4.4              20
Permanent Ineff=
       F       F
#Block Obstruct= 2 , 0
                             4.4
Bank Sta=0,4.4
XS Rating Curve= 0
Exp/Cntr=.3,.1

Type RM Length L Ch R = 1 ,29      ,50,50,50
#Sta/Elev= 13
   -16.1     4.1    -6.1     4.1    -5.9     4.3    -5.6     4.3    -5.3       4
      -5       4      -1     6.2       0     6.2     1.8     4.7     3.6     4.7
     4.8     5.8     7.8     6.8    10.8     7.8
#Mann= 3 , 0 , 0
   -16.1    .035       0       0    .035       0     4.8    .035       0
#XS Ineff= 2 , 0
               0      20     4.8              20
Permanent Ineff=
       F       F
#Block Obstruct= 2 , 0
                             4.8
Bank Sta=0,4.8
XS Rating Curve= 0
Exp/Cntr=.3,.1

Type RM Length L Ch R = 1 ,28      ,50,50,50
#Sta/Elev= 13
   -16.1    3.37    -6.1    3.37    -5.9    3.57    -5.6    3.57    -5.3    3.27
      -5    3.27      -1    5.67       0    5.67       2    4.07     4.2    4.07
     4.8    5.07     7.8    6.87    10.8    8.67
#Mann= 3 , 0 , 0
   -16.1    .035       0       0    .035       0     4.8    .035       0
#XS Ineff= 2 , 0
               0      20     4.8              20
Permanent Ineff=
       F       F
#Block Obstruct= 2 , 0
                             4.8
Bank Sta=0,4.8
XS Rating Curve= 0
Exp/Cntr=.3,.1

Type RM Length L Ch R = 1 ,27      ,50,50,50
#Sta/Elev= 11
   -16.3    3.54    -6.3    3.54    -5.8    3.34    -5.5    3.34    -1.5    5.24
       0    5.24     2.3    3.74     4.6    3.74     5.2    4.74     8.2    6.54
    11.2    8.34
#Mann= 3 , 0 , 0
   -16.3    .035       0       0    .035       0     8.2    .035       0
#XS Ineff= 2 , 0
               0      20     8.2              20
Permanent Ineff=
       F       F
#Block Obstruct= 2 , 0
                             8.2
Bank Sta=0,8.2
XS Rating Curve= 0
Exp/Cntr=.3,.1

Type RM Length L Ch R = 1 ,26      ,50,50,50
#Sta/Elev= 12
     -17    3.39      -7    3.39    -6.8    3.59    -6.6    3.59    -6.3    3.29
    -5.8    3.29    -2.3    4.79       0    4.79     2.5    3.19       5    3.19
       8    4.99      11    6.79
#Mann= 3 , 0 , 0
     -17    .035       0       0    .035       0       8    .035       0
#XS Ineff= 2 , 0
               0      20       8              20
Permanent Ineff=
       F       F
#Block Obstruct= 2 , 0
                               8
Bank Sta=0,8
XS Rating Curve= 0
Exp/Cntr=.3,.1

Type RM Length L Ch R = 1 ,25      ,27,27,27
#Sta/Elev= 13
   -17.9    2.92    -7.9    2.92    -7.7    3.12    -7.3    3.12      -7    2.82
    -6.7    2.82      -5    4.52       0    4.52      .5    3.12     1.5    3.02
     3.5    3.02     4.7    4.22    14.7    4.22
#Mann= 3 , 0 , 0
   -17.9    .035       0       0    .035       0     4.7    .035       0
#XS Ineff= 2 , 0
               0      20     4.7              20
Permanent Ineff=
       F       F
#Block Obstruct= 2 , 0
                             4.7
Bank Sta=0,4.7
XS Rating Curve= 0
Exp/Cntr=.3,.1

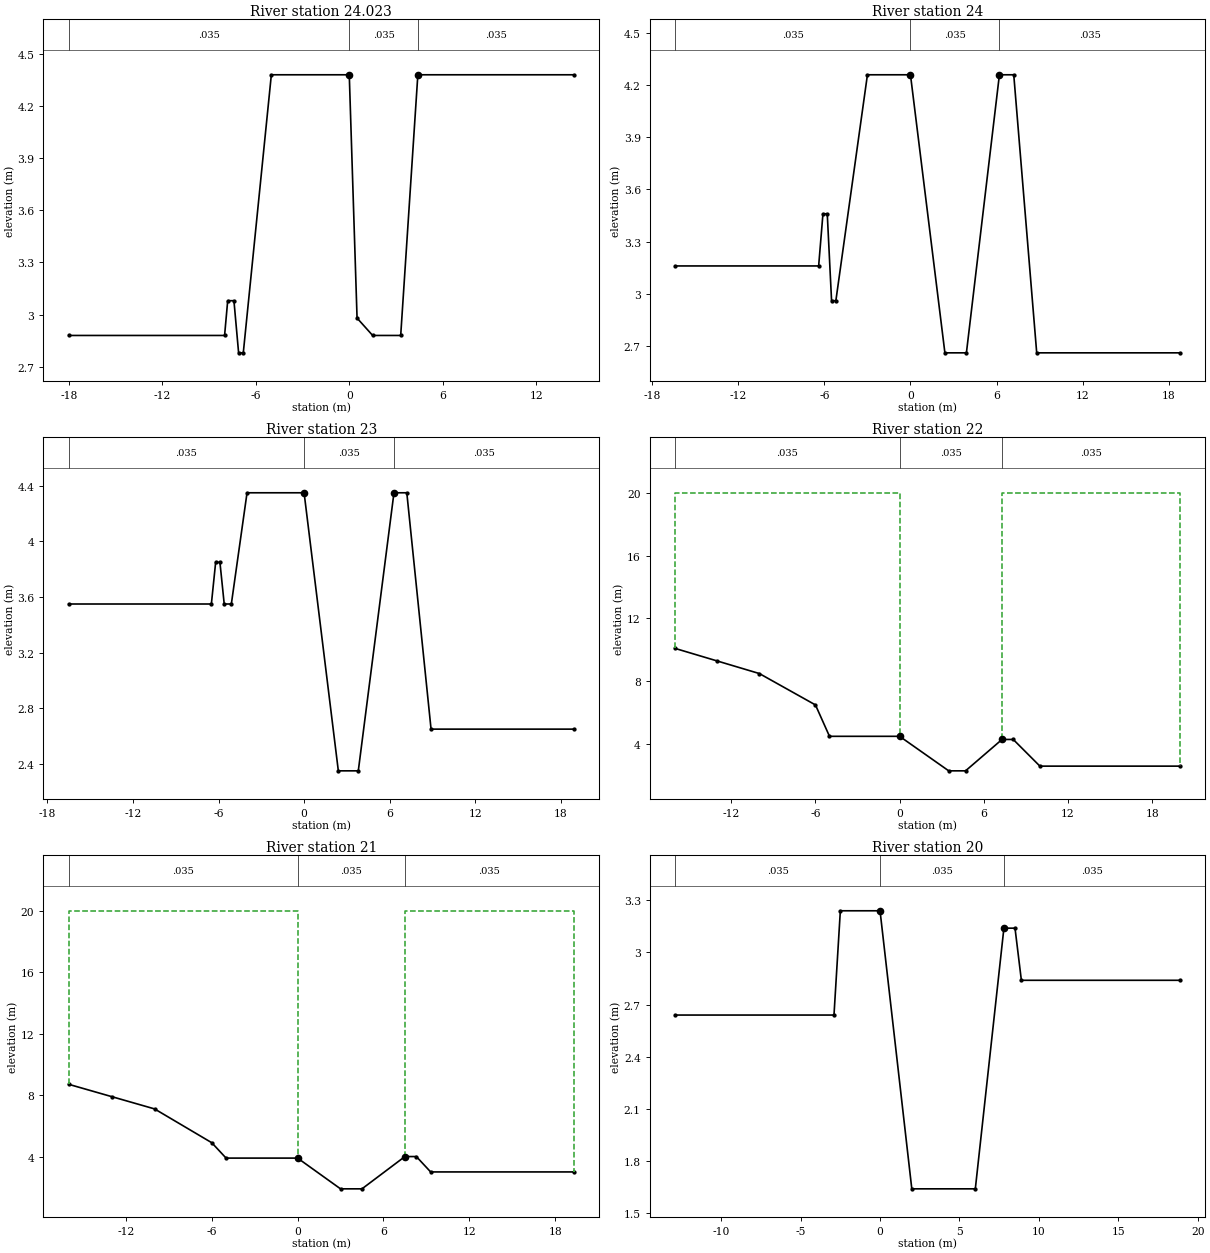
Type RM Length L Ch R = 1 ,24.023  ,23,23,23
#Sta/Elev= 13
     -18    2.88      -8    2.88    -7.8    3.08    -7.4    3.08    -7.1    2.78
    -6.8    2.78      -5    4.38       0    4.38      .5    2.98     1.5    2.88
     3.3    2.88     4.4    4.38    14.4    4.38
#Mann= 3 , 0 , 0
     -18    .035       0       0    .035       0     4.4    .035       0
#XS Ineff= 2 , 0
               0      20     4.4              20
Permanent Ineff=
       F       F
#Block Obstruct= 2 , 0
                             4.4
Bank Sta=0,4.4
XS Rating Curve= 0
Exp/Cntr=.3,.1

Type RM Length L Ch R = 1 ,24      ,50,50,50
#Sta/Elev= 14
   -16.4    3.16    -6.4    3.16    -6.1    3.46    -5.8    3.46    -5.5    2.96
    -5.2    2.96      -3    4.26       0    4.26     2.4    2.66     3.9    2.66
     6.2    4.26     7.2    4.26     8.8    2.66    18.8    2.66
#Mann= 3 , 0 , 0
   -16.4    .035       0       0    .035       0     6.2    .035       0
#XS Ineff= 2 , 0
               0      20     6.2              20
Permanent Ineff=
       F       F
#Block Obstruct= 2 , 0
                             6.2
Bank Sta=0,6.2
XS Rating Curve= 0
Exp/Cntr=.3,.1

Type RM Length L Ch R = 1 ,23      ,50,50,50
#Sta/Elev= 14
   -16.5    3.55    -6.5    3.55    -6.2    3.85    -5.9    3.85    -5.6    3.55
    -5.1    3.55      -4    4.35       0    4.35     2.4    2.35     3.8    2.35
     6.3    4.35     7.2    4.35     8.9    2.65    18.9    2.65
#Mann= 3 , 0 , 0
   -16.5    .035       0       0    .035       0     6.3    .035       0
#XS Ineff= 2 , 0
               0      20     6.3              20
Permanent Ineff=
       F       F
#Block Obstruct= 2 , 0
                             6.3
Bank Sta=0,6.3
XS Rating Curve= 0
Exp/Cntr=.3,.1

Type RM Length L Ch R = 1 ,22      ,50,50,50
#Sta/Elev= 12
     -16   10.08     -13    9.28     -10    8.48      -6    6.48      -5    4.48
       0    4.48     3.5    2.28     4.7    2.28     7.3    4.28     8.1    4.28
      10    2.58      20    2.58
#Mann= 3 , 0 , 0
     -16    .035       0       0    .035       0     7.3    .035       0
#XS Ineff= 2 , 0
               0      20     7.3              20
Permanent Ineff=
       F       F
#Block Obstruct= 2 , 0
                             7.3
Bank Sta=0,7.3
XS Rating Curve= 0
Exp/Cntr=.3,.1

Type RM Length L Ch R = 1 ,21      ,50,50,50
#Sta/Elev= 12
     -16    8.71     -13    7.91     -10    7.11      -6    4.91      -5    3.91
       0    3.91       3    1.91     4.5    1.91     7.5    4.01     8.3    4.01
     9.3    3.01    19.3    3.01
#Mann= 3 , 0 , 0
     -16    .035       0       0    .035       0     7.5    .035       0
#XS Ineff= 2 , 0
               0      20     7.5              20
Permanent Ineff=
       F       F
#Block Obstruct= 2 , 0
                             7.5
Bank Sta=0,7.5
XS Rating Curve= 0
Exp/Cntr=.3,.1

Type RM Length L Ch R = 1 ,20      ,50,50,50
#Sta/Elev= 10
   -12.9    2.64    -2.9    2.64    -2.5    3.24       0    3.24       2    1.64
       6    1.64     7.8    3.14     8.5    3.14     8.9    2.84    18.9    2.84
#Mann= 3 , 0 , 0
   -12.9    .035       0       0    .035       0     7.8    .035       0
#XS Ineff= 2 , 0
               0      20     7.8              20
Permanent Ineff=
       F       F
#Block Obstruct= 2 , 0
                             7.8
Bank Sta=0,7.8
XS Rating Curve= 0
Exp/Cntr=.3,.1

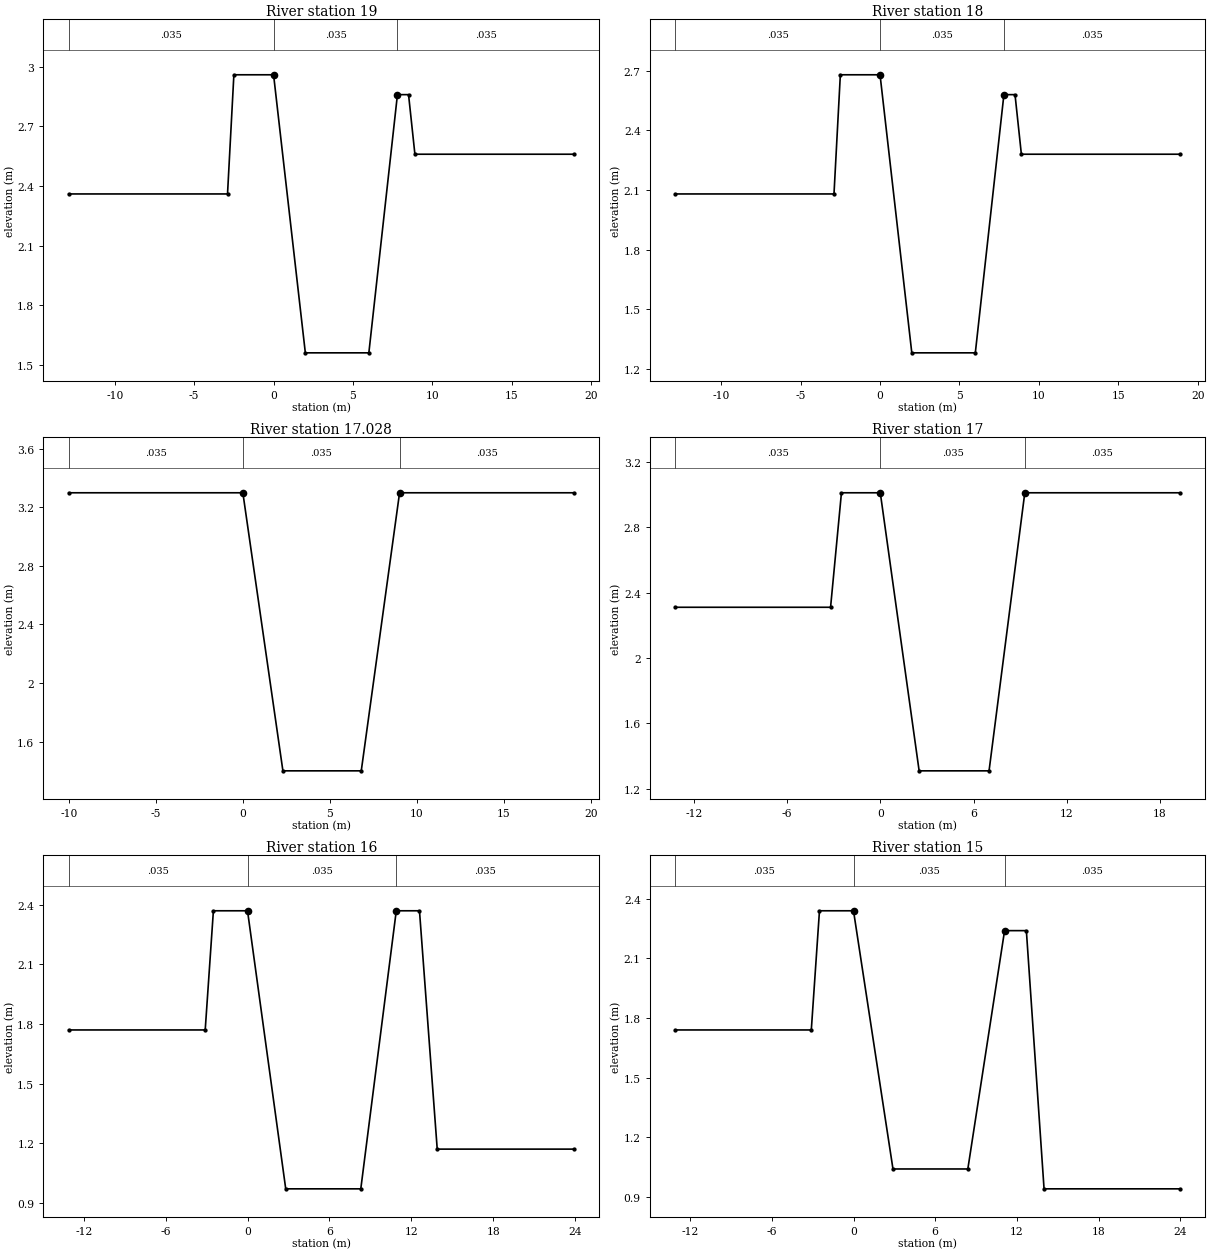
Type RM Length L Ch R = 1 ,19      ,50,50,50
#Sta/Elev= 10
   -12.9    2.36    -2.9    2.36    -2.5    2.96       0    2.96       2    1.56
       6    1.56     7.8    2.86     8.5    2.86     8.9    2.56    18.9    2.56
#Mann= 3 , 0 , 0
   -12.9    .035       0       0    .035       0     7.8    .035       0
#XS Ineff= 2 , 0
               0      20     7.8              20
Permanent Ineff=
       F       F
#Block Obstruct= 2 , 0
                             7.8
Bank Sta=0,7.8
XS Rating Curve= 0
Exp/Cntr=.3,.1

Type RM Length L Ch R = 1 ,18      ,22,22,22
#Sta/Elev= 10
   -12.9    2.08    -2.9    2.08    -2.5    2.68       0    2.68       2    1.28
       6    1.28     7.8    2.58     8.5    2.58     8.9    2.28    18.9    2.28
#Mann= 3 , 0 , 0
   -12.9    .035       0       0    .035       0     7.8    .035       0
#XS Ineff= 2 , 0
               0      20     7.8              20
Permanent Ineff=
       F       F
#Block Obstruct= 2 , 0
                             7.8
Bank Sta=0,7.8
XS Rating Curve= 0
Exp/Cntr=.3,.1

Type RM Length L Ch R = 1 ,17.028  ,28,28,28
#Sta/Elev= 6
     -10     3.3       0     3.3     2.3     1.4     6.8     1.4       9     3.3
      19     3.3
#Mann= 3 , 0 , 0
     -10    .035       0       0    .035       0       9    .035       0
#XS Ineff= 2 , 0
               0      20       9              20
Permanent Ineff=
       F       F
#Block Obstruct= 2 , 0
                               9
Bank Sta=0,9
XS Rating Curve= 0
Exp/Cntr=.3,.1

Type RM Length L Ch R = 1 ,17      ,50,50,50
#Sta/Elev= 8
   -13.2    2.31    -3.2    2.31    -2.5    3.01       0    3.01     2.5    1.31
       7    1.31     9.3    3.01    19.3    3.01
#Mann= 3 , 0 , 0
   -13.2    .035       0       0    .035       0     9.3    .035       0
#XS Ineff= 2 , 0
               0      20     9.3              20
Permanent Ineff=
       F       F
#Block Obstruct= 2 , 0
                             9.3
Bank Sta=0,9.3
XS Rating Curve= 0
Exp/Cntr=.3,.1

Type RM Length L Ch R = 1 ,16      ,50,50,50
#Sta/Elev= 10
   -13.1    1.77    -3.1    1.77    -2.5    2.37       0    2.37     2.8     .97
     8.3     .97    10.9    2.37    12.6    2.37    13.9    1.17    23.9    1.17
#Mann= 3 , 0 , 0
   -13.1    .035       0       0    .035       0    10.9    .035       0
#XS Ineff= 2 , 0
               0      20    10.9              20
Permanent Ineff=
       F       F
#Block Obstruct= 2 , 0
                            10.9
Bank Sta=0,10.9
XS Rating Curve= 0
Exp/Cntr=.3,.1

Type RM Length L Ch R = 1 ,15      ,50,50,50
#Sta/Elev= 10
   -13.1    1.74    -3.1    1.74    -2.5    2.34       0    2.34     2.9    1.04
     8.4    1.04    11.1    2.24    12.7    2.24      14     .94      24     .94
#Mann= 3 , 0 , 0
   -13.1    .035       0       0    .035       0    11.1    .035       0
#XS Ineff= 2 , 0
               0      20    11.1              20
Permanent Ineff=
       F       F
#Block Obstruct= 2 , 0
                            11.1
Bank Sta=0,11.1
XS Rating Curve= 0
Exp/Cntr=.3,.1

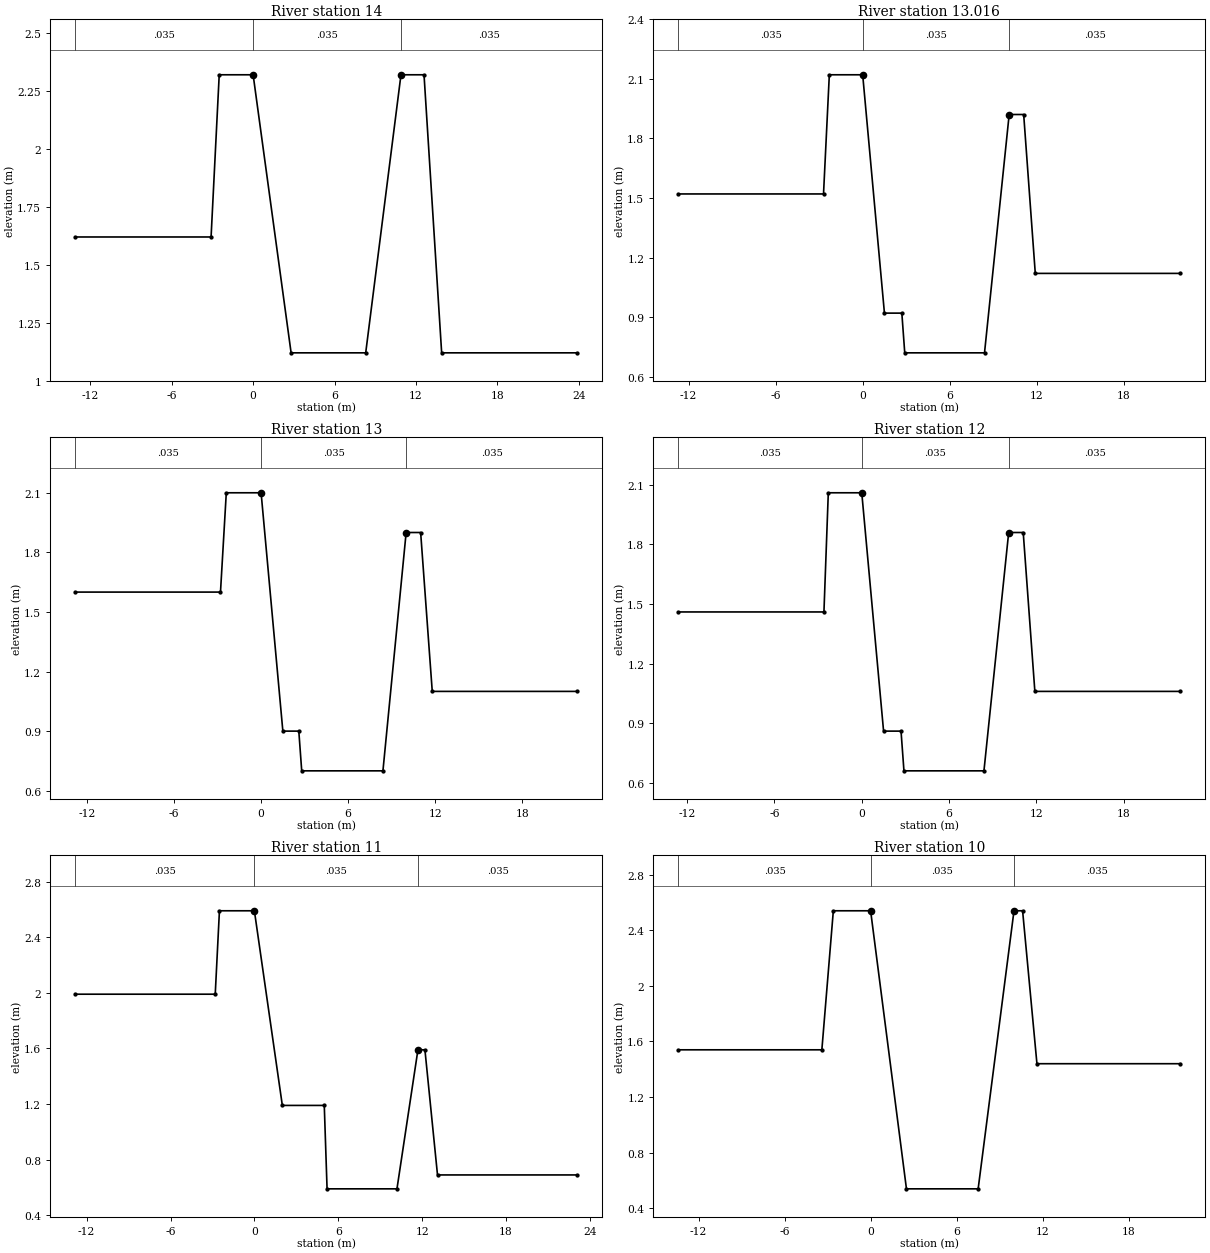
Type RM Length L Ch R = 1 ,14      ,34,34,34
#Sta/Elev= 10
   -13.1    1.62    -3.1    1.62    -2.5    2.32       0    2.32     2.8    1.12
     8.3    1.12    10.9    2.32    12.6    2.32    13.9    1.12    23.9    1.12
#Mann= 3 , 0 , 0
   -13.1    .035       0       0    .035       0    10.9    .035       0
#XS Ineff= 2 , 0
               0      20    10.9              20
Permanent Ineff=
       F       F
#Block Obstruct= 2 , 0
                            10.9
Bank Sta=0,10.9
XS Rating Curve= 0
Exp/Cntr=.3,.1

Type RM Length L Ch R = 1 ,13.016  ,16,16,16
#Sta/Elev= 12
   -12.7    1.52    -2.7    1.52    -2.3    2.12       0    2.12     1.5     .92
     2.7     .92     2.9     .72     8.4     .72    10.1    1.92    11.1    1.92
    11.9    1.12    21.9    1.12
#Mann= 3 , 0 , 0
   -12.7    .035       0       0    .035       0    10.1    .035       0
#XS Ineff= 2 , 0
               0      20    10.1              20
Permanent Ineff=
       F       F
#Block Obstruct= 2 , 0
                            10.1
Bank Sta=0,10.1
XS Rating Curve= 0
Exp/Cntr=.3,.1

Type RM Length L Ch R = 1 ,13      ,50,50,50
#Sta/Elev= 12
   -12.8     1.6    -2.8     1.6    -2.4     2.1       0     2.1     1.5      .9
     2.6      .9     2.8      .7     8.4      .7      10     1.9      11     1.9
    11.8     1.1    21.8     1.1
#Mann= 3 , 0 , 0
   -12.8    .035       0       0    .035       0      10    .035       0
#XS Ineff= 2 , 0
               0      20      10              20
Permanent Ineff=
       F       F
#Block Obstruct= 2 , 0
                              10
Bank Sta=0,10
XS Rating Curve= 0
Exp/Cntr=.3,.1

Type RM Length L Ch R = 1 ,12      ,50,50,50
#Sta/Elev= 12
   -12.6    1.46    -2.6    1.46    -2.3    2.06       0    2.06     1.5     .86
     2.7     .86     2.9     .66     8.4     .66    10.1    1.86    11.1    1.86
    11.9    1.06    21.9    1.06
#Mann= 3 , 0 , 0
   -12.6    .035       0       0    .035       0    10.1    .035       0
#XS Ineff= 2 , 0
               0      20    10.1              20
Permanent Ineff=
       F       F
#Block Obstruct= 2 , 0
                            10.1
Bank Sta=0,10.1
XS Rating Curve= 0
Exp/Cntr=.3,.1

Type RM Length L Ch R = 1 ,11      ,50,50,50
#Sta/Elev= 12
   -12.8    1.99    -2.8    1.99    -2.5    2.59       0    2.59       2    1.19
       5    1.19     5.2     .59    10.2     .59    11.7    1.59    12.2    1.59
    13.1     .69    23.1     .69
#Mann= 3 , 0 , 0
   -12.8    .035       0       0    .035       0    11.7    .035       0
#XS Ineff= 2 , 0
               0      20    11.7              20
Permanent Ineff=
       F       F
#Block Obstruct= 2 , 0
                            11.7
Bank Sta=0,11.7
XS Rating Curve= 0
Exp/Cntr=.3,.1

Type RM Length L Ch R = 1 ,10      ,50,50,50
#Sta/Elev= 10
   -13.4    1.54    -3.4    1.54    -2.6    2.54       0    2.54     2.5     .54
     7.5     .54      10    2.54    10.6    2.54    11.6    1.44    21.6    1.44
#Mann= 3 , 0 , 0
   -13.4    .035       0       0    .035       0      10    .035       0
#XS Ineff= 2 , 0
               0      20      10              20
Permanent Ineff=
       F       F
#Block Obstruct= 2 , 0
                              10
Bank Sta=0,10
XS Rating Curve= 0
Exp/Cntr=.3,.1

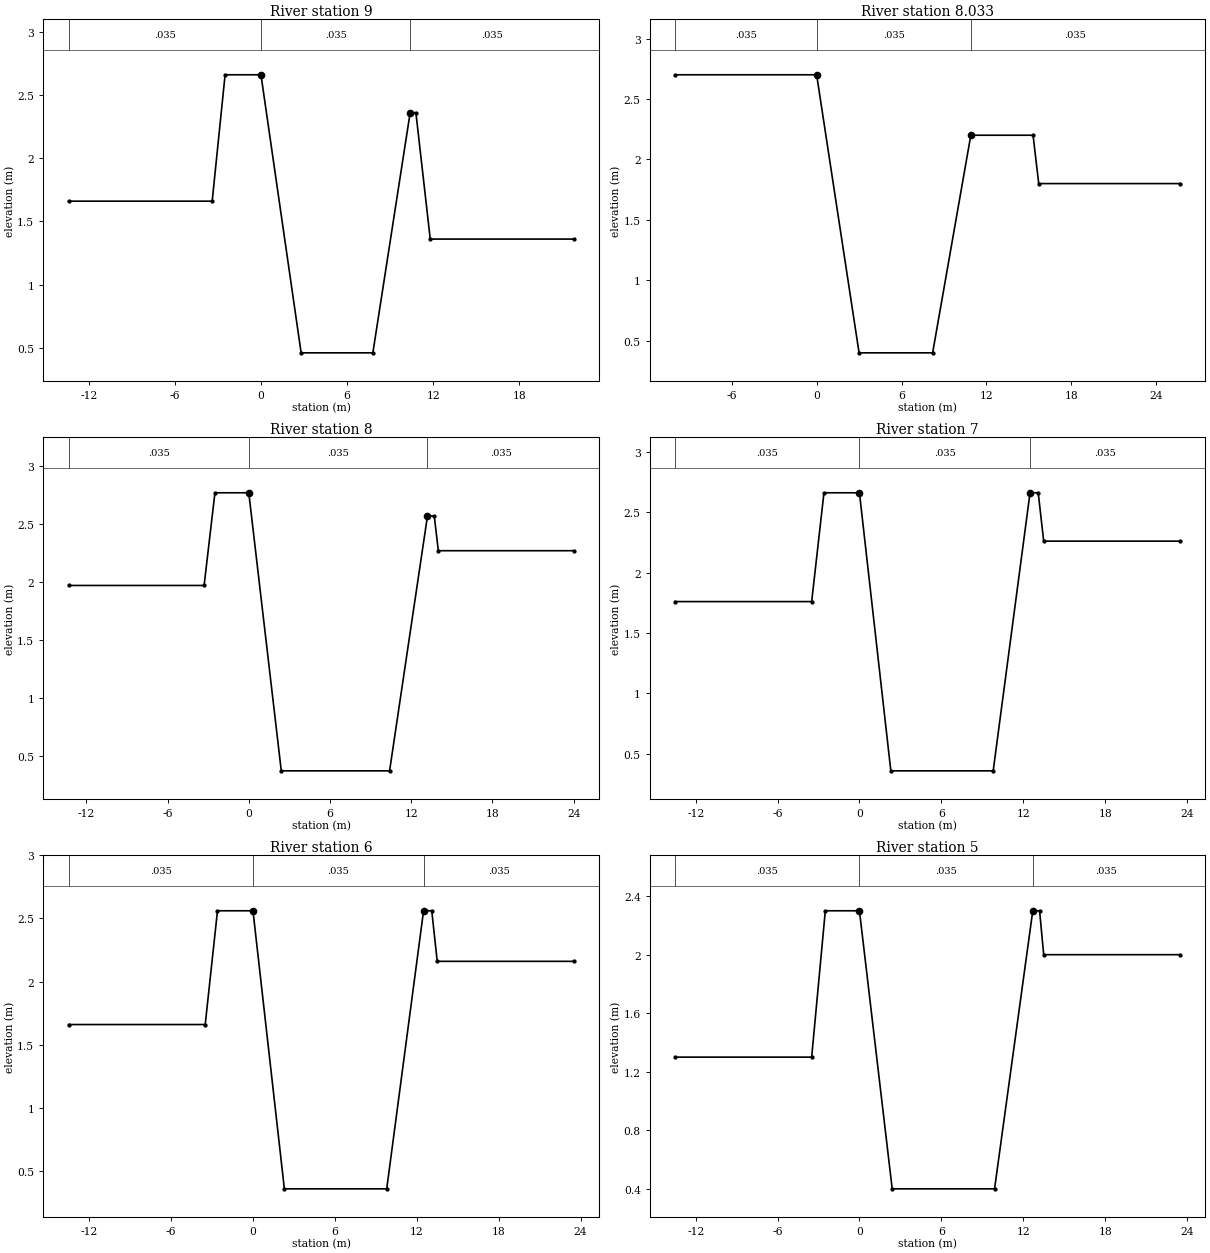
Type RM Length L Ch R = 1 ,9       ,12,12,12
#Sta/Elev= 10
   -13.4    1.66    -3.4    1.66    -2.5    2.66       0    2.66     2.8     .46
     7.8     .46    10.4    2.36    10.8    2.36    11.8    1.36    21.8    1.36
#Mann= 3 , 0 , 0
   -13.4    .035       0       0    .035       0    10.4    .035       0
#XS Ineff= 2 , 0
               0      20    10.4              20
Permanent Ineff=
       F       F
#Block Obstruct= 2 , 0
                            10.4
Bank Sta=0,10.4
XS Rating Curve= 0
Exp/Cntr=.3,.1

Type RM Length L Ch R = 1 ,8.033   ,33,33,33
#Sta/Elev= 8
     -10     2.7       0     2.7       3      .4     8.2      .4    10.9     2.2
    15.3     2.2    15.7     1.8    25.7     1.8
#Mann= 3 , 0 , 0
     -10    .035       0       0    .035       0    10.9    .035       0
#XS Ineff= 2 , 0
               0      20    10.9              20
Permanent Ineff=
       F       F
#Block Obstruct= 2 , 0
                            10.9
Bank Sta=0,10.9
XS Rating Curve= 0
Exp/Cntr=.3,.1

Type RM Length L Ch R = 1 ,8       ,50,50,50
#Sta/Elev= 10
   -13.3    1.97    -3.3    1.97    -2.5    2.77       0    2.77     2.4     .37
    10.4     .37    13.2    2.57    13.7    2.57      14    2.27      24    2.27
#Mann= 3 , 0 , 0
   -13.3    .035       0       0    .035       0    13.2    .035       0
#XS Ineff= 2 , 0
               0      20    13.2              20
Permanent Ineff=
       F       F
#Block Obstruct= 2 , 0
                            13.2
Bank Sta=0,13.2
XS Rating Curve= 0
Exp/Cntr=.3,.1

Type RM Length L Ch R = 1 ,7       ,50,50,50
#Sta/Elev= 10
   -13.5    1.76    -3.5    1.76    -2.6    2.66       0    2.66     2.3     .36
     9.8     .36    12.5    2.66    13.1    2.66    13.5    2.26    23.5    2.26
#Mann= 3 , 0 , 0
   -13.5    .035       0       0    .035       0    12.5    .035       0
#XS Ineff= 2 , 0
               0      20    12.5              20
Permanent Ineff=
       F       F
#Block Obstruct= 2 , 0
                            12.5
Bank Sta=0,12.5
XS Rating Curve= 0
Exp/Cntr=.3,.1

Type RM Length L Ch R = 1 ,6       ,50,50,50
#Sta/Elev= 10
   -13.5    1.66    -3.5    1.66    -2.6    2.56       0    2.56     2.3     .36
     9.8     .36    12.5    2.56    13.1    2.56    13.5    2.16    23.5    2.16
#Mann= 3 , 0 , 0
   -13.5    .035       0       0    .035       0    12.5    .035       0
#XS Ineff= 2 , 0
               0      20    12.5              20
Permanent Ineff=
       F       F
#Block Obstruct= 2 , 0
                            12.5
Bank Sta=0,12.5
XS Rating Curve= 0
Exp/Cntr=.3,.1

Type RM Length L Ch R = 1 ,5       ,50,50,50
#Sta/Elev= 10
   -13.5     1.3    -3.5     1.3    -2.5     2.3       0     2.3     2.4      .4
     9.9      .4    12.7     2.3    13.2     2.3    13.5       2    23.5       2
#Mann= 3 , 0 , 0
   -13.5    .035       0       0    .035       0    12.7    .035       0
#XS Ineff= 2 , 0
               0      20    12.7              20
Permanent Ineff=
       F       F
#Block Obstruct= 2 , 0
                            12.7
Bank Sta=0,12.7
XS Rating Curve= 0
Exp/Cntr=.3,.1

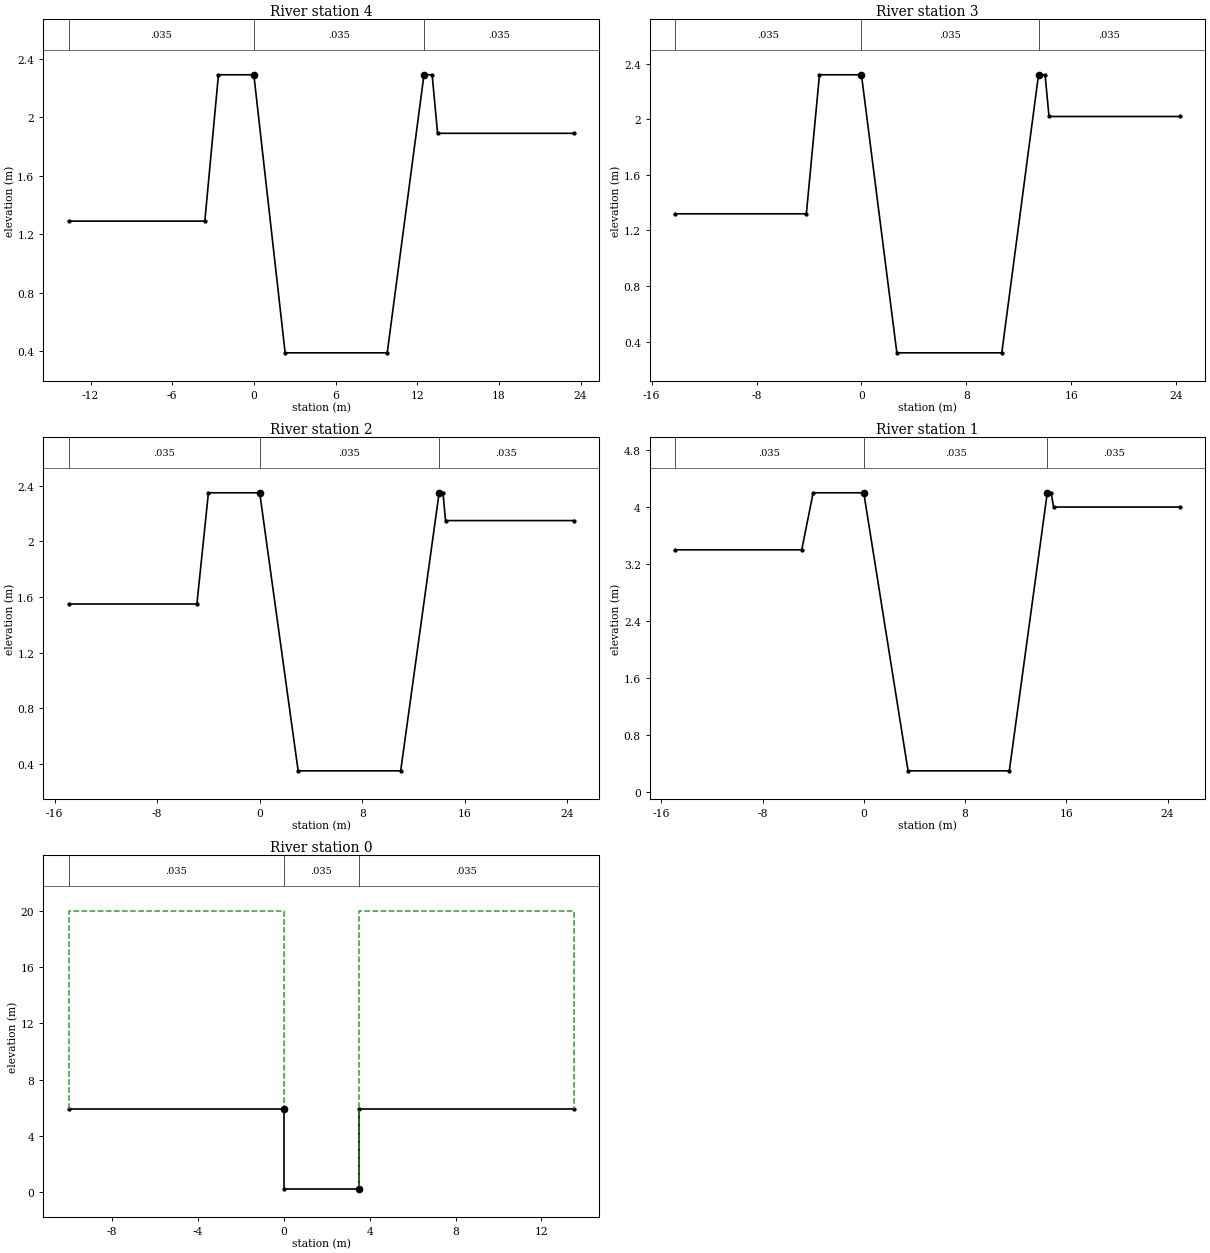
Type RM Length L Ch R = 1 ,4       ,50,50,50
#Sta/Elev= 10
   -13.6    1.29    -3.6    1.29    -2.6    2.29       0    2.29     2.3     .39
     9.8     .39    12.5    2.29    13.1    2.29    13.5    1.89    23.5    1.89
#Mann= 3 , 0 , 0
   -13.6    .035       0       0    .035       0    12.5    .035       0
#XS Ineff= 2 , 0
               0      20    12.5              20
Permanent Ineff=
       F       F
#Block Obstruct= 2 , 0
                            12.5
Bank Sta=0,12.5
XS Rating Curve= 0
Exp/Cntr=.3,.1

Type RM Length L Ch R = 1 ,3       ,50,50,50
#Sta/Elev= 10
   -14.2    1.32    -4.2    1.32    -3.2    2.32       0    2.32     2.7     .32
    10.7     .32    13.5    2.32      14    2.32    14.3    2.02    24.3    2.02
#Mann= 3 , 0 , 0
   -14.2    .035       0       0    .035       0    13.5    .035       0
#XS Ineff= 2 , 0
               0      20    13.5              20
Permanent Ineff=
       F       F
#Block Obstruct= 2 , 0
                            13.5
Bank Sta=0,13.5
XS Rating Curve= 0
Exp/Cntr=.3,.1

Type RM Length L Ch R = 1 ,2       ,50,50,50
#Sta/Elev= 10
   -14.9    1.55    -4.9    1.55      -4    2.35       0    2.35       3     .35
      11     .35      14    2.35    14.3    2.35    14.5    2.15    24.5    2.15
#Mann= 3 , 0 , 0
   -14.9    .035       0       0    .035       0      14    .035       0
#XS Ineff= 2 , 0
               0      20      14              20
Permanent Ineff=
       F       F
#Block Obstruct= 2 , 0
                              14
Bank Sta=0,14
XS Rating Curve= 0
Exp/Cntr=.3,.1

Type RM Length L Ch R = 1 ,1       ,50,50,50
#Sta/Elev= 10
   -14.9     3.4    -4.9     3.4      -4     4.2       0     4.2     3.5      .3
    11.5      .3    14.5     4.2    14.8     4.2      15       4      25       4
#Mann= 3 , 0 , 0
   -14.9    .035       0       0    .035       0    14.5    .035       0
#XS Ineff= 2 , 0
               0      20    14.5              20
Permanent Ineff=
       F       F
#Block Obstruct= 2 , 0
                            14.5
Bank Sta=0,14.5
XS Rating Curve= 0
Exp/Cntr=.3,.1

Type RM Length L Ch R = 1 ,0       ,0,0,0
#Sta/Elev= 6
     -10    5.94       0    5.94       0     .24     3.5     .24     3.5    5.94
    13.5    5.94
#Mann= 3 , 0 , 0
     -10    .035       0       0    .035       0     3.5    .035       0
#XS Ineff= 2 , 0
               0      20     3.5              20
Permanent Ineff=
       F       F
#Block Obstruct= 2 , 0
                             3.5
Bank Sta=0,3.5
XS Rating Curve= 0
Exp/Cntr=.3,.1

Chan Stop Cuts=-1