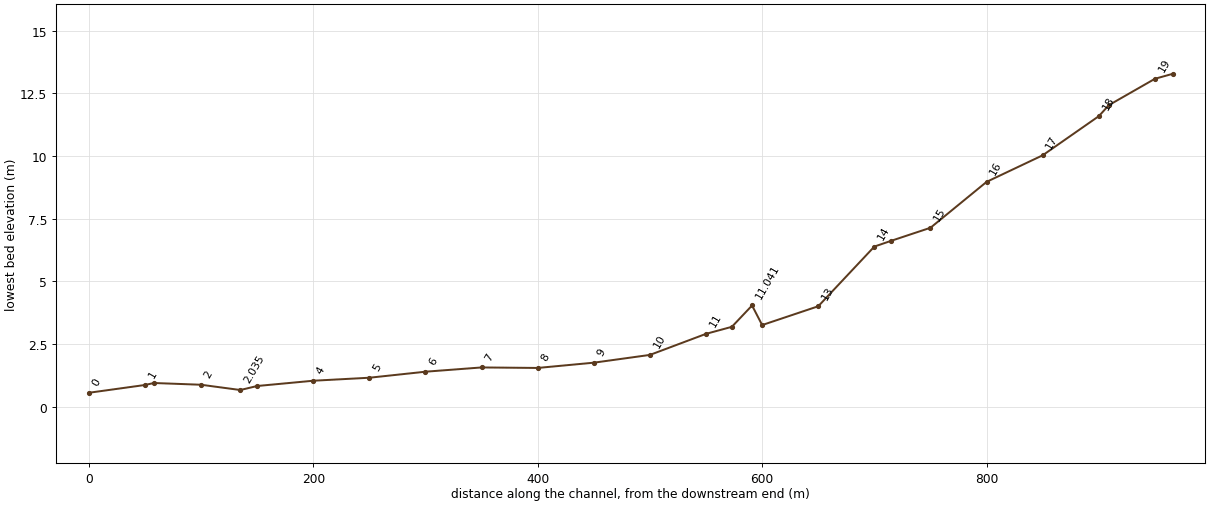
--- drg.prj (project) ---

Proj Title=dooryung
Current Plan=p01
Default Exp/Contr=.3,.1
SI Units
Geom File=g01
Flow File=f01
Plan File=p01
Y Axis Title=Elevation
X Axis Title(PF)=Main Channel Distance
X Axis Title(XS)=Station
BEGIN DESCRIPTION:
           BACK WATER COMPUTATION
      APPLICATION OF HEC-2 BY Samju Construction Engineering
      durungge-ch: 10,20,30,50,80 yr
END DESCRIPTION:
DSS Export Rating Curves= 0
DSS Export Rating Curve Sorted= 0
DSS Export Volume Flow Curves= 0
DXF OffsetX= 0
DXF OffsetY= 0
DXF ScaleX= 1
DXF ScaleY= 10

--- drg.p01 (plan) ---

Plan Title=Imported Plan 01
Version=Version 3.0.1  Mar 2001
Short Identifier=Imported Pla
Geom File=g01
Flow File=f01
Subcritical Flow
K Sum by GR= 0
Std Step Tol= 0.003
Critical Tol= 0.003
Num of Std Step Trials= 20
Max Error Tol= 0.1
Flow Tol Ratio= 0.001
Split Flow NTrial= 30
Split Flow Tol= 0.02
Split Flow Ratio= 0.02
Log Output Level= 0
Friction Slope Method= 1
Unsteady Friction Slope Method= 2
Parabolic Critical Depth
Global Vel Dist= 0 , 0 , 0
Global Log Level= 0
CheckData=True
Encroach Param=-1 ,0,0, 0
Computation Interval=1HOUR
Output Interval=1HOUR
Run HTab= 0
Run UNet= 0
Run PostProcess= 0
UNET Theta= 1
UNET ZTol= 0.02
UNET ZSATol= 0.1
UNET MxIter= 20
UNET MaxInSteps= 20
UNET DtIC= 0
UNET DtMin= 0
UNET MaxCRTS= 20
UNET WFStab= 2
UNET SFStab= 1
UNET WFX= 1
UNET SFX= 1
UNET Convert EG Bridges=-1
UNET Use Existing IB Tables=-1
Instantaneous Interval=1HOUR
Write IC File= 0
Write Velocity= 0
Write Detailed= 0

--- drg.f01 (steady flow) ---

Flow Title=Imported Flow 01
Version=Version 3.0.1  Mar 2001
Number of Profiles= 5
Profile Names=10yr,20yr,30yr,50yr,80yr
River Rch & RM=RIVER-1,Reach-1         ,19.016
    6.89    7.59       8    8.51    8.98
River Rch & RM=DOORUNGKAE,DOORUNGKAE      ,19.016
    6.89    7.59       8    8.51    8.98
Boundary for River Rch & Prof#=DOORUNGKAE,DOORUNGKAE      , 1
Up Type= 0
Dn Type= 3
Dn Slope=.001
Boundary for River Rch & Prof#=DOORUNGKAE,DOORUNGKAE      , 2
Up Type= 0
Dn Type= 3
Dn Slope=.001
Boundary for River Rch & Prof#=DOORUNGKAE,DOORUNGKAE      , 3
Up Type= 0
Dn Type= 3
Dn Slope=.001
Boundary for River Rch & Prof#=DOORUNGKAE,DOORUNGKAE      , 4
Up Type= 0
Dn Type= 3
Dn Slope=.001
Boundary for River Rch & Prof#=DOORUNGKAE,DOORUNGKAE      , 5
Up Type= 0
Dn Type= 3
Dn Slope=.001
DSS Import GetInterval= 0
DSS Import GetPeak= 0
DSS Import FillOption= 0

--- drg.g01 (geometry) ---

Geom Title=Imported Geom 01
Version=Version 3.0.1  Mar 2001

River Reach=DOORUNGKAE      ,DOORUNGKAE
Reach XY= 2
              .5             .95              .5             .05

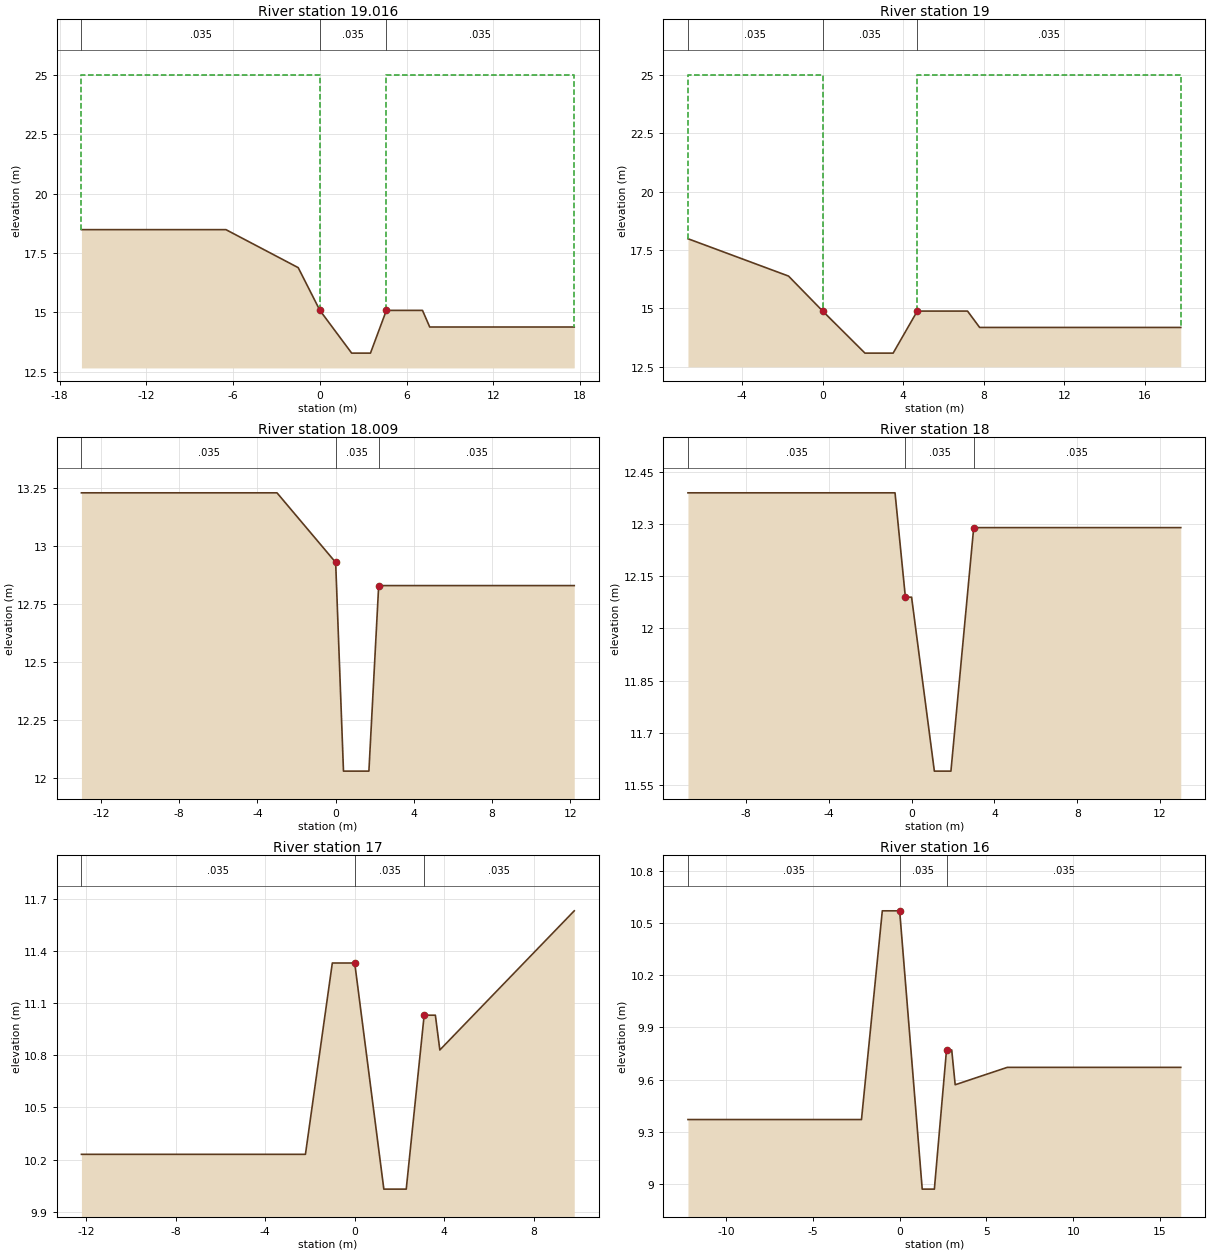
Type RM Length L Ch R = 1 ,19.016  ,16,16,16
#Sta/Elev= 10
   -16.5   18.48    -6.5   18.48    -1.5   16.88       0   15.08     2.2   13.28
     3.5   13.28     4.6   15.08     7.1   15.08     7.6   14.38    17.6   14.38
#Mann= 3 , 0 , 0
   -16.5    .035       0       0    .035       0     4.6    .035       0
#XS Ineff= 2 , 0
               0      25     4.6              25
Permanent Ineff=
       F       F
#Block Obstruct= 2 , 0
                             4.6
Bank Sta=0,4.6
XS Rating Curve= 0
Exp/Cntr=.3,.1

Type RM Length L Ch R = 1 ,19      ,41,41,41
#Sta/Elev= 9
    -6.7   17.98    -1.7   16.38       0   14.88     2.1   13.08     3.5   13.08
     4.7   14.88     7.2   14.88     7.8   14.18    17.8   14.18
#Mann= 3 , 0 , 0
    -6.7    .035       0       0    .035       0     4.7    .035       0
#XS Ineff= 2 , 0
               0      25     4.7              25
Permanent Ineff=
       F       F
#Block Obstruct= 2 , 0
                             4.7
Bank Sta=0,4.7
XS Rating Curve= 0
Exp/Cntr=.3,.1

Type RM Length L Ch R = 1 ,18.009  ,9,9,9
#Sta/Elev= 7
     -13   13.23      -3   13.23       0   12.93      .4   12.03     1.7   12.03
     2.2   12.83    12.2   12.83
#Mann= 3 , 0 , 0
     -13    .035       0       0    .035       0     2.2    .035       0
#XS Ineff= 2 , 0
               0      20     2.2              20
Permanent Ineff=
       F       F
#Block Obstruct= 2 , 0
                             2.2
Bank Sta=0,2.2
XS Rating Curve= 0
Exp/Cntr=.3,.1

Type RM Length L Ch R = 1 ,18      ,50,50,50
#Sta/Elev= 8
   -10.8   12.39     -.8   12.39     -.3   12.09       0   12.09     1.1   11.59
     1.9   11.59       3   12.29      13   12.29
#Mann= 3 , 0 , 0
   -10.8    .035       0     -.3    .035       0       3    .035       0
#XS Ineff= 2 , 0
             -.3      20       3              20
Permanent Ineff=
       F       F
#Block Obstruct= 2 , 0
             -.3               3
Bank Sta=-.3,3
XS Rating Curve= 0
Exp/Cntr=.3,.1

Type RM Length L Ch R = 1 ,17      ,50,50,50
#Sta/Elev= 11
   -12.2   10.23    -2.2   10.23      -1   11.33       0   11.33     1.3   10.03
     2.3   10.03     3.1   11.03     3.6   11.03     3.8   10.83     6.8   11.23
     9.8   11.63
#Mann= 3 , 0 , 0
   -12.2    .035       0       0    .035       0     3.1    .035       0
#XS Ineff= 2 , 0
               0      20     3.1              20
Permanent Ineff=
       F       F
#Block Obstruct= 2 , 0
                             3.1
Bank Sta=0,3.1
XS Rating Curve= 0
Exp/Cntr=.3,.1

Type RM Length L Ch R = 1 ,16      ,50,50,50
#Sta/Elev= 11
   -12.2    9.37    -2.2    9.37      -1   10.57       0   10.57     1.3    8.97
       2    8.97     2.7    9.77       3    9.77     3.2    9.57     6.2    9.67
    16.2    9.67
#Mann= 3 , 0 , 0
   -12.2    .035       0       0    .035       0     2.7    .035       0
#XS Ineff= 2 , 0
               0      20     2.7              20
Permanent Ineff=
       F       F
#Block Obstruct= 2 , 0
                             2.7
Bank Sta=0,2.7
XS Rating Curve= 0
Exp/Cntr=.3,.1

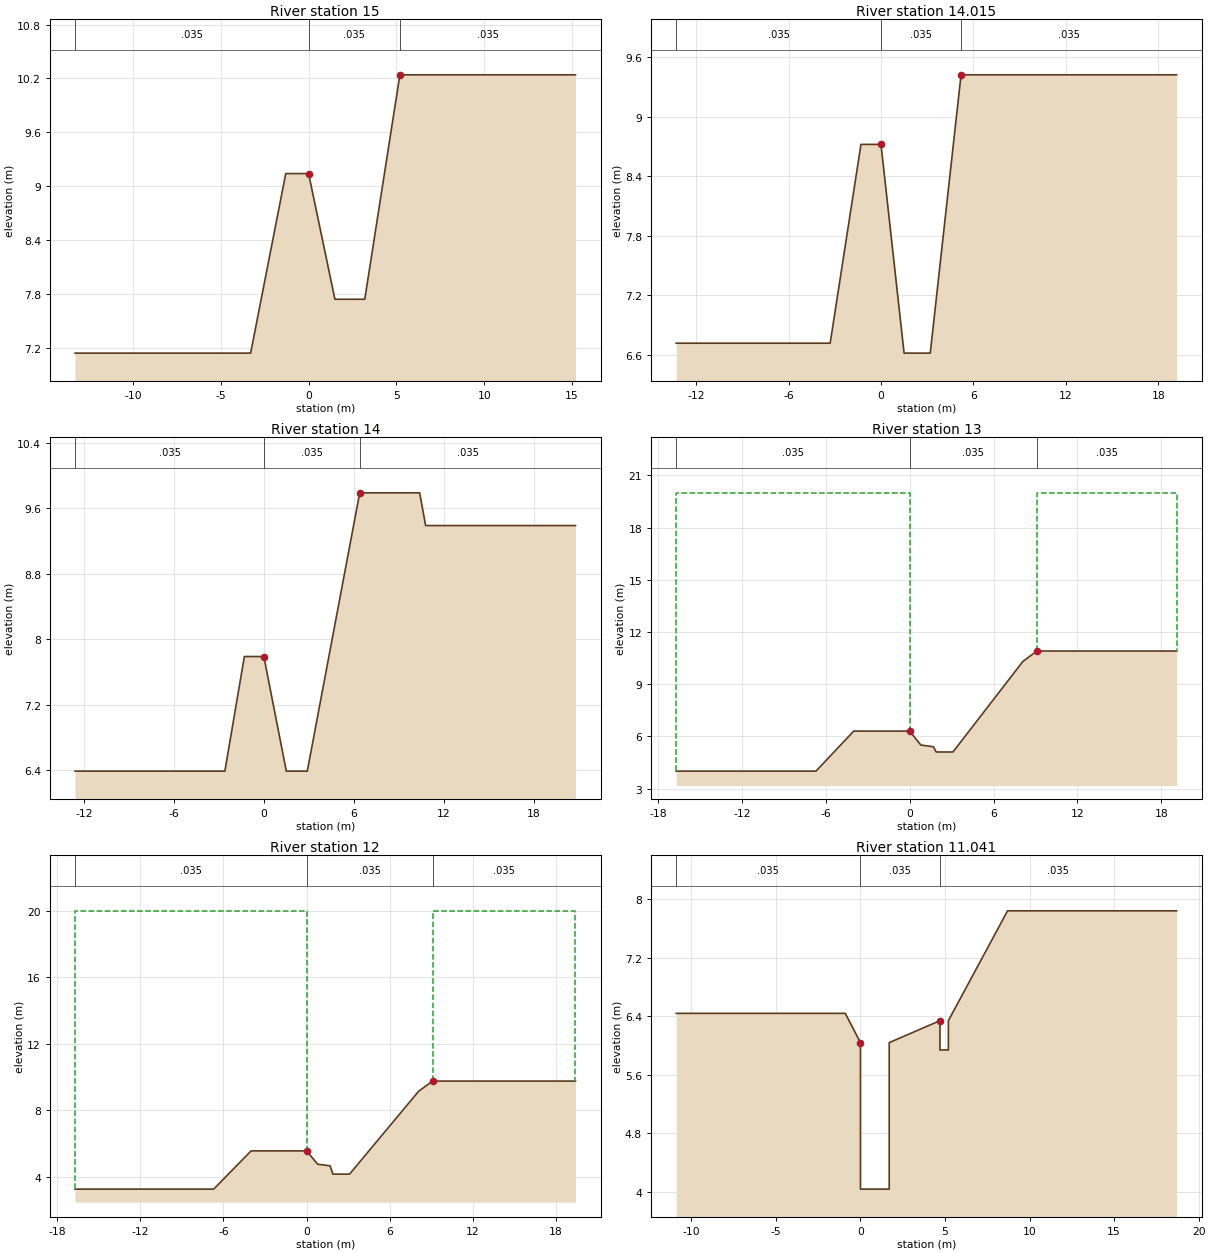
Type RM Length L Ch R = 1 ,15      ,35,35,35
#Sta/Elev= 8
   -13.3    7.14    -3.3    7.14    -1.3    9.14       0    9.14     1.5    7.74
     3.2    7.74     5.2   10.24    15.2   10.24
#Mann= 3 , 0 , 0
   -13.3    .035       0       0    .035       0     5.2    .035       0
#XS Ineff= 2 , 0
               0      20     5.2              20
Permanent Ineff=
       F       F
#Block Obstruct= 2 , 0
                             5.2
Bank Sta=0,5.2
XS Rating Curve= 0
Exp/Cntr=.3,.1

Type RM Length L Ch R = 1 ,14.015  ,15,15,15
#Sta/Elev= 9
   -13.3    6.72    -3.3    6.72    -1.3    8.72       0    8.72     1.5    6.62
     3.2    6.62     5.2    9.42     9.2    9.42    19.2    9.42
#Mann= 3 , 0 , 0
   -13.3    .035       0       0    .035       0     5.2    .035       0
#XS Ineff= 2 , 0
               0      20     5.2              20
Permanent Ineff=
       F       F
#Block Obstruct= 2 , 0
                             5.2
Bank Sta=0,5.2
XS Rating Curve= 0
Exp/Cntr=.3,.1

Type RM Length L Ch R = 1 ,14      ,50,50,50
#Sta/Elev= 10
   -12.6    6.39    -2.6    6.39    -1.3    7.79       0    7.79     1.5    6.39
     2.9    6.39     6.4    9.79    10.4    9.79    10.8    9.39    20.8    9.39
#Mann= 3 , 0 , 0
   -12.6    .035       0       0    .035       0     6.4    .035       0
#XS Ineff= 2 , 0
               0      20     6.4              20
Permanent Ineff=
       F       F
#Block Obstruct= 2 , 0
                             6.4
Bank Sta=0,6.4
XS Rating Curve= 0
Exp/Cntr=.3,.1

Type RM Length L Ch R = 1 ,13      ,50,50,50
#Sta/Elev= 11
   -16.7    4.01    -6.7    4.01      -4    6.31       0    6.31      .8    5.51
     1.7    5.41     1.9    5.11     3.1    5.11     8.1   10.31     9.1   10.91
    19.1   10.91
#Mann= 3 , 0 , 0
   -16.7    .035       0       0    .035       0     9.1    .035       0
#XS Ineff= 2 , 0
               0      20     9.1              20
Permanent Ineff=
       F       F
#Block Obstruct= 2 , 0
                             9.1
Bank Sta=0,9.1
XS Rating Curve= 0
Exp/Cntr=.3,.1

Type RM Length L Ch R = 1 ,12      ,9,9,9
#Sta/Elev= 11
   -16.7    3.26    -6.7    3.26      -4    5.56       0    5.56      .8    4.76
     1.7    4.66     1.9    4.16     3.1    4.16     8.1    9.16     9.1    9.76
    19.4    9.76
#Mann= 3 , 0 , 0
   -16.7    .035       0       0    .035       0     9.1    .035       0
#XS Ineff= 2 , 0
               0      20     9.1              20
Permanent Ineff=
       F       F
#Block Obstruct= 2 , 0
                             9.1
Bank Sta=0,9.1
XS Rating Curve= 0
Exp/Cntr=.3,.1

Type RM Length L Ch R = 1 ,11.041  ,18,18,18
#Sta/Elev= 12
   -10.9    6.44     -.9    6.44       0    6.04       0    4.04     1.7    4.04
     1.7    6.04     4.7    6.34     4.7    5.94     5.2    5.94     5.2    6.34
     8.7    7.84    18.7    7.84
#Mann= 3 , 0 , 0
   -10.9    .035       0       0    .035       0     4.7    .035       0
#XS Ineff= 2 , 0
               0      20     4.7              20
Permanent Ineff=
       F       F
#Block Obstruct= 2 , 0
                             4.7
Bank Sta=0,4.7
XS Rating Curve= 0
Exp/Cntr=.3,.1

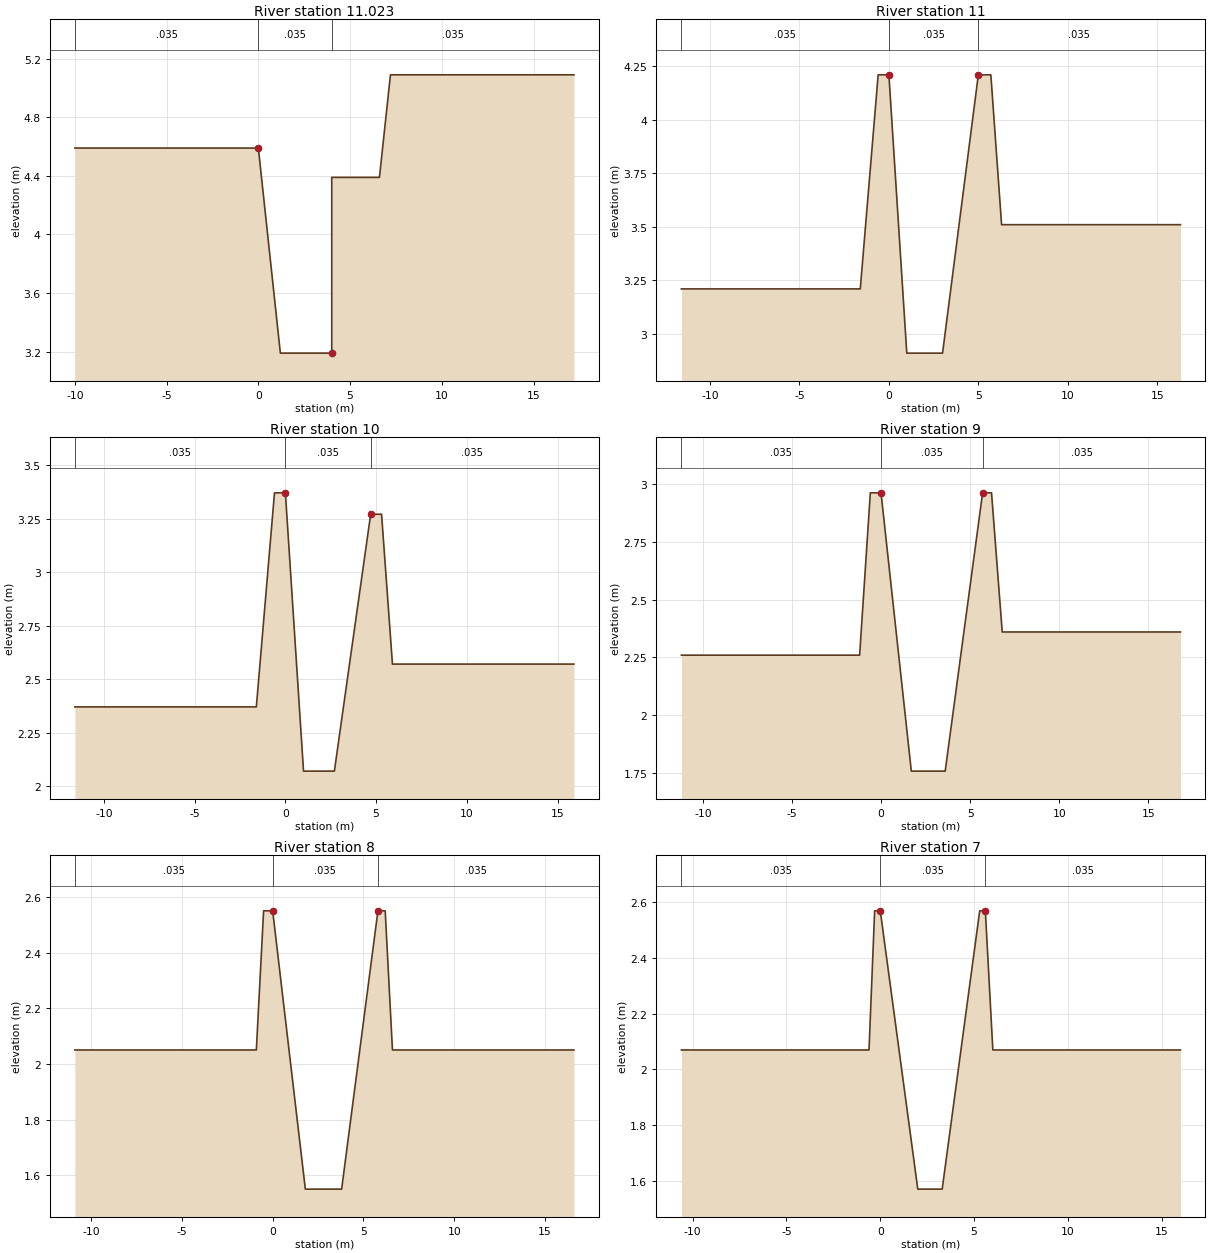
Type RM Length L Ch R = 1 ,11.023  ,23,23,23
#Sta/Elev= 8
     -10    4.59       0    4.59     1.2    3.19       4    3.19       4    4.39
     6.6    4.39     7.2    5.09    17.2    5.09
#Mann= 3 , 0 , 0
     -10    .035       0       0    .035       0       4    .035       0
#XS Ineff= 2 , 0
               0      20       4              20
Permanent Ineff=
       F       F
#Block Obstruct= 2 , 0
                               4
Bank Sta=0,4
XS Rating Curve= 0
Exp/Cntr=.3,.1

Type RM Length L Ch R = 1 ,11      ,50,50,50
#Sta/Elev= 10
   -11.6    3.21    -1.6    3.21     -.6    4.21       0    4.21       1    2.91
       3    2.91       5    4.21     5.7    4.21     6.3    3.51    16.3    3.51
#Mann= 3 , 0 , 0
   -11.6    .035       0       0    .035       0       5    .035       0
#XS Ineff= 2 , 0
               0      20       5              20
Permanent Ineff=
       F       F
#Block Obstruct= 2 , 0
                               5
Bank Sta=0,5
XS Rating Curve= 0
Exp/Cntr=.3,.1

Type RM Length L Ch R = 1 ,10      ,50,50,50
#Sta/Elev= 10
   -11.6    2.37    -1.6    2.37     -.6    3.37       0    3.37       1    2.07
     2.7    2.07     4.7    3.27     5.3    3.27     5.9    2.57    15.9    2.57
#Mann= 3 , 0 , 0
   -11.6    .035       0       0    .035       0     4.7    .035       0
#XS Ineff= 2 , 0
               0      20     4.7              20
Permanent Ineff=
       F       F
#Block Obstruct= 2 , 0
                             4.7
Bank Sta=0,4.7
XS Rating Curve= 0
Exp/Cntr=.3,.1

Type RM Length L Ch R = 1 ,9       ,50,50,50
#Sta/Elev= 10
   -11.2    2.26    -1.2    2.26     -.6    2.96       0    2.96     1.7    1.76
     3.6    1.76     5.7    2.96     6.2    2.96     6.8    2.36    16.8    2.36
#Mann= 3 , 0 , 0
   -11.2    .035       0       0    .035       0     5.7    .035       0
#XS Ineff= 2 , 0
               0      20     5.7              20
Permanent Ineff=
       F       F
#Block Obstruct= 2 , 0
                             5.7
Bank Sta=0,5.7
XS Rating Curve= 0
Exp/Cntr=.3,.1

Type RM Length L Ch R = 1 ,8       ,50,50,50
#Sta/Elev= 10
   -10.9    2.05     -.9    2.05     -.5    2.55       0    2.55     1.8    1.55
     3.8    1.55     5.8    2.55     6.2    2.55     6.6    2.05    16.6    2.05
#Mann= 3 , 0 , 0
   -10.9    .035       0       0    .035       0     5.8    .035       0
#XS Ineff= 2 , 0
               0      20     5.8              20
Permanent Ineff=
       F       F
#Block Obstruct= 2 , 0
                             5.8
Bank Sta=0,5.8
XS Rating Curve= 0
Exp/Cntr=.3,.1

Type RM Length L Ch R = 1 ,7       ,50,50,50
#Sta/Elev= 10
   -10.6    2.07     -.6    2.07     -.3    2.57       0    2.57       2    1.57
     3.3    1.57     5.3    2.57     5.6    2.57       6    2.07      16    2.07
#Mann= 3 , 0 , 0
   -10.6    .035       0       0    .035       0     5.6    .035       0
#XS Ineff= 2 , 0
               0      20     5.6              20
Permanent Ineff=
       F       F
#Block Obstruct= 2 , 0
                             5.6
Bank Sta=0,5.6
XS Rating Curve= 0
Exp/Cntr=.3,.1

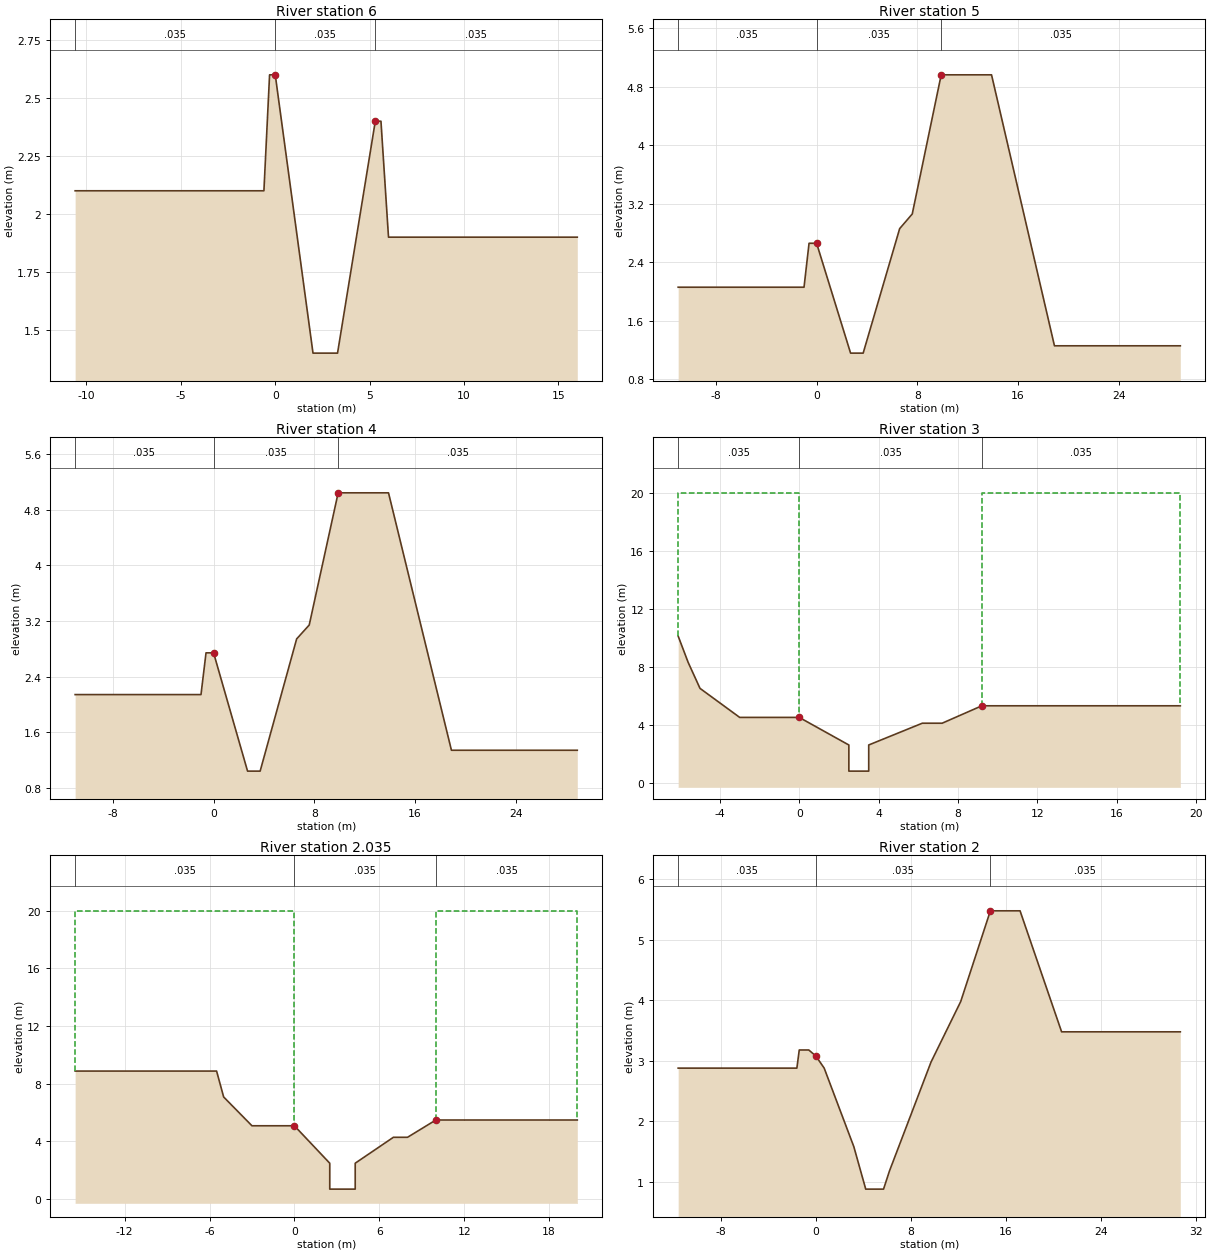
Type RM Length L Ch R = 1 ,6       ,50,50,50
#Sta/Elev= 10
   -10.6     2.1     -.6     2.1     -.3     2.6       0     2.6       2     1.4
     3.3     1.4     5.3     2.4     5.6     2.4       6     1.9      16     1.9
#Mann= 3 , 0 , 0
   -10.6    .035       0       0    .035       0     5.3    .035       0
#XS Ineff= 2 , 0
               0      20     5.3              20
Permanent Ineff=
       F       F
#Block Obstruct= 2 , 0
                             5.3
Bank Sta=0,5.3
XS Rating Curve= 0
Exp/Cntr=.3,.1

Type RM Length L Ch R = 1 ,5       ,50,50,50
#Sta/Elev= 12
     -11    2.06      -1    2.06     -.6    2.66       0    2.66     2.7    1.16
     3.7    1.16     6.6    2.86     7.6    3.06     9.9    4.96    13.9    4.96
    18.9    1.26    28.9    1.26
#Mann= 3 , 0 , 0
     -11    .035       0       0    .035       0     9.9    .035       0
#XS Ineff= 2 , 0
               0      20     9.9              20
Permanent Ineff=
       F       F
#Block Obstruct= 2 , 0
                             9.9
Bank Sta=0,9.9
XS Rating Curve= 0
Exp/Cntr=.3,.1

Type RM Length L Ch R = 1 ,4       ,50,50,50
#Sta/Elev= 12
     -11    2.14      -1    2.14     -.6    2.74       0    2.74     2.7    1.04
     3.7    1.04     6.6    2.94     7.6    3.14     9.9    5.04    13.9    5.04
    18.9    1.34    28.9    1.34
#Mann= 3 , 0 , 0
     -11    .035       0       0    .035       0     9.9    .035       0
#XS Ineff= 2 , 0
               0      20     9.9              20
Permanent Ineff=
       F       F
#Block Obstruct= 2 , 0
                             9.9
Bank Sta=0,9.9
XS Rating Curve= 0
Exp/Cntr=.3,.1

Type RM Length L Ch R = 1 ,3       ,15,15,15
#Sta/Elev= 13
    -6.1   10.13    -5.6    8.33      -5    6.53      -3    4.53       0    4.53
     2.5    2.63     2.5     .83     3.5     .83     3.5    2.63     6.2    4.13
     7.2    4.13     9.2    5.33    19.2    5.33
#Mann= 3 , 0 , 0
    -6.1    .035       0       0    .035       0     9.2    .035       0
#XS Ineff= 2 , 0
               0      20     9.2              20
Permanent Ineff=
       F       F
#Block Obstruct= 2 , 0
                             9.2
Bank Sta=0,9.2
XS Rating Curve= 0
Exp/Cntr=.3,.1

Type RM Length L Ch R = 1 ,2.035   ,35,35,35
#Sta/Elev= 13
   -15.5    8.87    -5.5    8.87      -5    7.07      -3    5.07       0    5.07
     2.5    2.47     2.5     .67     4.3     .67     4.3    2.47       7    4.27
       8    4.27      10    5.47      20    5.47
#Mann= 3 , 0 , 0
   -15.5    .035       0       0    .035       0      10    .035       0
#XS Ineff= 2 , 0
               0      20      10              20
Permanent Ineff=
       F       F
#Block Obstruct= 2 , 0
                              10
Bank Sta=0,10
XS Rating Curve= 0
Exp/Cntr=.3,.1

Type RM Length L Ch R = 1 ,2       ,42,42,42
#Sta/Elev= 16
   -11.6    2.88    -1.6    2.88    -1.4    3.18     -.6    3.18       0    3.08
      .7    2.88     3.2    1.58     4.2     .88     5.7     .88     6.2    1.18
     9.7    2.98    12.2    3.98    14.7    5.48    17.2    5.48    20.7    3.48
    30.7    3.48
#Mann= 3 , 0 , 0
   -11.6    .035       0       0    .035       0    14.7    .035       0
#XS Ineff= 2 , 0
               0      20    14.7              20
Permanent Ineff=
       F       F
#Block Obstruct= 2 , 0
                            14.7
Bank Sta=0,14.7
XS Rating Curve= 0
Exp/Cntr=.3,.1

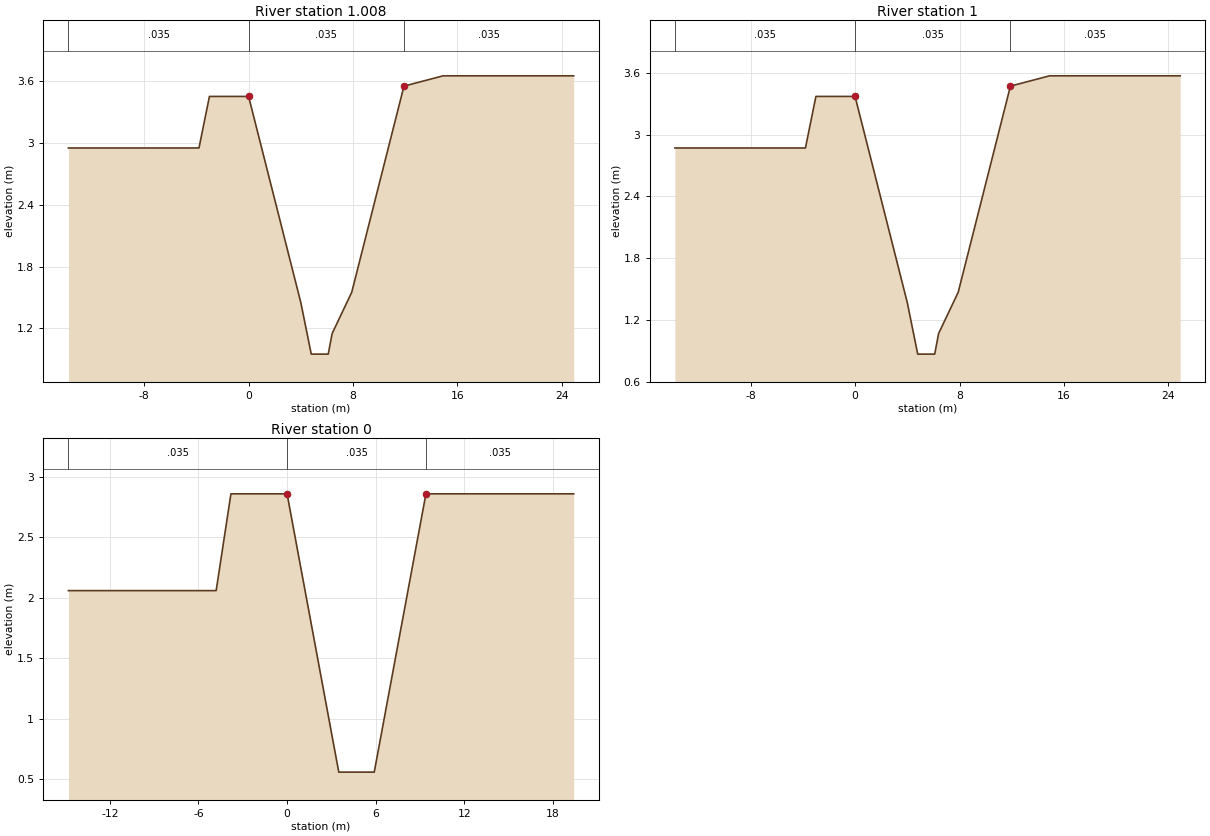
Type RM Length L Ch R = 1 ,1.008   ,8,8,8
#Sta/Elev= 12
   -13.8    2.95    -3.8    2.95      -3    3.45       0    3.45       4    1.45
     4.8     .95     6.1     .95     6.4    1.15     7.9    1.55    11.9    3.55
    14.9    3.65    24.9    3.65
#Mann= 3 , 0 , 0
   -13.8    .035       0       0    .035       0    11.9    .035       0
#XS Ineff= 2 , 0
               0      20    11.9              20
Permanent Ineff=
       F       F
#Block Obstruct= 2 , 0
                            11.9
Bank Sta=0,11.9
XS Rating Curve= 0
Exp/Cntr=.3,.1

Type RM Length L Ch R = 1 ,1       ,50,50,50
#Sta/Elev= 12
   -13.8    2.87    -3.8    2.87      -3    3.37       0    3.37       4    1.37
     4.8     .87     6.1     .87     6.4    1.07     7.9    1.47    11.9    3.47
    14.9    3.57    24.9    3.57
#Mann= 3 , 0 , 0
   -13.8    .035       0       0    .035       0    11.9    .035       0
#XS Ineff= 2 , 0
               0      20    11.9              20
Permanent Ineff=
       F       F
#Block Obstruct= 2 , 0
                            11.9
Bank Sta=0,11.9
XS Rating Curve= 0
Exp/Cntr=.3,.1

Type RM Length L Ch R = 1 ,0       ,0,0,0
#Sta/Elev= 9
   -14.8    2.06    -4.8    2.06    -3.8    2.86      -3    2.86       0    2.86
     3.5     .56     5.9     .56     9.4    2.86    19.4    2.86
#Mann= 3 , 0 , 0
   -14.8    .035       0       0    .035       0     9.4    .035       0
#XS Ineff= 2 , 0
               0      20     9.4              20
Permanent Ineff=
       F       F
#Block Obstruct= 2 , 0
                             9.4
Bank Sta=0,9.4
XS Rating Curve= 0
Exp/Cntr=.3,.1

Chan Stop Cuts=-1