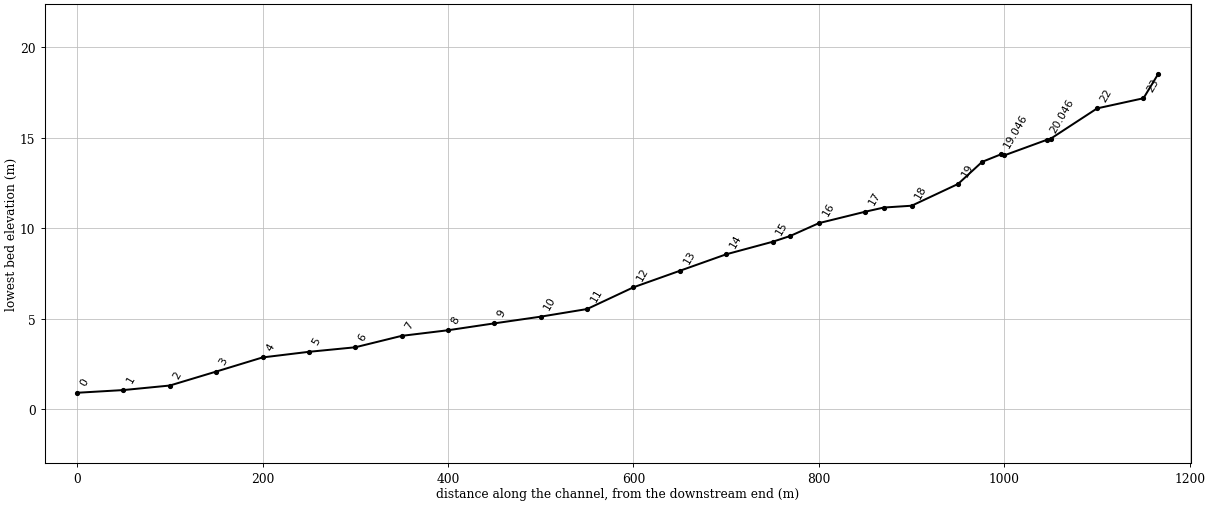
--- HDC.prj (project) ---

Proj Title=HWADUCK
Current Plan=p01
Default Exp/Contr=.3,.1
SI Units
Geom File=g01
Flow File=f01
Plan File=p01
Y Axis Title=Elevation
X Axis Title(PF)=Main Channel Distance
X Axis Title(XS)=Station
BEGIN DESCRIPTION:
           BACK WATER COMPUTATION
      APPLICATION OF HEC-2 BY Samju Construction Engineering
      whadeuk-ch: 10,20,30,50,80 yr
END DESCRIPTION:
DSS Export Rating Curves= 0
DSS Export Rating Curve Sorted= 0
DSS Export Volume Flow Curves= 0
DXF OffsetX= 0
DXF OffsetY= 0
DXF ScaleX= 1
DXF ScaleY= 10

--- HDC.p01 (plan) ---

Plan Title=Imported Plan 01
Version=Version 3.0.1  Mar 2001
Short Identifier=Imported Pla
Geom File=g01
Flow File=f01
Subcritical Flow
K Sum by GR= 0
Std Step Tol= 0.003
Critical Tol= 0.003
Num of Std Step Trials= 20
Max Error Tol= 0.1
Flow Tol Ratio= 0.001
Split Flow NTrial= 30
Split Flow Tol= 0.02
Split Flow Ratio= 0.02
Log Output Level= 0
Friction Slope Method= 1
Unsteady Friction Slope Method= 2
Parabolic Critical Depth
Global Vel Dist= 0 , 0 , 0
Global Log Level= 0
CheckData=True
Encroach Param=-1 ,0,0, 0
Computation Interval=1HOUR
Output Interval=1HOUR
Run HTab= 0
Run UNet= 0
Run PostProcess= 0
UNET Theta= 1
UNET ZTol= 0.02
UNET ZSATol= 0.1
UNET MxIter= 20
UNET MaxInSteps= 20
UNET DtIC= 0
UNET DtMin= 0
UNET MaxCRTS= 20
UNET WFStab= 2
UNET SFStab= 1
UNET WFX= 1
UNET SFX= 1
UNET Convert EG Bridges=-1
UNET Use Existing IB Tables=-1
Instantaneous Interval=1HOUR
Write IC File= 0
Write Velocity= 0
Write Detailed= 0

--- HDC.f01 (steady flow) ---

Flow Title=Imported Flow 01
Version=Version 3.0.1  Mar 2001
Number of Profiles= 5
Profile Names=10YR,20YR,30YR,50YR,80RY
River Rch & RM=RIVER-1,Reach-1         ,23.016
   10.69   11.77   12.41   13.21   13.95
River Rch & RM=HWADUCK,HWADUCK         ,23.016
   10.69   11.77   12.41   13.21   13.95
Boundary for River Rch & Prof#=HWADUCK,HWADUCK         , 1
Up Type= 0
Dn Type= 3
Dn Slope=.015
Boundary for River Rch & Prof#=HWADUCK,HWADUCK         , 2
Up Type= 0
Dn Type= 3
Dn Slope=.015
Boundary for River Rch & Prof#=HWADUCK,HWADUCK         , 3
Up Type= 0
Dn Type= 3
Dn Slope=.015
Boundary for River Rch & Prof#=HWADUCK,HWADUCK         , 4
Up Type= 0
Dn Type= 3
Dn Slope=.015
Boundary for River Rch & Prof#=HWADUCK,HWADUCK         , 5
Up Type= 0
Dn Type= 3
Dn Slope=.015
DSS Import GetInterval= 0
DSS Import GetPeak= 0
DSS Import FillOption= 0

--- HDC.g01 (geometry) ---

Geom Title=Imported Geom 01
Version=Version 3.0.1  Mar 2001

River Reach=HWADUCK         ,HWADUCK
Reach XY= 2
              .5             .95              .5             .05

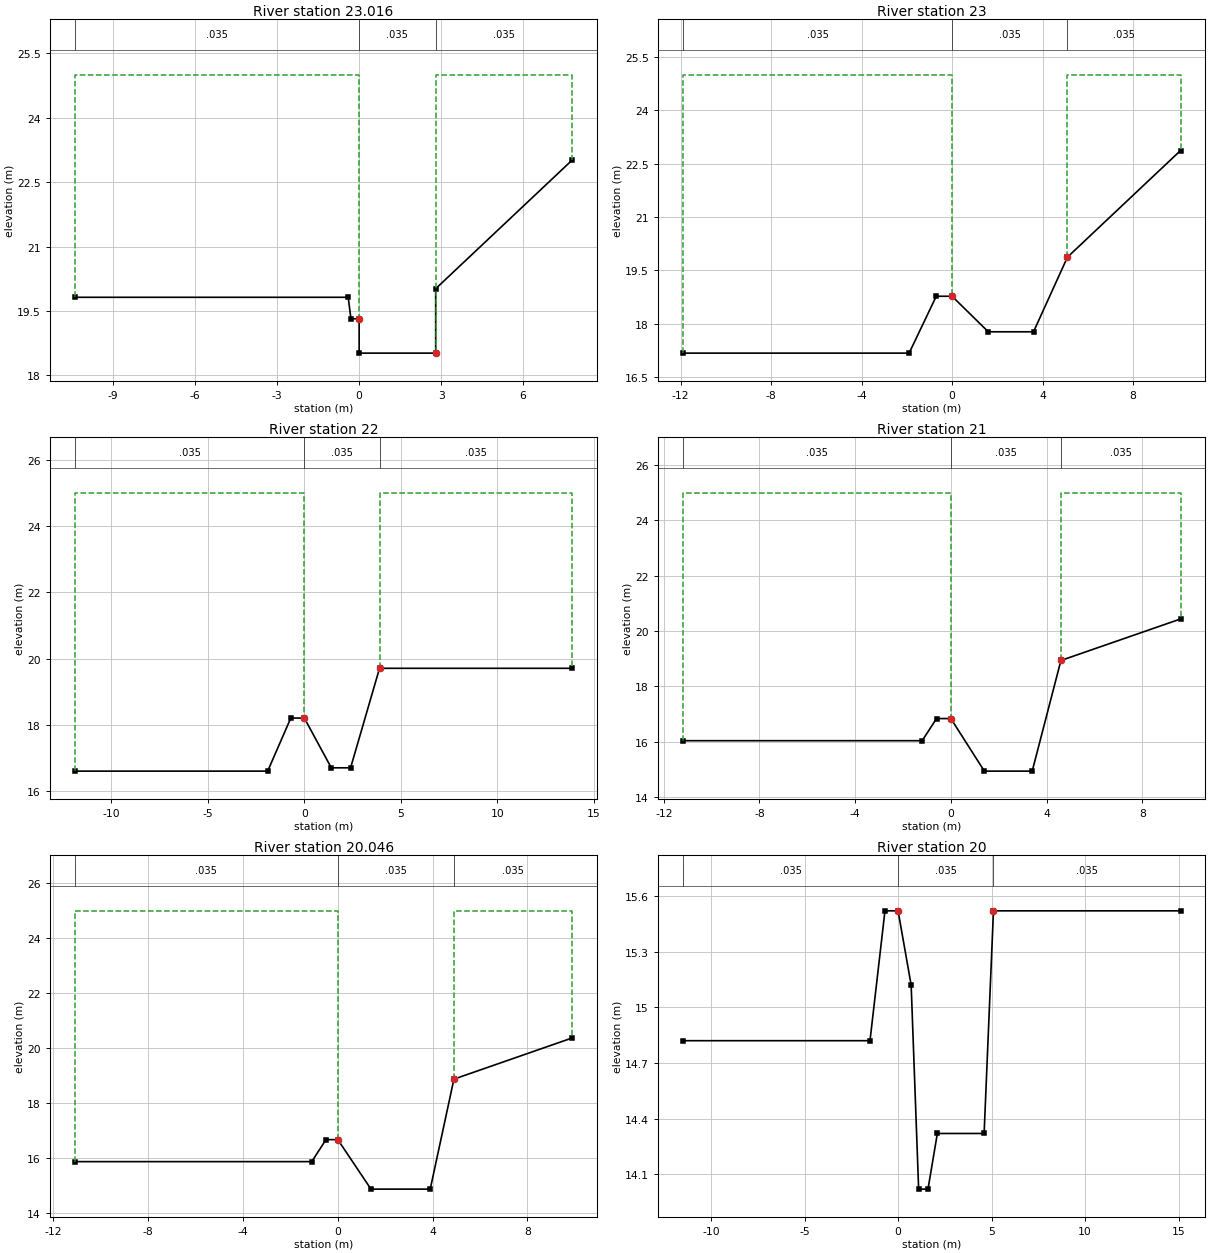
Type RM Length L Ch R = 1 ,23.016  ,16,16,16
#Sta/Elev= 8
   -10.4   19.82     -.4   19.82     -.3   19.32       0   19.32       0   18.52
     2.8   18.52     2.8   20.02     7.8   23.02
#Mann= 3 , 0 , 0
   -10.4    .035       0       0    .035       0     2.8    .035       0
#XS Ineff= 2 , 0
               0      25     2.8              25
Permanent Ineff=
       F       F
#Block Obstruct= 2 , 0
                             2.8
Bank Sta=0,2.8
XS Rating Curve= 0
Exp/Cntr=.3,.1

Type RM Length L Ch R = 1 ,23      ,50,50,50
#Sta/Elev= 8
   -11.9   17.17    -1.9   17.17     -.7   18.77       0   18.77     1.6   17.77
     3.6   17.77     5.1   19.87    10.1   22.87
#Mann= 3 , 0 , 0
   -11.9    .035       0       0    .035       0     5.1    .035       0
#XS Ineff= 2 , 0
               0      25     5.1              25
Permanent Ineff=
       F       F
#Block Obstruct= 2 , 0
                             5.1
Bank Sta=0,5.1
XS Rating Curve= 0
Exp/Cntr=.3,.1

Type RM Length L Ch R = 1 ,22      ,50,50,50
#Sta/Elev= 8
   -11.9   16.61    -1.9   16.61     -.7   18.21       0   18.21     1.4   16.71
     2.4   16.71     3.9   19.71    13.9   19.71
#Mann= 3 , 0 , 0
   -11.9    .035       0       0    .035       0     3.9    .035       0
#XS Ineff= 2 , 0
               0      25     3.9              25
Permanent Ineff=
       F       F
#Block Obstruct= 2 , 0
                             3.9
Bank Sta=0,3.9
XS Rating Curve= 0
Exp/Cntr=.3,.1

Type RM Length L Ch R = 1 ,21      ,4,4,4
#Sta/Elev= 8
   -11.2   16.04    -1.2   16.04     -.6   16.84       0   16.84     1.4   14.94
     3.4   14.94     4.6   18.94     9.6   20.44
#Mann= 3 , 0 , 0
   -11.2    .035       0       0    .035       0     4.6    .035       0
#XS Ineff= 2 , 0
               0      25     4.6              25
Permanent Ineff=
       F       F
#Block Obstruct= 2 , 0
                             4.6
Bank Sta=0,4.6
XS Rating Curve= 0
Exp/Cntr=.3,.1

Type RM Length L Ch R = 1 ,20.046  ,46,46,46
#Sta/Elev= 8
   -11.1   15.88    -1.1   15.88     -.5   16.68       0   16.68     1.4   14.88
     3.9   14.88     4.9   18.88     9.9   20.38
#Mann= 3 , 0 , 0
   -11.1    .035       0       0    .035       0     4.9    .035       0
#XS Ineff= 2 , 0
               0      25     4.9              25
Permanent Ineff=
       F       F
#Block Obstruct= 2 , 0
                             4.9
Bank Sta=0,4.9
XS Rating Curve= 0
Exp/Cntr=.3,.1

Type RM Length L Ch R = 1 ,20      ,4,4,4
#Sta/Elev= 11
   -11.5   14.82    -1.5   14.82     -.7   15.52       0   15.52      .7   15.12
     1.1   14.02     1.6   14.02     2.1   14.32     4.6   14.32     5.1   15.52
    15.1   15.52
#Mann= 3 , 0 , 0
   -11.5    .035       0       0    .035       0     5.1    .035       0
#XS Ineff= 2 , 0
               0      25     5.1              25
Permanent Ineff=
       F       F
#Block Obstruct= 2 , 0
                             5.1
Bank Sta=0,5.1
XS Rating Curve= 0
Exp/Cntr=.3,.1

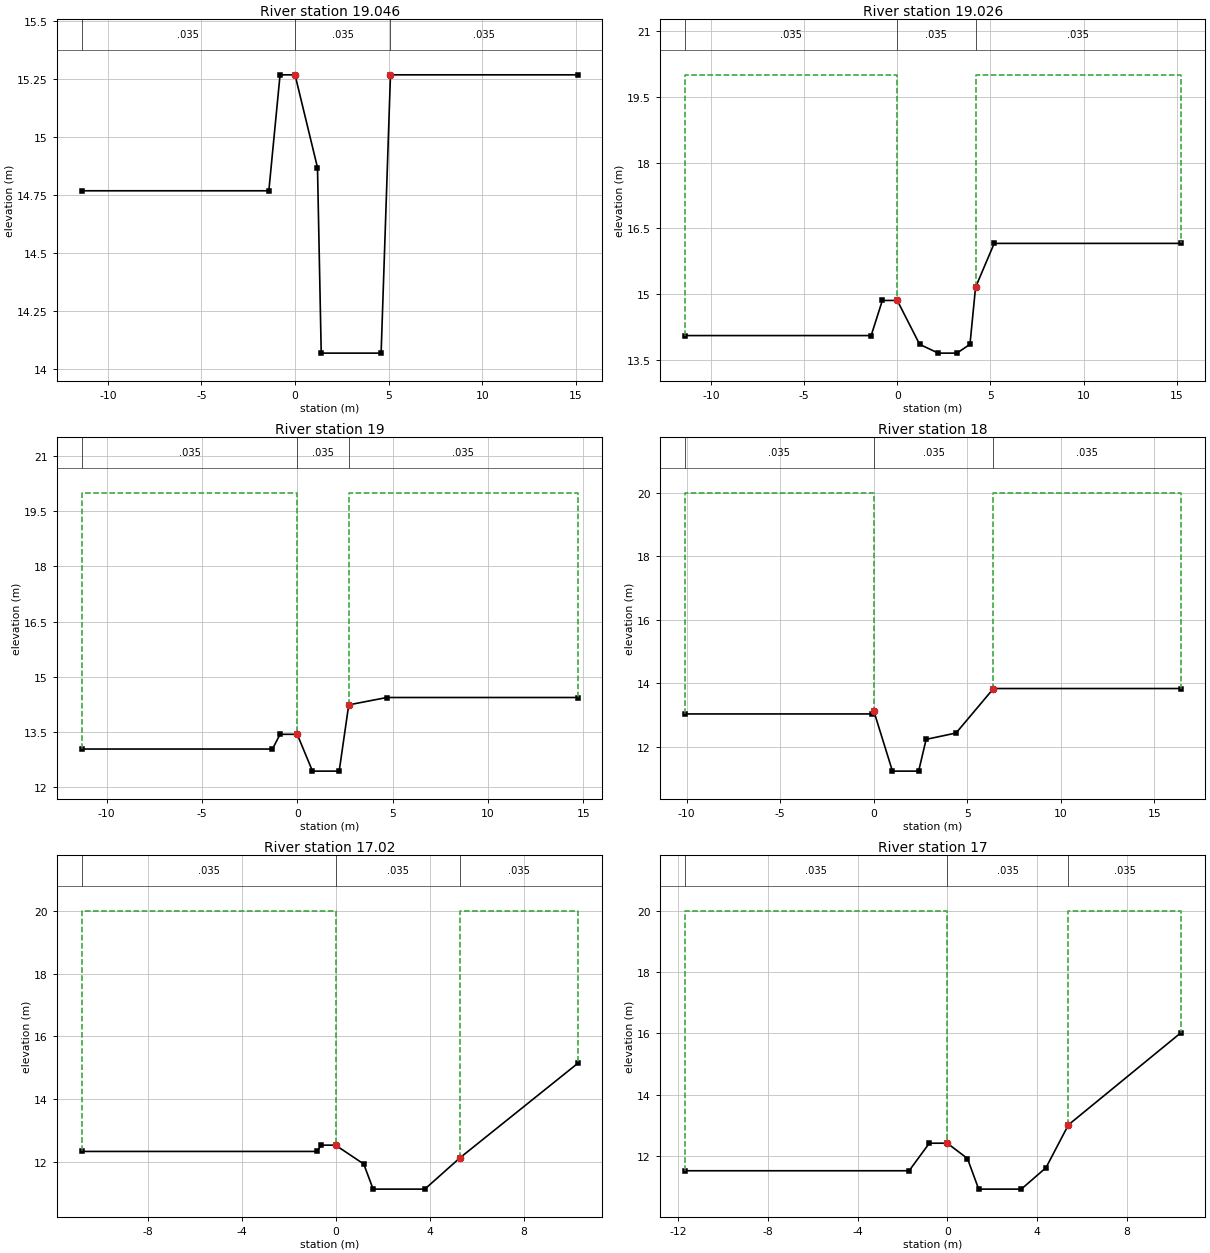
Type RM Length L Ch R = 1 ,19.046  ,20,20,20
#Sta/Elev= 9
   -11.4   14.77    -1.4   14.77     -.8   15.27       0   15.27     1.2   14.87
     1.4   14.07     4.6   14.07     5.1   15.27    15.1   15.27
#Mann= 3 , 0 , 0
   -11.4    .035       0       0    .035       0     5.1    .035       0
#XS Ineff= 2 , 0
               0      25     5.1              25
Permanent Ineff=
       F       F
#Block Obstruct= 2 , 0
                             5.1
Bank Sta=0,5.1
XS Rating Curve= 0
Exp/Cntr=.3,.1

Type RM Length L Ch R = 1 ,19.026  ,26,26,26
#Sta/Elev= 11
   -11.4   14.06    -1.4   14.06     -.8   14.86       0   14.86     1.2   13.86
     2.2   13.66     3.2   13.66     3.9   13.86     4.2   15.16     5.2   16.16
    15.2   16.16
#Mann= 3 , 0 , 0
   -11.4    .035       0       0    .035       0     4.2    .035       0
#XS Ineff= 2 , 0
               0      20     4.2              20
Permanent Ineff=
       F       F
#Block Obstruct= 2 , 0
                             4.2
Bank Sta=0,4.2
XS Rating Curve= 0
Exp/Cntr=.3,.1

Type RM Length L Ch R = 1 ,19      ,50,50,50
#Sta/Elev= 9
   -11.3   13.04    -1.3   13.04     -.9   13.44       0   13.44      .8   12.44
     2.2   12.44     2.7   14.24     4.7   14.44    14.7   14.44
#Mann= 3 , 0 , 0
   -11.3    .035       0       0    .035       0     2.7    .035       0
#XS Ineff= 2 , 0
               0      20     2.7              20
Permanent Ineff=
       F       F
#Block Obstruct= 2 , 0
                             4.2
Bank Sta=0,2.7
XS Rating Curve= 0
Exp/Cntr=.3,.1

Type RM Length L Ch R = 1 ,18      ,30,30,30
#Sta/Elev= 9
   -10.1   13.04     -.1   13.04       0   13.14       1   11.24     2.4   11.24
     2.8   12.24     4.4   12.44     6.4   13.84    16.4   13.84
#Mann= 3 , 0 , 0
   -10.1    .035       0       0    .035       0     6.4    .035       0
#XS Ineff= 2 , 0
               0      20     6.4              20
Permanent Ineff=
       F       F
#Block Obstruct= 2 , 0
                             6.4
Bank Sta=0,6.4
XS Rating Curve= 0
Exp/Cntr=.3,.1

Type RM Length L Ch R = 1 ,17.02   ,20,20,20
#Sta/Elev= 9
   -10.8   12.34     -.8   12.34     -.6   12.54       0   12.54     1.2   11.94
     1.6   11.14     3.8   11.14     5.3   12.14    10.3   15.14
#Mann= 3 , 0 , 0
   -10.8    .035       0       0    .035       0     5.3    .035       0
#XS Ineff= 2 , 0
               0      20     5.3              20
Permanent Ineff=
       F       F
#Block Obstruct= 2 , 0
                             5.3
Bank Sta=0,5.3
XS Rating Curve= 0
Exp/Cntr=.3,.1

Type RM Length L Ch R = 1 ,17      ,50,50,50
#Sta/Elev= 10
   -11.7   11.51    -1.7   11.51     -.8   12.41       0   12.41      .9   11.91
     1.4   10.91     3.3   10.91     4.4   11.61     5.4   13.01    10.4   16.01
#Mann= 3 , 0 , 0
   -11.7    .035       0       0    .035       0     5.4    .035       0
#XS Ineff= 2 , 0
               0      20     5.4              20
Permanent Ineff=
       F       F
#Block Obstruct= 2 , 0
                             5.4
Bank Sta=0,5.4
XS Rating Curve= 0
Exp/Cntr=.3,.1

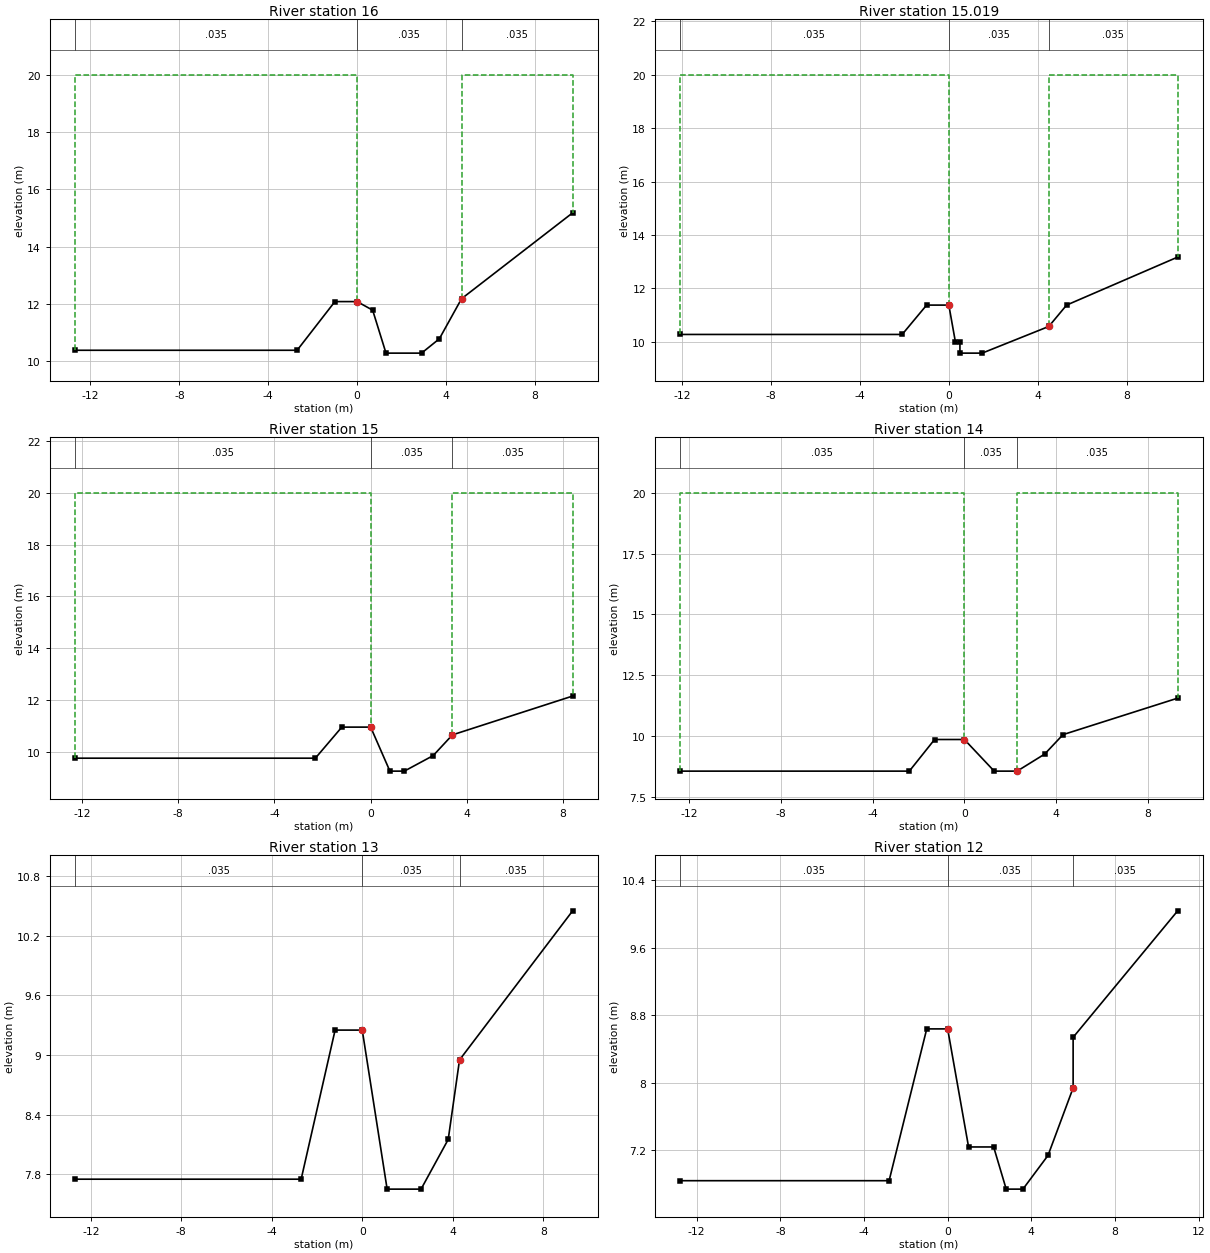
Type RM Length L Ch R = 1 ,16      ,31,31,31
#Sta/Elev= 10
   -12.7   10.38    -2.7   10.38      -1   12.08       0   12.08      .7   11.78
     1.3   10.28     2.9   10.28     3.7   10.78     4.7   12.18     9.7   15.18
#Mann= 3 , 0 , 0
   -12.7    .035       0       0    .035       0     4.7    .035       0
#XS Ineff= 2 , 0
               0      20     4.7              20
Permanent Ineff=
       F       F
#Block Obstruct= 2 , 0
                             4.7
Bank Sta=0,4.7
XS Rating Curve= 0
Exp/Cntr=.3,.1

Type RM Length L Ch R = 1 ,15.019  ,19,19,19
#Sta/Elev= 11
   -12.1   10.27    -2.1   10.27      -1   11.37       0   11.37      .3    9.97
      .5    9.97      .5    9.57     1.5    9.57     4.5   10.57     5.3   11.37
    10.3   13.17
#Mann= 3 , 0 , 0
   -12.1    .035       0       0    .035       0     4.5    .035       0
#XS Ineff= 2 , 0
               0      20     4.5              20
Permanent Ineff=
       F       F
#Block Obstruct= 2 , 0
                             4.5
Bank Sta=0,4.5
XS Rating Curve= 0
Exp/Cntr=.3,.1

Type RM Length L Ch R = 1 ,15      ,50,50,50
#Sta/Elev= 9
   -12.3    9.75    -2.3    9.75    -1.2   10.95       0   10.95      .8    9.25
     1.4    9.25     2.6    9.85     3.4   10.65     8.4   12.15
#Mann= 3 , 0 , 0
   -12.3    .035       0       0    .035       0     3.4    .035       0
#XS Ineff= 2 , 0
               0      20     3.4              20
Permanent Ineff=
       F       F
#Block Obstruct= 2 , 0
                             3.4
Bank Sta=0,3.4
XS Rating Curve= 0
Exp/Cntr=.3,.1

Type RM Length L Ch R = 1 ,14      ,50,50,50
#Sta/Elev= 9
   -12.4    8.56    -2.4    8.56    -1.3    9.86       0    9.86     1.3    8.56
     2.3    8.56     3.5    9.26     4.3   10.06     9.3   11.56
#Mann= 3 , 0 , 0
   -12.4    .035       0       0    .035       0     2.3    .035       0
#XS Ineff= 2 , 0
               0      20     2.3              20
Permanent Ineff=
       F       F
#Block Obstruct= 2 , 0
                             3.4
Bank Sta=0,2.3
XS Rating Curve= 0
Exp/Cntr=.3,.1

Type RM Length L Ch R = 1 ,13      ,50,50,50
#Sta/Elev= 9
   -12.7    7.75    -2.7    7.75    -1.2    9.25       0    9.25     1.1    7.65
     2.6    7.65     3.8    8.15     4.3    8.95     9.3   10.45
#Mann= 3 , 0 , 0
   -12.7    .035       0       0    .035       0     4.3    .035       0
#XS Ineff= 2 , 0
               0      20     4.3              20
Permanent Ineff=
       F       F
#Block Obstruct= 2 , 0
                             4.3
Bank Sta=0,4.3
XS Rating Curve= 0
Exp/Cntr=.3,.1

Type RM Length L Ch R = 1 ,12      ,50,50,50
#Sta/Elev= 12
   -12.8    6.84    -2.8    6.84      -1    8.64       0    8.64       1    7.24
     2.2    7.24     2.8    6.74     3.6    6.74     4.8    7.14       6    7.94
       6    8.54      11   10.04
#Mann= 3 , 0 , 0
   -12.8    .035       0       0    .035       0       6    .035       0
#XS Ineff= 2 , 0
               0      20       6              20
Permanent Ineff=
       F       F
#Block Obstruct= 2 , 0
                               6
Bank Sta=0,6
XS Rating Curve= 0
Exp/Cntr=.3,.1

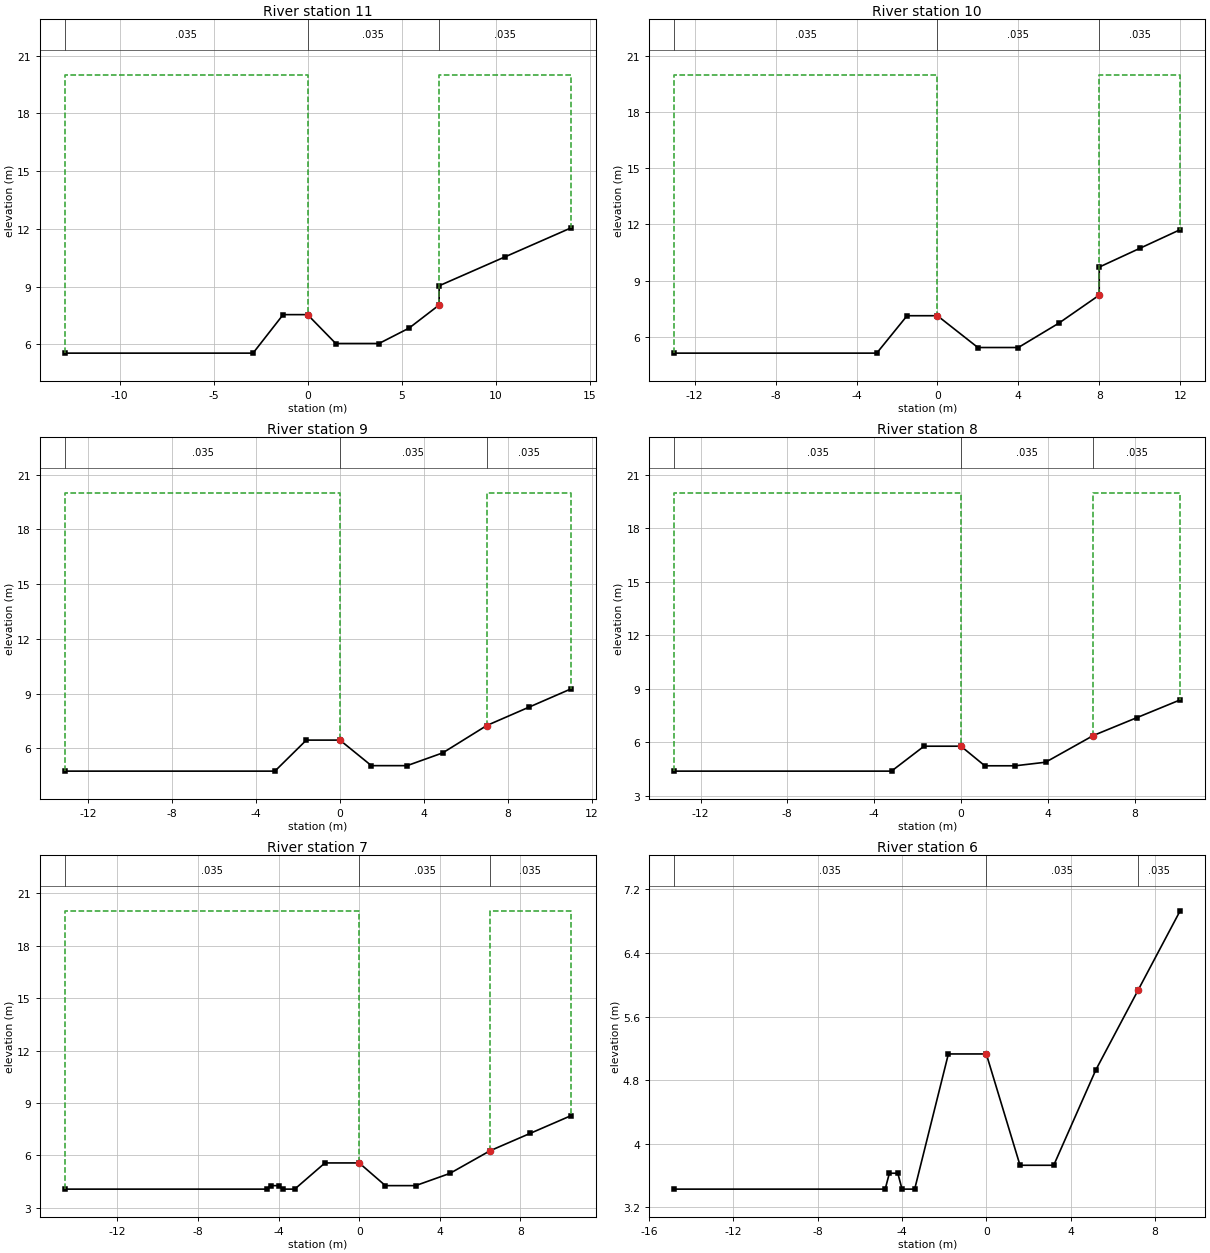
Type RM Length L Ch R = 1 ,11      ,50,50,50
#Sta/Elev= 11
   -12.9    5.54    -2.9    5.54    -1.3    7.54       0    7.54     1.5    6.04
     3.8    6.04     5.4    6.84       7    8.04       7    9.04    10.5   10.54
      14   12.04
#Mann= 3 , 0 , 0
   -12.9    .035       0       0    .035       0       7    .035       0
#XS Ineff= 2 , 0
               0      20       7              20
Permanent Ineff=
       F       F
#Block Obstruct= 2 , 0
                               7
Bank Sta=0,7
XS Rating Curve= 0
Exp/Cntr=.3,.1

Type RM Length L Ch R = 1 ,10      ,50,50,50
#Sta/Elev= 11
     -13    5.12      -3    5.12    -1.5    7.12       0    7.12       2    5.42
       4    5.42       6    6.72       8    8.22       8    9.72      10   10.72
      12   11.72
#Mann= 3 , 0 , 0
     -13    .035       0       0    .035       0       8    .035       0
#XS Ineff= 2 , 0
               0      20       8              20
Permanent Ineff=
       F       F
#Block Obstruct= 2 , 0
                               8
Bank Sta=0,8
XS Rating Curve= 0
Exp/Cntr=.3,.1

Type RM Length L Ch R = 1 ,9       ,50,50,50
#Sta/Elev= 10
   -13.1    4.75    -3.1    4.75    -1.6    6.45       0    6.45     1.5    5.05
     3.2    5.05     4.9    5.75       7    7.25       9    8.25      11    9.25
#Mann= 3 , 0 , 0
   -13.1    .035       0       0    .035       0       7    .035       0
#XS Ineff= 2 , 0
               0      20       7              20
Permanent Ineff=
       F       F
#Block Obstruct= 2 , 0
                               7
Bank Sta=0,7
XS Rating Curve= 0
Exp/Cntr=.3,.1

Type RM Length L Ch R = 1 ,8       ,50,50,50
#Sta/Elev= 10
   -13.2    4.37    -3.2    4.37    -1.7    5.77       0    5.77     1.1    4.67
     2.5    4.67     3.9    4.87     6.1    6.37     8.1    7.37    10.1    8.37
#Mann= 3 , 0 , 0
   -13.2    .035       0       0    .035       0     6.1    .035       0
#XS Ineff= 2 , 0
               0      20     6.1              20
Permanent Ineff=
       F       F
#Block Obstruct= 2 , 0
                             6.1
Bank Sta=0,6.1
XS Rating Curve= 0
Exp/Cntr=.3,.1

Type RM Length L Ch R = 1 ,7       ,50,50,50
#Sta/Elev= 14
   -14.6    4.06    -4.6    4.06    -4.4    4.26      -4    4.26    -3.8    4.06
    -3.2    4.06    -1.7    5.56       0    5.56     1.3    4.26     2.8    4.26
     4.5    4.96     6.5    6.26     8.5    7.26    10.5    8.26
#Mann= 3 , 0 , 0
   -14.6    .035       0       0    .035       0     6.5    .035       0
#XS Ineff= 2 , 0
               0      20     6.5              20
Permanent Ineff=
       F       F
#Block Obstruct= 2 , 0
                             6.5
Bank Sta=0,6.5
XS Rating Curve= 0
Exp/Cntr=.3,.1

Type RM Length L Ch R = 1 ,6       ,50,50,50
#Sta/Elev= 13
   -14.8    3.43    -4.8    3.43    -4.6    3.63    -4.2    3.63      -4    3.43
    -3.4    3.43    -1.8    5.13       0    5.13     1.6    3.73     3.2    3.73
     5.2    4.93     7.2    5.93     9.2    6.93
#Mann= 3 , 0 , 0
   -14.8    .035       0       0    .035       0     7.2    .035       0
#XS Ineff= 2 , 0
               0      20     7.2              20
Permanent Ineff=
       F       F
#Block Obstruct= 2 , 0
                             7.2
Bank Sta=0,7.2
XS Rating Curve= 0
Exp/Cntr=.3,.1

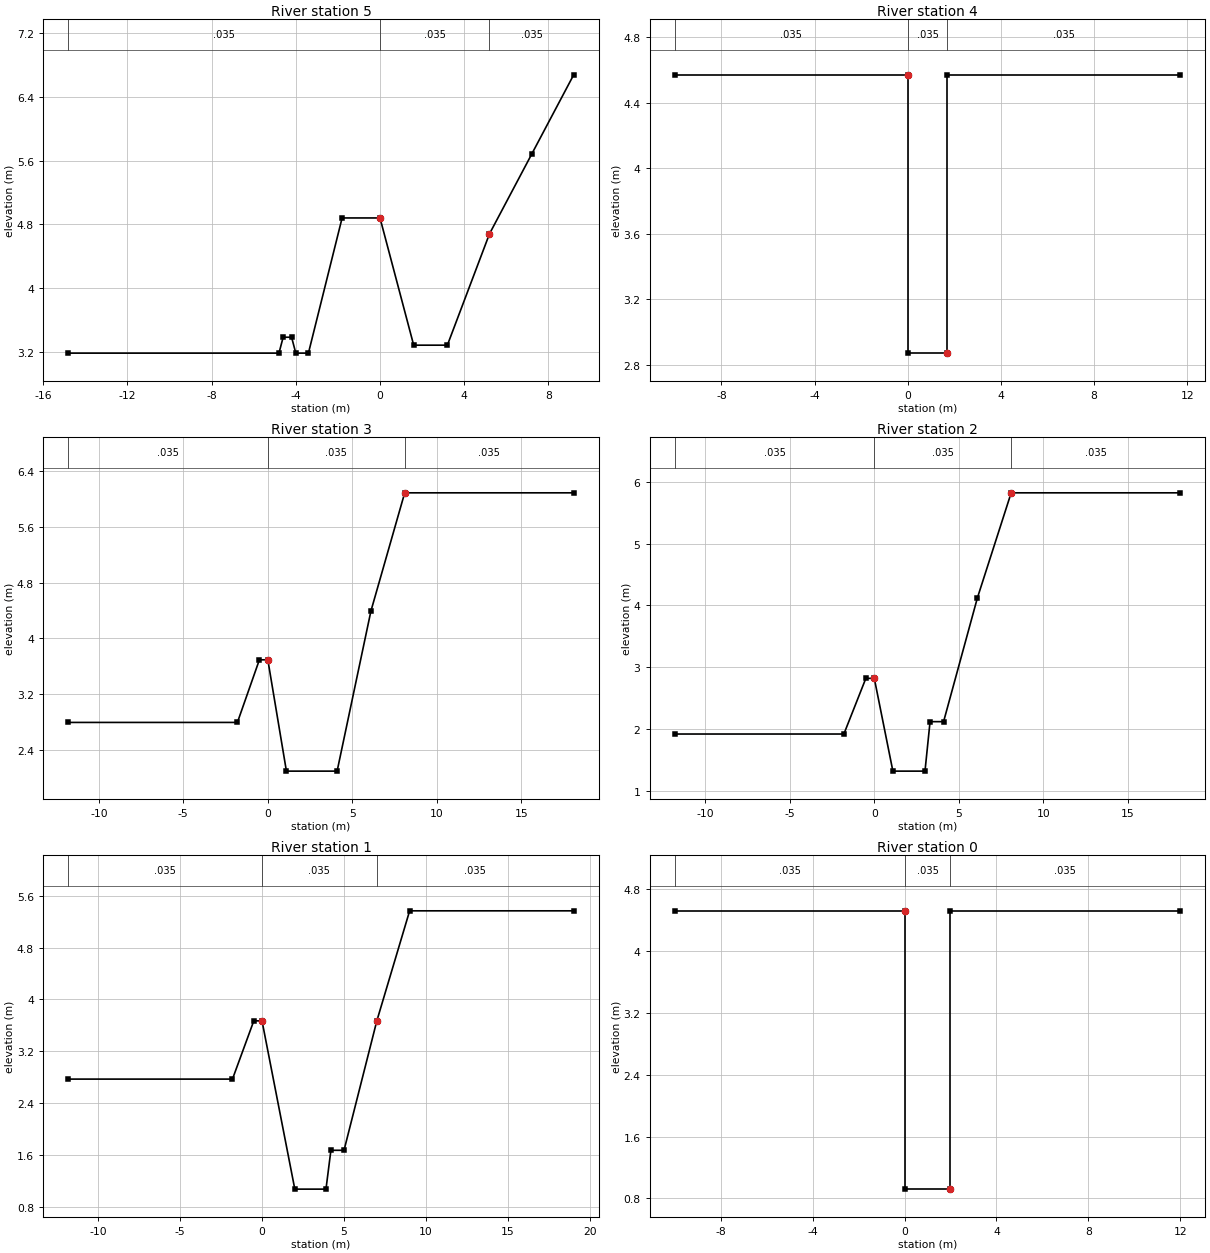
Type RM Length L Ch R = 1 ,5       ,50,50,50
#Sta/Elev= 13
   -14.8    3.18    -4.8    3.18    -4.6    3.38    -4.2    3.38      -4    3.18
    -3.4    3.18    -1.8    4.88       0    4.88     1.6    3.28     3.2    3.28
     5.2    4.68     7.2    5.68     9.2    6.68
#Mann= 3 , 0 , 0
   -14.8    .035       0       0    .035       0     5.2    .035       0
#XS Ineff= 2 , 0
               0      20     5.2              20
Permanent Ineff=
       F       F
#Block Obstruct= 2 , 0
                             5.2
Bank Sta=0,5.2
XS Rating Curve= 0
Exp/Cntr=.3,.1

Type RM Length L Ch R = 1 ,4       ,50,50,50
#Sta/Elev= 6
     -10    4.57       0    4.57       0    2.87     1.7    2.87     1.7    4.57
    11.7    4.57
#Mann= 3 , 0 , 0
     -10    .035       0       0    .035       0     1.7    .035       0
#XS Ineff= 2 , 0
               0      20     1.7              20
Permanent Ineff=
       F       F
#Block Obstruct= 2 , 0
                             1.7
Bank Sta=0,1.7
XS Rating Curve= 0
Exp/Cntr=.3,.1

Type RM Length L Ch R = 1 ,3       ,50,50,50
#Sta/Elev= 9
   -11.8    2.79    -1.8    2.79     -.5    3.69       0    3.69     1.1    2.09
     4.1    2.09     6.1    4.39     8.1    6.09    18.1    6.09
#Mann= 3 , 0 , 0
   -11.8    .035       0       0    .035       0     8.1    .035       0
#XS Ineff= 2 , 0
               0      20     8.1              20
Permanent Ineff=
       F       F
#Block Obstruct= 2 , 0
                             8.1
Bank Sta=0,8.1
XS Rating Curve= 0
Exp/Cntr=.3,.1

Type RM Length L Ch R = 1 ,2       ,50,50,50
#Sta/Elev= 11
   -11.8    1.92    -1.8    1.92     -.5    2.82       0    2.82     1.1    1.32
       3    1.32     3.3    2.12     4.1    2.12     6.1    4.12     8.1    5.82
    18.1    5.82
#Mann= 3 , 0 , 0
   -11.8    .035       0       0    .035       0     8.1    .035       0
#XS Ineff= 2 , 0
               0      20     8.1              20
Permanent Ineff=
       F       F
#Block Obstruct= 2 , 0
                             8.1
Bank Sta=0,8.1
XS Rating Curve= 0
Exp/Cntr=.3,.1

Type RM Length L Ch R = 1 ,1       ,50,50,50
#Sta/Elev= 11
   -11.8    2.77    -1.8    2.77     -.5    3.67       0    3.67       2    1.07
     3.9    1.07     4.2    1.67       5    1.67       7    3.67       9    5.37
      19    5.37
#Mann= 3 , 0 , 0
   -11.8    .035       0       0    .035       0       7    .035       0
#XS Ineff= 2 , 0
               0      20       7              20
Permanent Ineff=
       F       F
#Block Obstruct= 2 , 0
                               7
Bank Sta=0,7
XS Rating Curve= 0
Exp/Cntr=.3,.1

Type RM Length L Ch R = 1 ,0       ,0,0,0
#Sta/Elev= 6
     -10    4.52       0    4.52       0     .92       2     .92       2    4.52
      12    4.52
#Mann= 3 , 0 , 0
     -10    .035       0       0    .035       0       2    .035       0
#XS Ineff= 2 , 0
               0      20       2              20
Permanent Ineff=
       F       F
#Block Obstruct= 2 , 0
                               2
Bank Sta=0,2
XS Rating Curve= 0
Exp/Cntr=.3,.1

Chan Stop Cuts=-1