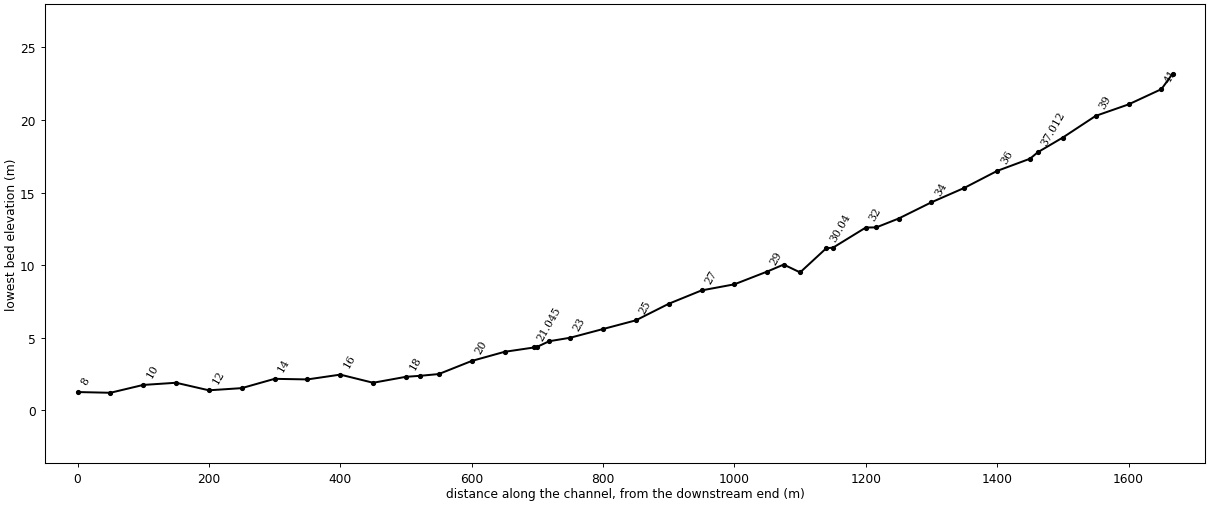
--- HDC.prj (project) ---

Proj Title=HODONG
Current Plan=p01
Default Exp/Contr=.3,.1
SI Units
Geom File=g01
Flow File=f01
Plan File=p01
Y Axis Title=Elevation
X Axis Title(PF)=Main Channel Distance
X Axis Title(XS)=Station
BEGIN DESCRIPTION:
           BACK WATER COMPUTATION
      APPLICATION OF HEC-2 BY Samju Construction Engineering
      hodong-ch: 10,20,30,50,80 yr
END DESCRIPTION:
DSS Export Rating Curves= 0
DSS Export Rating Curve Sorted= 0
DSS Export Volume Flow Curves= 0
DXF OffsetX= 0
DXF OffsetY= 0
DXF ScaleX= 1
DXF ScaleY= 10

--- HDC.p01 (plan) ---

Plan Title=Imported Plan 01
Version=Version 3.0.1  Mar 2001
Short Identifier=Imported Pla
Geom File=g01
Flow File=f01
Subcritical Flow
K Sum by GR= 0
Std Step Tol= 0.003
Critical Tol= 0.003
Num of Std Step Trials= 20
Max Error Tol= 0.1
Flow Tol Ratio= 0.001
Split Flow NTrial= 30
Split Flow Tol= 0.02
Split Flow Ratio= 0.02
Log Output Level= 0
Friction Slope Method= 1
Unsteady Friction Slope Method= 2
Parabolic Critical Depth
Global Vel Dist= 0 , 0 , 0
Global Log Level= 0
CheckData=True
Encroach Param=-1 ,0,0, 0
Computation Interval=1HOUR
Output Interval=1HOUR
Run HTab= 0
Run UNet= 0
Run PostProcess= 0
UNET Theta= 1
UNET ZTol= 0.02
UNET ZSATol= 0.1
UNET MxIter= 20
UNET MaxInSteps= 20
UNET DtIC= 0
UNET DtMin= 0
UNET MaxCRTS= 20
UNET WFStab= 2
UNET SFStab= 1
UNET WFX= 1
UNET SFX= 1
UNET Convert EG Bridges=-1
UNET Use Existing IB Tables=-1
Instantaneous Interval=1HOUR
Write IC File= 0
Write Velocity= 0
Write Detailed= 0

--- HDC.f01 (steady flow) ---

Flow Title=Imported Flow 01
Version=Version 3.0.1  Mar 2001
Number of Profiles= 5
Profile Names=10YR,20YR,30YR,50YR,80YR
River Rch & RM=RIVER-1,Reach-1         ,41.017
   13.46   14.83   15.63   16.64   17.57
River Rch & RM=RIVER-1,Reach-1         ,18
   18.53   20.42   21.53   22.92   24.21
River Rch & RM=HODONG,HODONG          ,41.017
   13.46   14.83   15.63   16.64   17.57
River Rch & RM=HODONG,HODONG          ,18
   18.53   20.42   21.53   22.92   24.21
Boundary for River Rch & Prof#=HODONG,HODONG          , 1
Up Type= 0
Dn Type= 3
Dn Slope=.025
Boundary for River Rch & Prof#=HODONG,HODONG          , 2
Up Type= 0
Dn Type= 3
Dn Slope=.025
Boundary for River Rch & Prof#=HODONG,HODONG          , 3
Up Type= 0
Dn Type= 3
Dn Slope=.025
Boundary for River Rch & Prof#=HODONG,HODONG          , 4
Up Type= 0
Dn Type= 3
Dn Slope=.025
Boundary for River Rch & Prof#=HODONG,HODONG          , 5
Up Type= 0
Dn Type= 3
Dn Slope=.025
DSS Import GetInterval= 0
DSS Import GetPeak= 0
DSS Import FillOption= 0

--- HDC.g01 (geometry) ---

Geom Title=Imported Geom 01
Version=Version 3.0.1  Mar 2001

River Reach=HODONG          ,HODONG
Reach XY= 2
              .5             .95              .5             .05

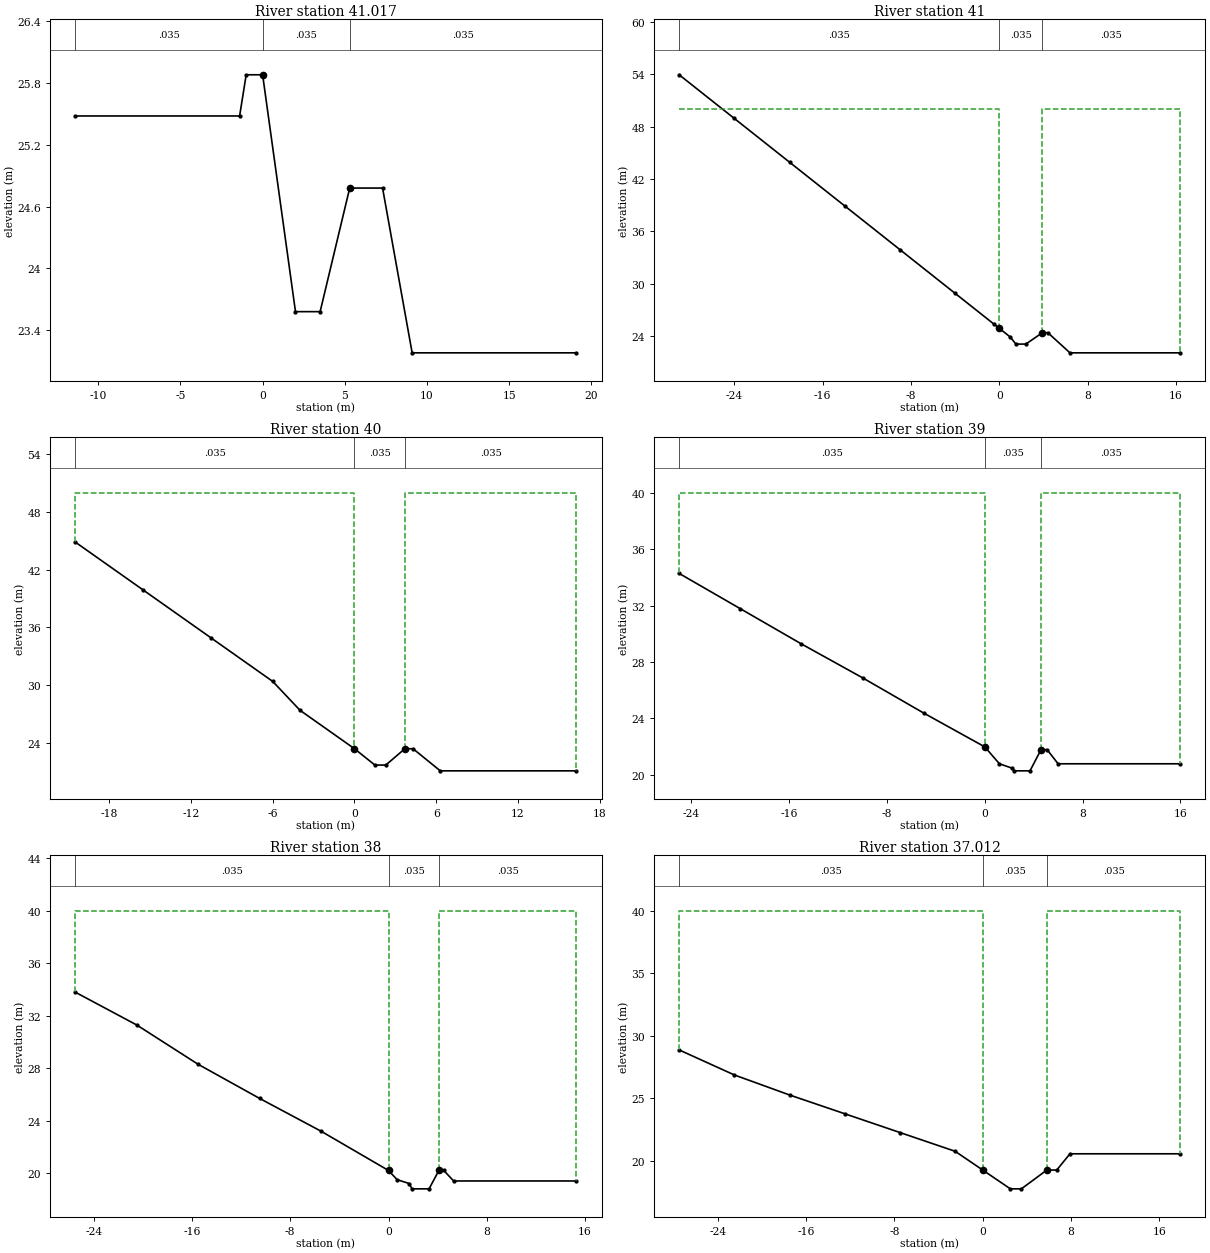
Type RM Length L Ch R = 1 ,41.017  ,17,17,17
#Sta/Elev= 10
   -11.4   25.48    -1.4   25.48      -1   25.88       0   25.88       2   23.58
     3.5   23.58     5.3   24.78     7.3   24.78     9.1   23.18    19.1   23.18
#Mann= 3 , 0 , 0
   -11.4    .035       0       0    .035       0     5.3    .035       0
#XS Ineff= 2 , 0
               0      50     5.3              50
Permanent Ineff=
       F       F
#Block Obstruct= 2 , 0
                             5.3
Bank Sta=0,5.3
XS Rating Curve= 0
Exp/Cntr=.3,.1

Type RM Length L Ch R = 1 ,41      ,50,50,50
#Sta/Elev= 15
     -29   53.92     -24   48.92     -19   43.92     -14   38.92      -9   33.92
      -4   28.92     -.5   25.42       0   24.92       1   23.92     1.5   23.12
     2.4   23.12     3.9   24.42     4.4   24.42     6.4   22.12    16.4   22.12
#Mann= 3 , 0 , 0
     -29    .035       0       0    .035       0     3.9    .035       0
#XS Ineff= 2 , 0
               0      50     3.9              50
Permanent Ineff=
       F       F
#Block Obstruct= 2 , 0
                             3.9
Bank Sta=0,3.9
XS Rating Curve= 0
Exp/Cntr=.3,.1

Type RM Length L Ch R = 1 ,40      ,50,50,50
#Sta/Elev= 12
   -20.5   44.87   -15.5   39.87   -10.5   34.87      -6   30.37      -4   27.37
       0   23.37     1.5   21.67     2.3   21.67     3.7   23.37     4.3   23.37
     6.3   21.07    16.3   21.07
#Mann= 3 , 0 , 0
   -20.5    .035       0       0    .035       0     3.7    .035       0
#XS Ineff= 2 , 0
               0      50     3.7              50
Permanent Ineff=
       F       F
#Block Obstruct= 2 , 0
                             3.7
Bank Sta=0,3.7
XS Rating Curve= 0
Exp/Cntr=.3,.1

Type RM Length L Ch R = 1 ,39      ,50,50,50
#Sta/Elev= 14
     -25   34.28     -20   31.78     -15   29.28     -10   26.88      -5   24.38
       0   21.98     1.2   20.78     2.2   20.48     2.4   20.28     3.7   20.28
     4.6   21.78     5.1   21.78       6   20.78      16   20.78
#Mann= 3 , 0 , 0
     -25    .035       0       0    .035       0     4.6    .035       0
#XS Ineff= 2 , 0
               0      40     4.6              40
Permanent Ineff=
       F       F
#Block Obstruct= 2 , 0
                             4.6
Bank Sta=0,4.6
XS Rating Curve= 0
Exp/Cntr=.3,.1

Type RM Length L Ch R = 1 ,38      ,38,38,38
#Sta/Elev= 14
   -25.5   33.79   -20.5   31.29   -15.5   28.29   -10.5   25.69    -5.5   23.19
       0   20.19      .7   19.49     1.7   19.19     1.9   18.79     3.3   18.79
     4.1   20.19     4.5   20.19     5.3   19.39    15.3   19.39
#Mann= 3 , 0 , 0
   -25.5    .035       0       0    .035       0     4.1    .035       0
#XS Ineff= 2 , 0
               0      40     4.1              40
Permanent Ineff=
       F       F
#Block Obstruct= 2 , 0
                             4.1
Bank Sta=0,4.1
XS Rating Curve= 0
Exp/Cntr=.3,.1

Type RM Length L Ch R = 1 ,37.012  ,12,12,12
#Sta/Elev= 13
   -27.5   28.88   -22.5   26.88   -17.5   25.28   -12.5   23.78    -7.5   22.28
    -2.5   20.78       0   19.28     2.5   17.78     3.5   17.78     5.8   19.28
     6.7   19.28     7.9   20.58    17.9   20.58
#Mann= 3 , 0 , 0
   -27.5    .035       0       0    .035       0     5.8    .035       0
#XS Ineff= 2 , 0
               0      40     5.8              40
Permanent Ineff=
       F       F
#Block Obstruct= 2 , 0
                             5.8
Bank Sta=0,5.8
XS Rating Curve= 0
Exp/Cntr=.3,.1

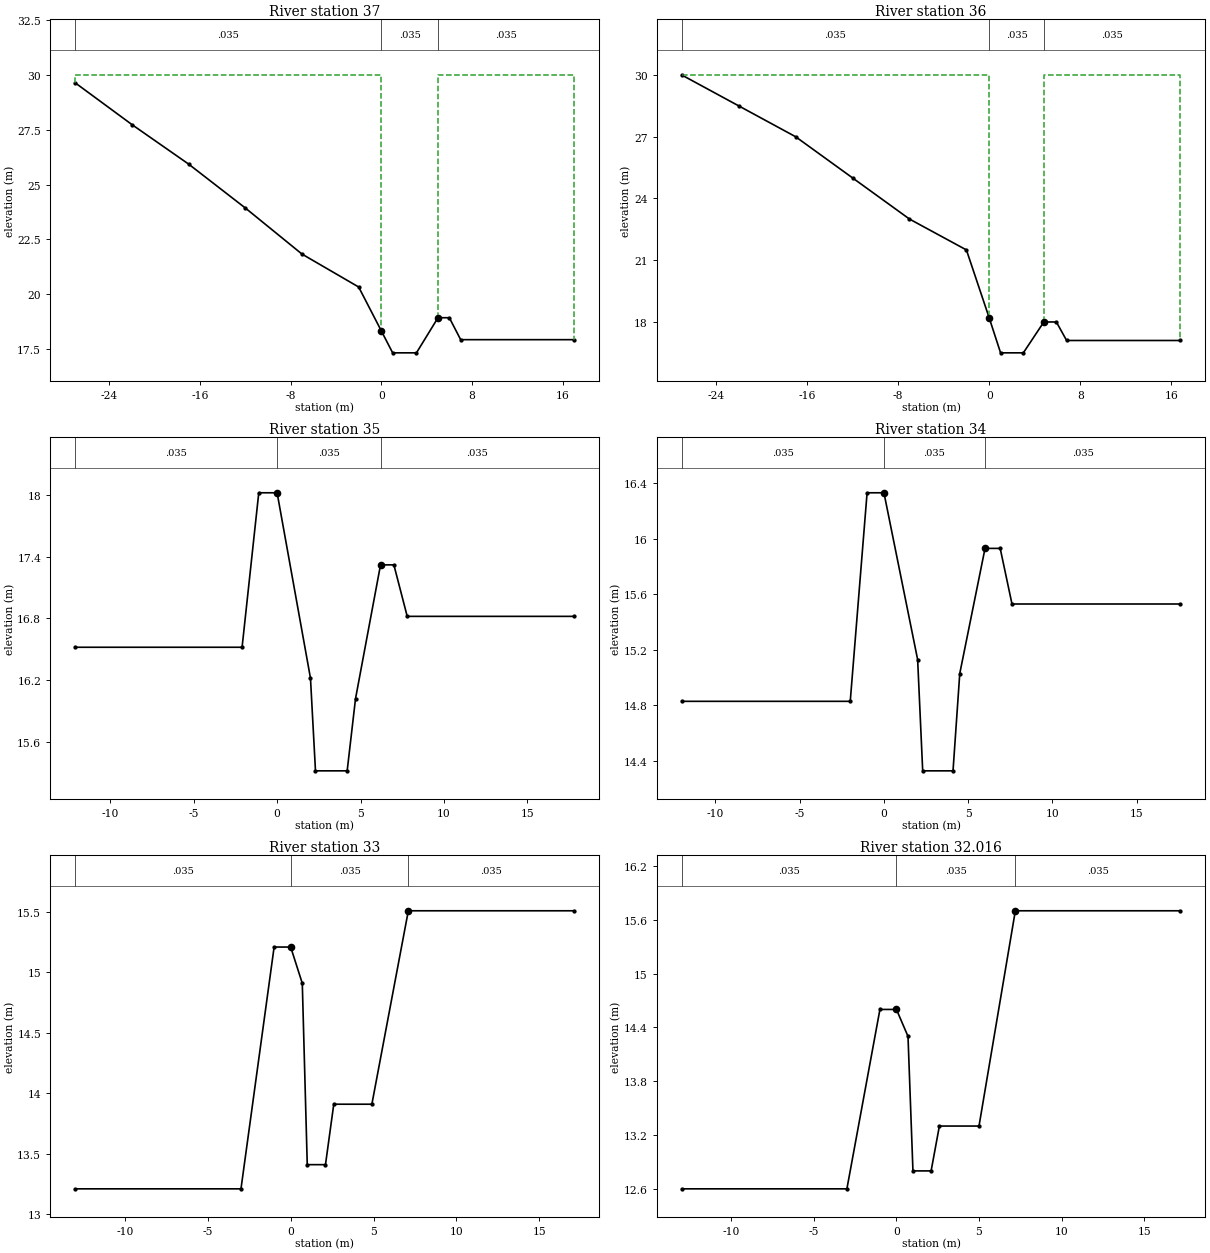
Type RM Length L Ch R = 1 ,37      ,50,50,50
#Sta/Elev= 13
     -27   29.63     -22   27.73     -17   25.93     -12   23.93      -7   21.83
      -2   20.33       0   18.33       1   17.33     3.1   17.33       5   18.93
       6   18.93       7   17.93      17   17.93
#Mann= 3 , 0 , 0
     -27    .035       0       0    .035       0       5    .035       0
#XS Ineff= 2 , 0
               0      30       5              30
Permanent Ineff=
       F       F
#Block Obstruct= 2 , 0
                               5
Bank Sta=0,5
XS Rating Curve= 0
Exp/Cntr=.3,.1

Type RM Length L Ch R = 1 ,36      ,50,50,50
#Sta/Elev= 13
     -27   29.99     -22   28.49     -17   26.99     -12   24.99      -7   22.99
      -2   21.49       0   18.19       1   16.49       3   16.49     4.8   17.99
     5.9   17.99     6.8   17.09    16.8   17.09
#Mann= 3 , 0 , 0
     -27    .035       0       0    .035       0     4.8    .035       0
#XS Ineff= 2 , 0
               0      30     4.8              30
Permanent Ineff=
       F       F
#Block Obstruct= 2 , 0
                             4.8
Bank Sta=0,4.8
XS Rating Curve= 0
Exp/Cntr=.3,.1

Type RM Length L Ch R = 1 ,35      ,50,50,50
#Sta/Elev= 12
   -12.1   16.52    -2.1   16.52    -1.1   18.02       0   18.02       2   16.22
     2.3   15.32     4.2   15.32     4.7   16.02     6.2   17.32       7   17.32
     7.8   16.82    17.8   16.82
#Mann= 3 , 0 , 0
   -12.1    .035       0       0    .035       0     6.2    .035       0
#XS Ineff= 2 , 0
               0      30     6.2              30
Permanent Ineff=
       F       F
#Block Obstruct= 2 , 0
                             6.2
Bank Sta=0,6.2
XS Rating Curve= 0
Exp/Cntr=.3,.1

Type RM Length L Ch R = 1 ,34      ,50,50,50
#Sta/Elev= 12
     -12   14.83      -2   14.83      -1   16.33       0   16.33       2   15.13
     2.3   14.33     4.1   14.33     4.5   15.03       6   15.93     6.9   15.93
     7.6   15.53    17.6   15.53
#Mann= 3 , 0 , 0
     -12    .035       0       0    .035       0       6    .035       0
#XS Ineff= 2 , 0
               0      30       6              30
Permanent Ineff=
       F       F
#Block Obstruct= 2 , 0
                               6
Bank Sta=0,6
XS Rating Curve= 0
Exp/Cntr=.3,.1

Type RM Length L Ch R = 1 ,33      ,34,34,34
#Sta/Elev= 11
     -13   13.21      -3   13.21      -1   15.21       0   15.21      .7   14.91
       1   13.41     2.1   13.41     2.6   13.91     4.9   13.91     7.1   15.51
    17.1   15.51
#Mann= 3 , 0 , 0
     -13    .035       0       0    .035       0     7.1    .035       0
#XS Ineff= 2 , 0
               0      30     7.1              30
Permanent Ineff=
       F       F
#Block Obstruct= 2 , 0
                             7.1
Bank Sta=0,7.1
XS Rating Curve= 0
Exp/Cntr=.3,.1

Type RM Length L Ch R = 1 ,32.016  ,16,16,16
#Sta/Elev= 11
     -13    12.6      -3    12.6      -1    14.6       0    14.6      .7    14.3
       1    12.8     2.1    12.8     2.6    13.3       5    13.3     7.2    15.7
    17.2    15.7
#Mann= 3 , 0 , 0
     -13    .035       0       0    .035       0     7.2    .035       0
#XS Ineff= 2 , 0
               0      30     7.2              30
Permanent Ineff=
       F       F
#Block Obstruct= 2 , 0
                             7.2
Bank Sta=0,7.2
XS Rating Curve= 0
Exp/Cntr=.3,.1

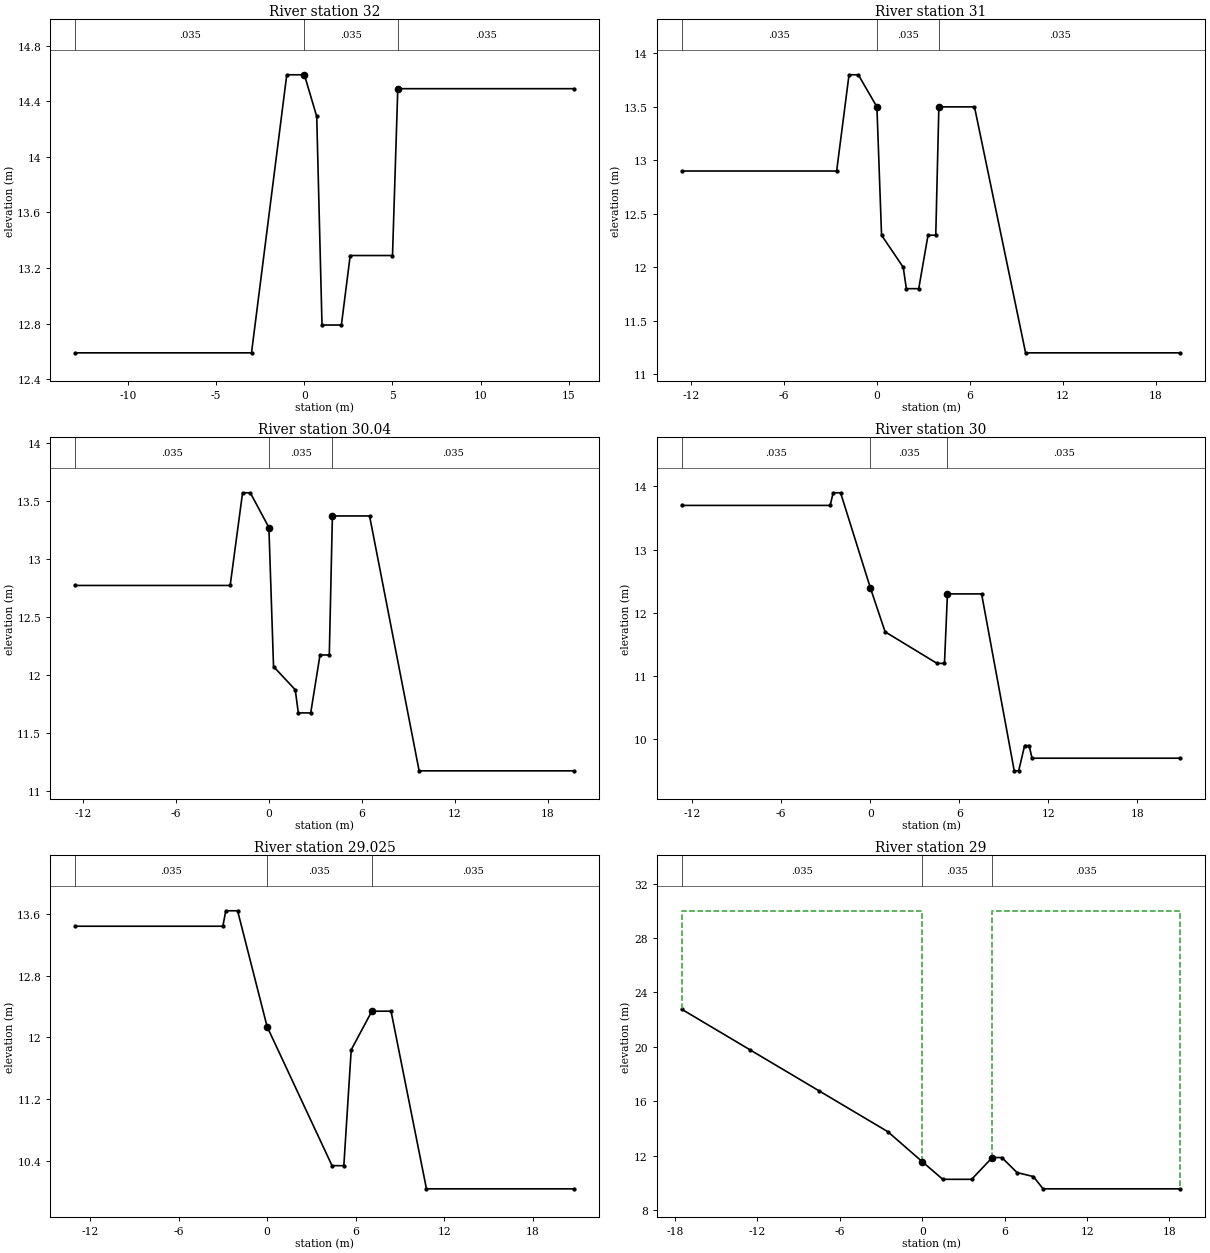
Type RM Length L Ch R = 1 ,32      ,50,50,50
#Sta/Elev= 11
     -13   12.59      -3   12.59      -1   14.59       0   14.59      .7   14.29
       1   12.79     2.1   12.79     2.6   13.29       5   13.29     5.3   14.49
    15.3   14.49
#Mann= 3 , 0 , 0
     -13    .035       0       0    .035       0     5.3    .035       0
#XS Ineff= 2 , 0
               0      30     5.3              30
Permanent Ineff=
       F       F
#Block Obstruct= 2 , 0
                             5.3
Bank Sta=0,5.3
XS Rating Curve= 0
Exp/Cntr=.3,.1

Type RM Length L Ch R = 1 ,31      ,10,10,10
#Sta/Elev= 15
   -12.6    12.9    -2.6    12.9    -1.8    13.8    -1.2    13.8       0    13.5
      .3    12.3     1.7      12     1.9    11.8     2.7    11.8     3.3    12.3
     3.8    12.3       4    13.5     6.3    13.5     9.6    11.2    19.6    11.2
#Mann= 3 , 0 , 0
   -12.6    .035       0       0    .035       0       4    .035       0
#XS Ineff= 2 , 0
               0      30       4              30
Permanent Ineff=
       F       F
#Block Obstruct= 2 , 0
                               4
Bank Sta=0,4
XS Rating Curve= 0
Exp/Cntr=.3,.1

Type RM Length L Ch R = 1 ,30.04   ,40,40,40
#Sta/Elev= 15
   -12.5   12.77    -2.5   12.77    -1.7   13.57    -1.2   13.57       0   13.27
      .3   12.07     1.7   11.87     1.9   11.67     2.7   11.67     3.3   12.17
     3.9   12.17     4.1   13.37     6.5   13.37     9.7   11.17    19.7   11.17
#Mann= 3 , 0 , 0
   -12.5    .035       0       0    .035       0     4.1    .035       0
#XS Ineff= 2 , 0
               0      30     4.1              30
Permanent Ineff=
       F       F
#Block Obstruct= 2 , 0
                             4.1
Bank Sta=0,4.1
XS Rating Curve= 0
Exp/Cntr=.3,.1

Type RM Length L Ch R = 1 ,30      ,25,25,25
#Sta/Elev= 16
   -12.7    13.7    -2.7    13.7    -2.5    13.9      -2    13.9       0    12.4
       1    11.7     4.5    11.2       5    11.2     5.2    12.3     7.5    12.3
     9.7     9.5      10     9.5    10.4     9.9    10.7     9.9    10.9     9.7
    20.9     9.7
#Mann= 3 , 0 , 0
   -12.7    .035       0       0    .035       0     5.2    .035       0
#XS Ineff= 2 , 0
               0      30     5.2              30
Permanent Ineff=
       F       F
#Block Obstruct= 2 , 0
                             5.2
Bank Sta=0,5.2
XS Rating Curve= 0
Exp/Cntr=.3,.1

Type RM Length L Ch R = 1 ,29.025  ,25,25,25
#Sta/Elev= 12
     -13   13.44      -3   13.44    -2.8   13.64      -2   13.64       0   12.14
     4.4   10.34     5.2   10.34     5.7   11.84     7.1   12.34     8.4   12.34
    10.8   10.04    20.8   10.04
#Mann= 3 , 0 , 0
     -13    .035       0       0    .035       0     7.1    .035       0
#XS Ineff= 2 , 0
               0      30     7.1              30
Permanent Ineff=
       F       F
#Block Obstruct= 2 , 0
                             7.1
Bank Sta=0,7.1
XS Rating Curve= 0
Exp/Cntr=.3,.1

Type RM Length L Ch R = 1 ,29      ,50,50,50
#Sta/Elev= 13
   -17.5   22.76   -12.5   19.76    -7.5   16.76    -2.5   13.76       0   11.56
     1.5   10.26     3.6   10.26     5.1   11.86     5.8   11.86     6.9   10.76
     8.1   10.46     8.8    9.56    18.8    9.56
#Mann= 3 , 0 , 0
   -17.5    .035       0       0    .035       0     5.1    .035       0
#XS Ineff= 2 , 0
               0      30     5.1              30
Permanent Ineff=
       F       F
#Block Obstruct= 2 , 0
                             5.1
Bank Sta=0,5.1
XS Rating Curve= 0
Exp/Cntr=.3,.1

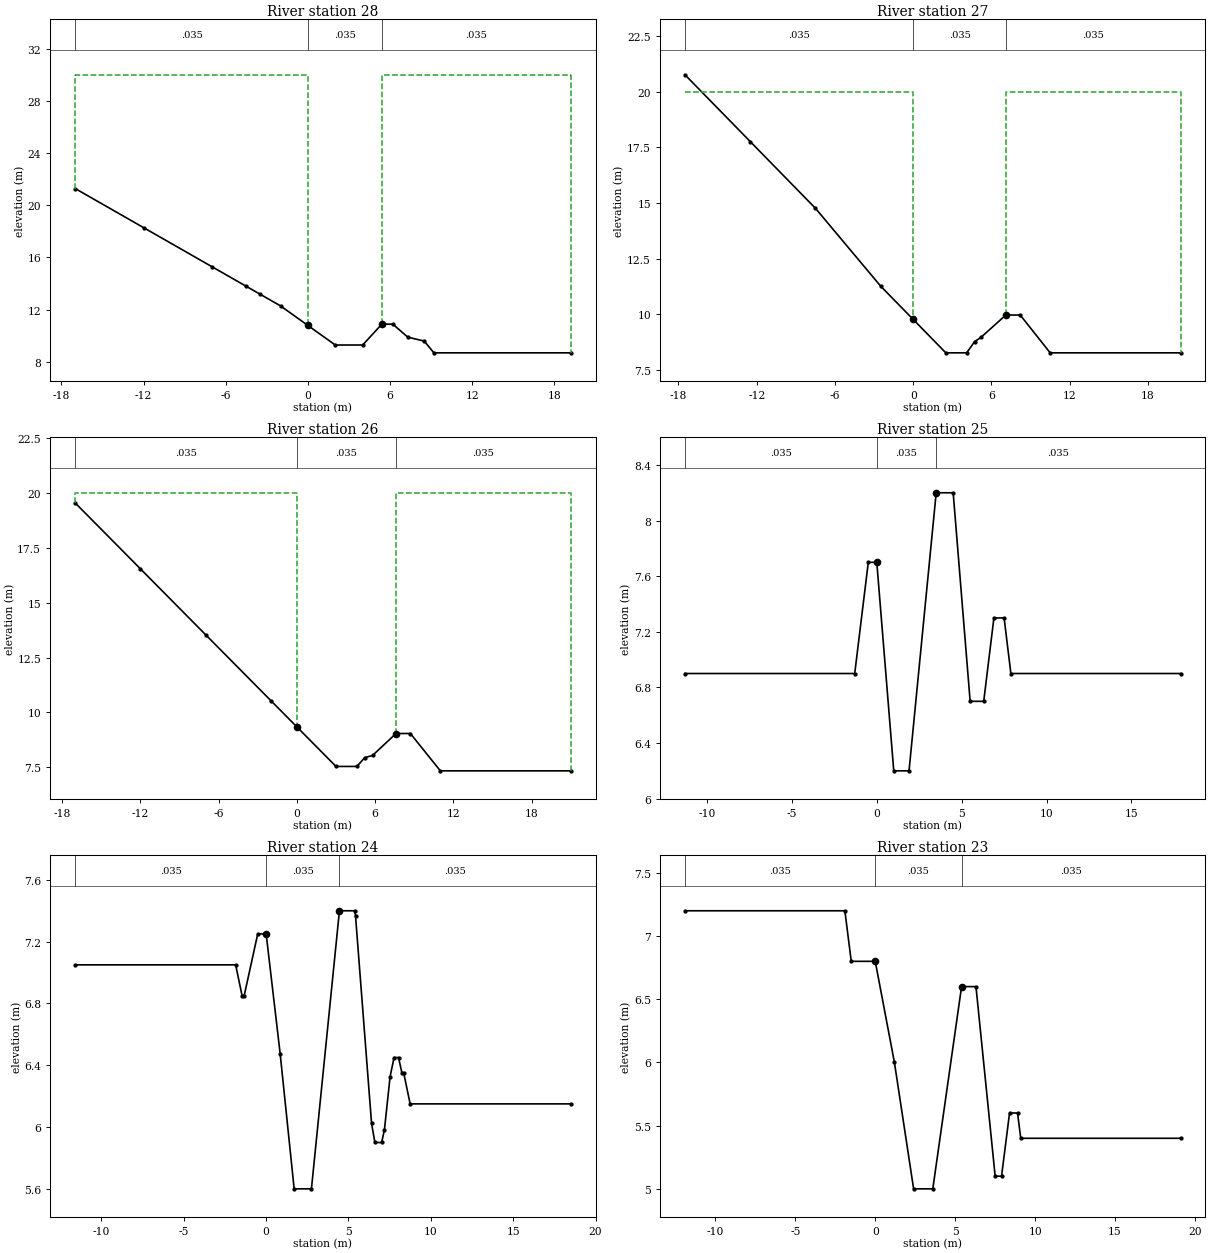
Type RM Length L Ch R = 1 ,28      ,50,50,50
#Sta/Elev= 15
     -17   21.28     -12   18.28      -7   15.28    -4.5   13.78    -3.5   13.18
      -2   12.28       0   10.78       2    9.28       4    9.28     5.4   10.88
     6.2   10.88     7.3    9.88     8.5    9.58     9.2    8.68    19.2    8.68
#Mann= 3 , 0 , 0
     -17    .035       0       0    .035       0     5.4    .035       0
#XS Ineff= 2 , 0
               0      30     5.4              30
Permanent Ineff=
       F       F
#Block Obstruct= 2 , 0
                             5.4
Bank Sta=0,5.4
XS Rating Curve= 0
Exp/Cntr=.3,.1

Type RM Length L Ch R = 1 ,27      ,50,50,50
#Sta/Elev= 13
   -17.5   20.76   -12.5   17.76    -7.5   14.76    -2.5   11.26       0    9.76
     2.5    8.26     4.1    8.26     4.7    8.76     5.2    8.96     7.1    9.96
     8.2    9.96    10.5    8.26    20.5    8.26
#Mann= 3 , 0 , 0
   -17.5    .035       0       0    .035       0     7.1    .035       0
#XS Ineff= 2 , 0
               0      20     7.1              20
Permanent Ineff=
       F       F
#Block Obstruct= 2 , 0
                             7.1
Bank Sta=0,7.1
XS Rating Curve= 0
Exp/Cntr=.3,.1

Type RM Length L Ch R = 1 ,26      ,50,50,50
#Sta/Elev= 13
     -17   19.54     -12   16.54      -7   13.54      -2   10.54       0    9.34
       3    7.54     4.6    7.54     5.2    7.94     5.8    8.04     7.6    9.04
     8.7    9.04      11    7.34      21    7.34
#Mann= 3 , 0 , 0
     -17    .035       0       0    .035       0     7.6    .035       0
#XS Ineff= 2 , 0
               0      20     7.6              20
Permanent Ineff=
       F       F
#Block Obstruct= 2 , 0
                             7.6
Bank Sta=0,7.6
XS Rating Curve= 0
Exp/Cntr=.3,.1

Type RM Length L Ch R = 1 ,25      ,50,50,50
#Sta/Elev= 14
   -11.3     6.9    -1.3     6.9     -.5     7.7       0     7.7       1     6.2
     1.9     6.2     3.5     8.2     4.5     8.2     5.5     6.7     6.3     6.7
     6.9     7.3     7.5     7.3     7.9     6.9    17.9     6.9
#Mann= 3 , 0 , 0
   -11.3    .035       0       0    .035       0     3.5    .035       0
#XS Ineff= 2 , 0
               0      20     3.5              20
Permanent Ineff=
       F       F
#Block Obstruct= 2 , 0
                             3.5
Bank Sta=0,3.5
XS Rating Curve= 0
Exp/Cntr=.3,.1

Type RM Length L Ch R = 1 ,24      ,50,50,50
#Sta/Elev= 23
   -11.6    7.05  -1.852    7.05  -1.462    6.85  -1.335    6.85   -.513    7.25
       0    7.25     .85   6.475     1.7     5.6    2.75     5.6    4.45     7.4
   5.373     7.4   5.426   7.368   6.401   6.023   6.604     5.9   7.014     5.9
   7.182   5.982   7.527   6.327   7.767    6.45   8.039    6.45   8.245    6.35
   8.353    6.35   8.743    6.15    18.5    6.15
#Mann= 3 , 0 , 0
   -11.6    .035       0       0    .035       0    4.45    .035       0
#XS Ineff= 2 , 0
               0      20    4.45              20
Permanent Ineff=
       F       F
#Block Obstruct= 2 , 0
                            4.45
Bank Sta=0,4.45
XS Rating Curve= 0
Exp/Cntr=.3,.1

Type RM Length L Ch R = 1 ,23      ,32,32,32
#Sta/Elev= 15
   -11.9     7.2    -1.9     7.2    -1.5     6.8       0     6.8     1.2       6
     2.4       5     3.6       5     5.4     6.6     6.3     6.6     7.5     5.1
     7.9     5.1     8.4     5.6     8.9     5.6     9.1     5.4    19.1     5.4
#Mann= 3 , 0 , 0
   -11.9    .035       0       0    .035       0     5.4    .035       0
#XS Ineff= 2 , 0
               0      20     5.4              20
Permanent Ineff=
       F       F
#Block Obstruct= 2 , 0
                             5.4
Bank Sta=0,5.4
XS Rating Curve= 0
Exp/Cntr=.3,.1

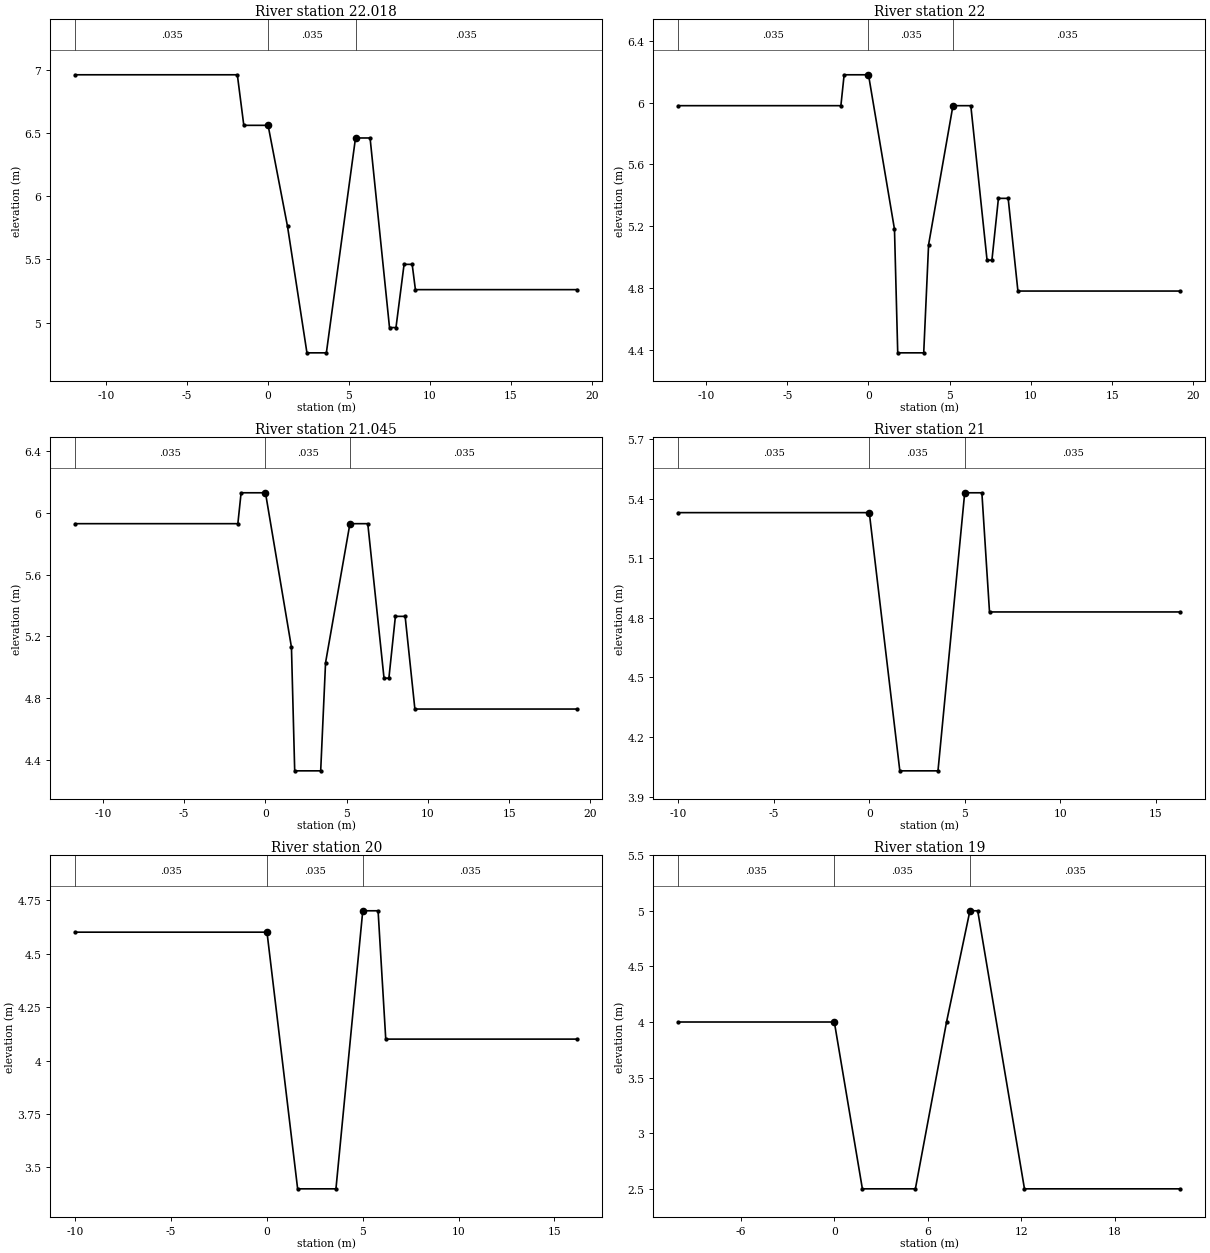
Type RM Length L Ch R = 1 ,22.018  ,18,18,18
#Sta/Elev= 15
   -11.9    6.96    -1.9    6.96    -1.5    6.56       0    6.56     1.2    5.76
     2.4    4.76     3.6    4.76     5.4    6.46     6.3    6.46     7.5    4.96
     7.9    4.96     8.4    5.46     8.9    5.46     9.1    5.26    19.1    5.26
#Mann= 3 , 0 , 0
   -11.9    .035       0       0    .035       0     5.4    .035       0
#XS Ineff= 2 , 0
               0      20     5.4              20
Permanent Ineff=
       F       F
#Block Obstruct= 2 , 0
                             5.4
Bank Sta=0,5.4
XS Rating Curve= 0
Exp/Cntr=.3,.1

Type RM Length L Ch R = 1 ,22      ,5,5,5
#Sta/Elev= 16
   -11.7    5.98    -1.7    5.98    -1.5    6.18       0    6.18     1.6    5.18
     1.8    4.38     3.4    4.38     3.7    5.08     5.2    5.98     6.3    5.98
     7.3    4.98     7.6    4.98       8    5.38     8.6    5.38     9.2    4.78
    19.2    4.78
#Mann= 3 , 0 , 0
   -11.7    .035       0       0    .035       0     5.2    .035       0
#XS Ineff= 2 , 0
               0      20     5.2              20
Permanent Ineff=
       F       F
#Block Obstruct= 2 , 0
                             5.2
Bank Sta=0,5.2
XS Rating Curve= 0
Exp/Cntr=.3,.1

Type RM Length L Ch R = 1 ,21.045  ,45,45,45
#Sta/Elev= 16
   -11.7    5.93    -1.7    5.93    -1.5    6.13       0    6.13     1.6    5.13
     1.8    4.33     3.4    4.33     3.7    5.03     5.2    5.93     6.3    5.93
     7.3    4.93     7.6    4.93       8    5.33     8.6    5.33     9.2    4.73
    19.2    4.73
#Mann= 3 , 0 , 0
   -11.7    .035       0       0    .035       0     5.2    .035       0
#XS Ineff= 2 , 0
               0      20     5.2              20
Permanent Ineff=
       F       F
#Block Obstruct= 2 , 0
                             5.2
Bank Sta=0,5.2
XS Rating Curve= 0
Exp/Cntr=.3,.1

Type RM Length L Ch R = 1 ,21      ,50,50,50
#Sta/Elev= 8
     -10    5.33       0    5.33     1.6    4.03     3.6    4.03       5    5.43
     5.9    5.43     6.3    4.83    16.3    4.83
#Mann= 3 , 0 , 0
     -10    .035       0       0    .035       0       5    .035       0
#XS Ineff= 2 , 0
               0      20       5              20
Permanent Ineff=
       F       F
#Block Obstruct= 2 , 0
                               5
Bank Sta=0,5
XS Rating Curve= 0
Exp/Cntr=.3,.1

Type RM Length L Ch R = 1 ,20      ,50,50,50
#Sta/Elev= 8
     -10     4.6       0     4.6     1.6     3.4     3.6     3.4       5     4.7
     5.8     4.7     6.2     4.1    16.2     4.1
#Mann= 3 , 0 , 0
     -10    .035       0       0    .035       0       5    .035       0
#XS Ineff= 2 , 0
               0      20       5              20
Permanent Ineff=
       F       F
#Block Obstruct= 2 , 0
                               5
Bank Sta=0,5
XS Rating Curve= 0
Exp/Cntr=.3,.1

Type RM Length L Ch R = 1 ,19      ,28,28,28
#Sta/Elev= 9
     -10       4       0       4     1.8     2.5     5.2     2.5     7.2       4
     8.7       5     9.2       5    12.2     2.5    22.2     2.5
#Mann= 3 , 0 , 0
     -10    .035       0       0    .035       0     8.7    .035       0
#XS Ineff= 2 , 0
               0      20     8.7              20
Permanent Ineff=
       F       F
#Block Obstruct= 2 , 0
                             8.7
Bank Sta=0,8.7
XS Rating Curve= 0
Exp/Cntr=.3,.1

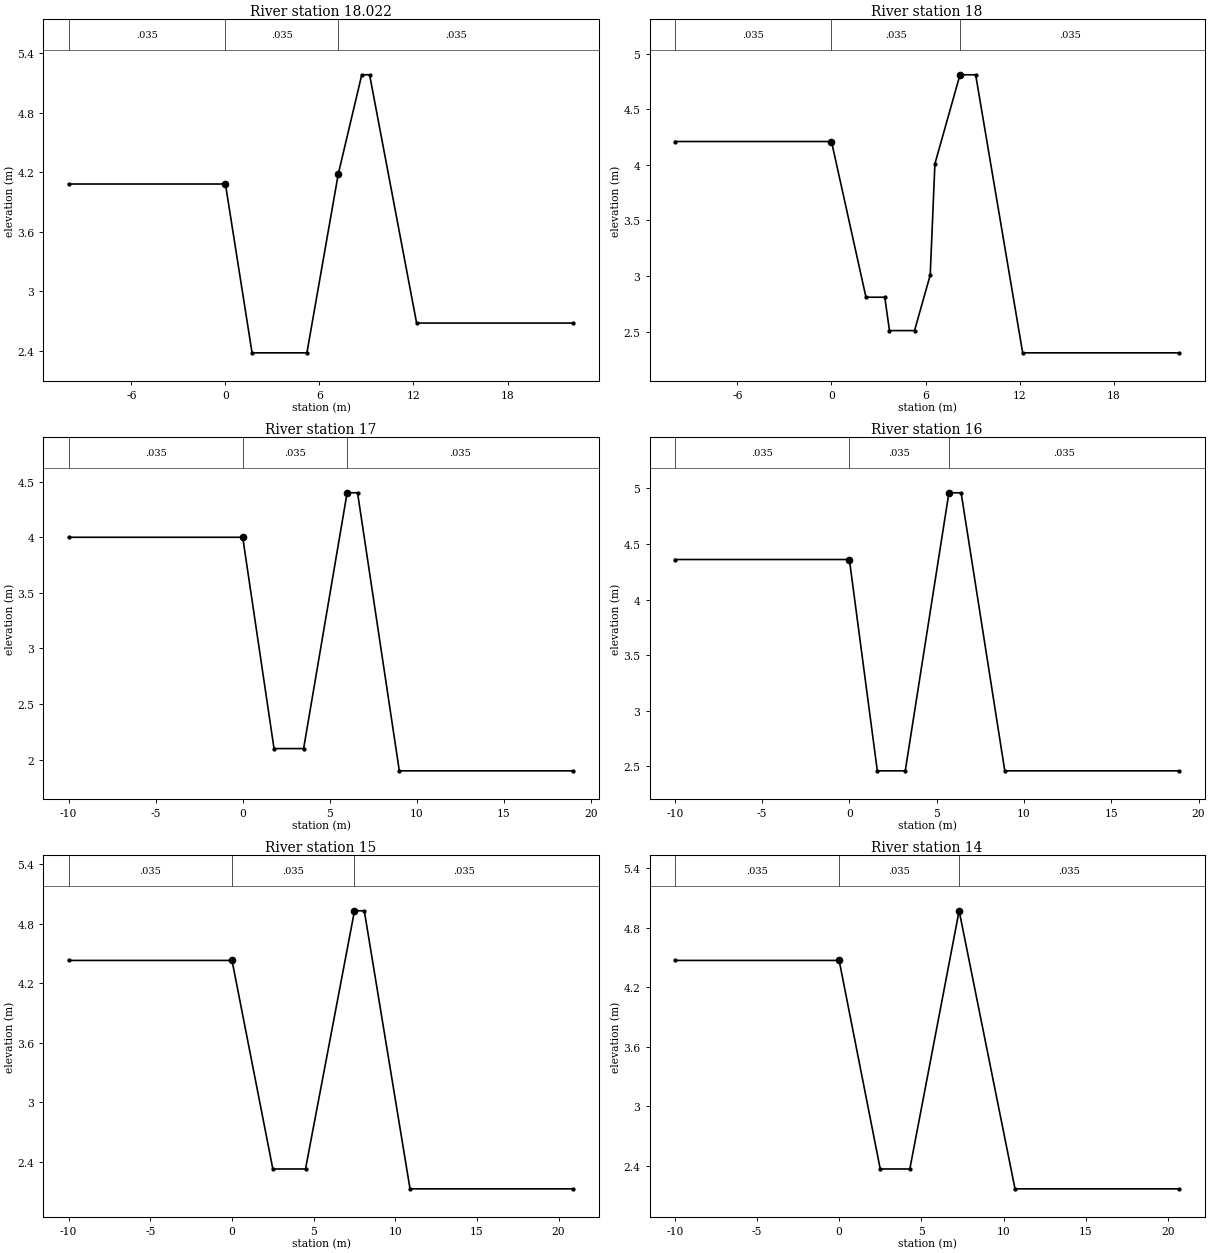
Type RM Length L Ch R = 1 ,18.022  ,22,22,22
#Sta/Elev= 9
     -10    4.08       0    4.08     1.7    2.38     5.2    2.38     7.2    4.18
     8.7    5.18     9.2    5.18    12.2    2.68    22.2    2.68
#Mann= 3 , 0 , 0
     -10    .035       0       0    .035       0     7.2    .035       0
#XS Ineff= 2 , 0
               0      20     7.2              20
Permanent Ineff=
       F       F
#Block Obstruct= 2 , 0
                             7.2
Bank Sta=0,7.2
XS Rating Curve= 0
Exp/Cntr=.3,.1

Type RM Length L Ch R = 1 ,18      ,50,50,50
#Sta/Elev= 12
     -10    4.21       0    4.21     2.2    2.81     3.4    2.81     3.7    2.51
     5.3    2.51     6.3    3.01     6.6    4.01     8.2    4.81     9.2    4.81
    12.2    2.31    22.2    2.31
#Mann= 3 , 0 , 0
     -10    .035       0       0    .035       0     8.2    .035       0
#XS Ineff= 2 , 0
               0      20     8.2              20
Permanent Ineff=
       F       F
#Block Obstruct= 2 , 0
                             8.2
Bank Sta=0,8.2
XS Rating Curve= 0
Exp/Cntr=.3,.1

Type RM Length L Ch R = 1 ,17      ,50,50,50
#Sta/Elev= 8
     -10       4       0       4     1.8     2.1     3.5     2.1       6     4.4
     6.6     4.4       9     1.9      19     1.9
#Mann= 3 , 0 , 0
     -10    .035       0       0    .035       0       6    .035       0
#XS Ineff= 2 , 0
               0      20       6              20
Permanent Ineff=
       F       F
#Block Obstruct= 2 , 0
                               6
Bank Sta=0,6
XS Rating Curve= 0
Exp/Cntr=.3,.1

Type RM Length L Ch R = 1 ,16      ,50,50,50
#Sta/Elev= 8
     -10    4.36       0    4.36     1.6    2.46     3.2    2.46     5.7    4.96
     6.4    4.96     8.9    2.46    18.9    2.46
#Mann= 3 , 0 , 0
     -10    .035       0       0    .035       0     5.7    .035       0
#XS Ineff= 2 , 0
               0      20     5.7              20
Permanent Ineff=
       F       F
#Block Obstruct= 2 , 0
                             5.7
Bank Sta=0,5.7
XS Rating Curve= 0
Exp/Cntr=.3,.1

Type RM Length L Ch R = 1 ,15      ,50,50,50
#Sta/Elev= 8
     -10    4.43       0    4.43     2.5    2.33     4.5    2.33     7.5    4.93
     8.1    4.93    10.9    2.13    20.9    2.13
#Mann= 3 , 0 , 0
     -10    .035       0       0    .035       0     7.5    .035       0
#XS Ineff= 2 , 0
               0      20     7.5              20
Permanent Ineff=
       F       F
#Block Obstruct= 2 , 0
                             7.5
Bank Sta=0,7.5
XS Rating Curve= 0
Exp/Cntr=.3,.1

Type RM Length L Ch R = 1 ,14      ,50,50,50
#Sta/Elev= 7
     -10    4.47       0    4.47     2.5    2.37     4.3    2.37     7.3    4.97
    10.7    2.17    20.7    2.17
#Mann= 3 , 0 , 0
     -10    .035       0       0    .035       0     7.3    .035       0
#XS Ineff= 2 , 0
               0      20     7.3              20
Permanent Ineff=
       F       F
#Block Obstruct= 2 , 0
                             7.3
Bank Sta=0,7.3
XS Rating Curve= 0
Exp/Cntr=.3,.1

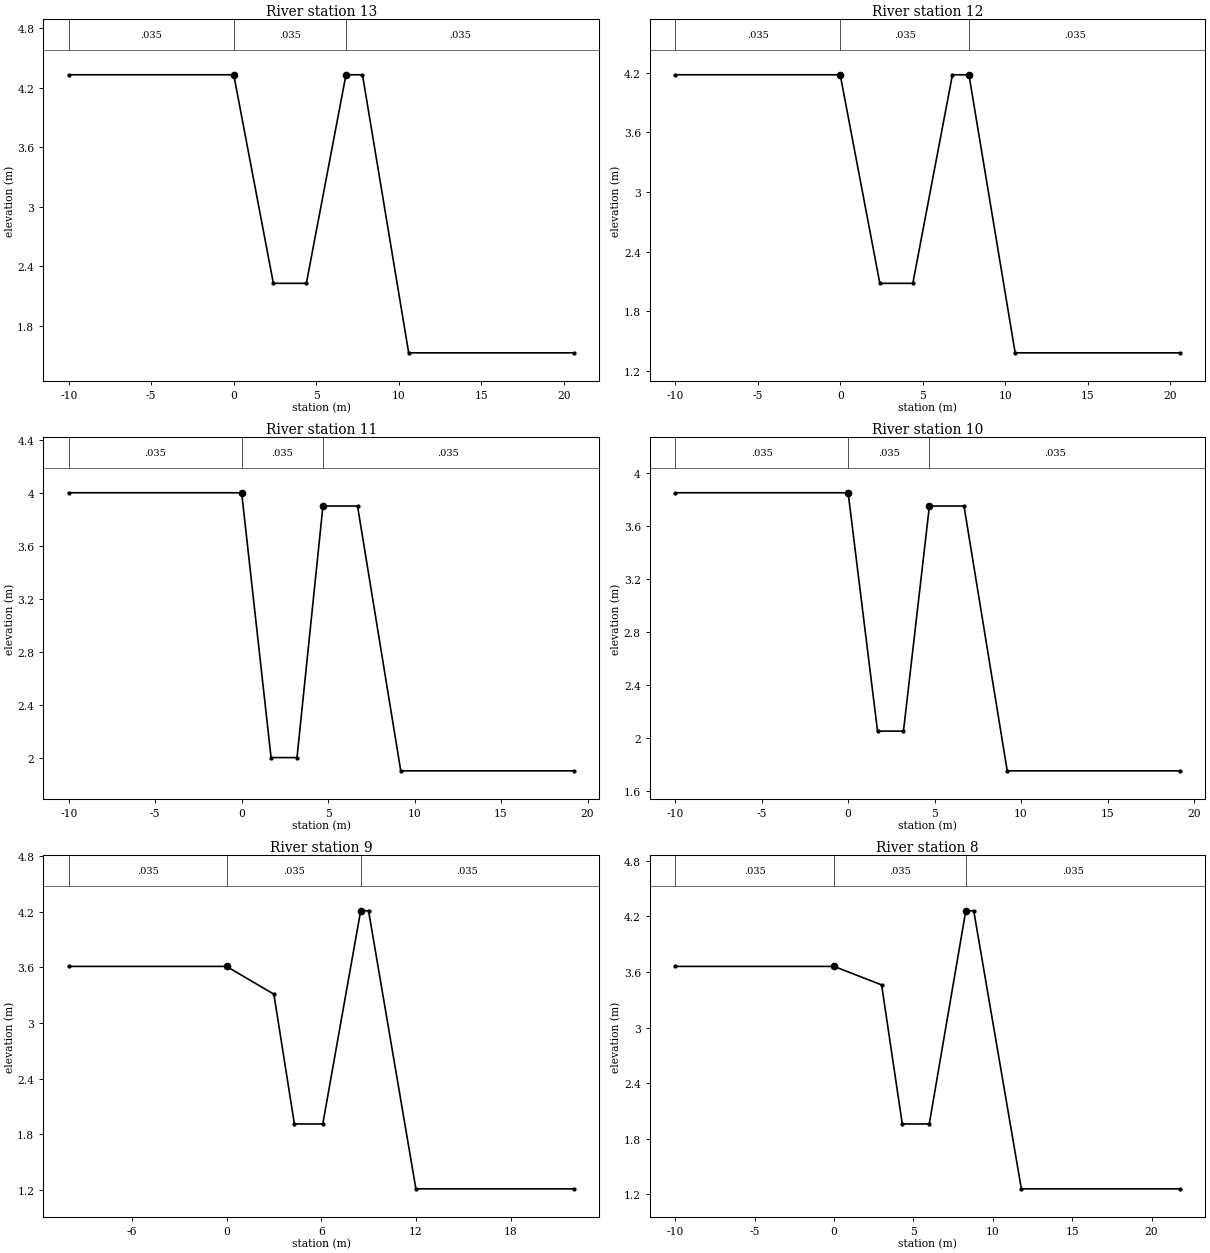
Type RM Length L Ch R = 1 ,13      ,50,50,50
#Sta/Elev= 8
     -10    4.33       0    4.33     2.4    2.23     4.4    2.23     6.8    4.33
     7.8    4.33    10.6    1.53    20.6    1.53
#Mann= 3 , 0 , 0
     -10    .035       0       0    .035       0     6.8    .035       0
#XS Ineff= 2 , 0
               0      20     6.8              20
Permanent Ineff=
       F       F
#Block Obstruct= 2 , 0
                             6.8
Bank Sta=0,6.8
XS Rating Curve= 0
Exp/Cntr=.3,.1

Type RM Length L Ch R = 1 ,12      ,50,50,50
#Sta/Elev= 8
     -10    4.18       0    4.18     2.4    2.08     4.4    2.08     6.8    4.18
     7.8    4.18    10.6    1.38    20.6    1.38
#Mann= 3 , 0 , 0
     -10    .035       0       0    .035       0     7.8    .035       0
#XS Ineff= 2 , 0
               0      20     7.8              20
Permanent Ineff=
       F       F
#Block Obstruct= 2 , 0
                             7.8
Bank Sta=0,7.8
XS Rating Curve= 0
Exp/Cntr=.3,.1

Type RM Length L Ch R = 1 ,11      ,50,50,50
#Sta/Elev= 8
     -10       4       0       4     1.7       2     3.2       2     4.7     3.9
     6.7     3.9     9.2     1.9    19.2     1.9
#Mann= 3 , 0 , 0
     -10    .035       0       0    .035       0     4.7    .035       0
#XS Ineff= 2 , 0
               0      20     4.7              20
Permanent Ineff=
       F       F
#Block Obstruct= 2 , 0
                             4.7
Bank Sta=0,4.7
XS Rating Curve= 0
Exp/Cntr=.3,.1

Type RM Length L Ch R = 1 ,10      ,50,50,50
#Sta/Elev= 8
     -10    3.85       0    3.85     1.7    2.05     3.2    2.05     4.7    3.75
     6.7    3.75     9.2    1.75    19.2    1.75
#Mann= 3 , 0 , 0
     -10    .035       0       0    .035       0     4.7    .035       0
#XS Ineff= 2 , 0
               0      20     4.7              20
Permanent Ineff=
       F       F
#Block Obstruct= 2 , 0
                             4.7
Bank Sta=0,4.7
XS Rating Curve= 0
Exp/Cntr=.3,.1

Type RM Length L Ch R = 1 ,9       ,50,50,50
#Sta/Elev= 9
     -10    3.61       0    3.61       3    3.31     4.3    1.91     6.1    1.91
     8.5    4.21       9    4.21      12    1.21      22    1.21
#Mann= 3 , 0 , 0
     -10    .035       0       0    .035       0     8.5    .035       0
#XS Ineff= 2 , 0
               0      20     8.5              20
Permanent Ineff=
       F       F
#Block Obstruct= 2 , 0
                             8.5
Bank Sta=0,8.5
XS Rating Curve= 0
Exp/Cntr=.3,.1

Type RM Length L Ch R = 1 ,8       ,50,50,50
#Sta/Elev= 9
     -10    3.66       0    3.66       3    3.46     4.3    1.96       6    1.96
     8.3    4.26     8.8    4.26    11.8    1.26    21.8    1.26
#Mann= 3 , 0 , 0
     -10    .035       0       0    .035       0     8.3    .035       0
#XS Ineff= 2 , 0
               0      20     8.3              20
Permanent Ineff=
       F       F
#Block Obstruct= 2 , 0
                             8.3
Bank Sta=0,8.3
XS Rating Curve= 0
Exp/Cntr=.3,.1