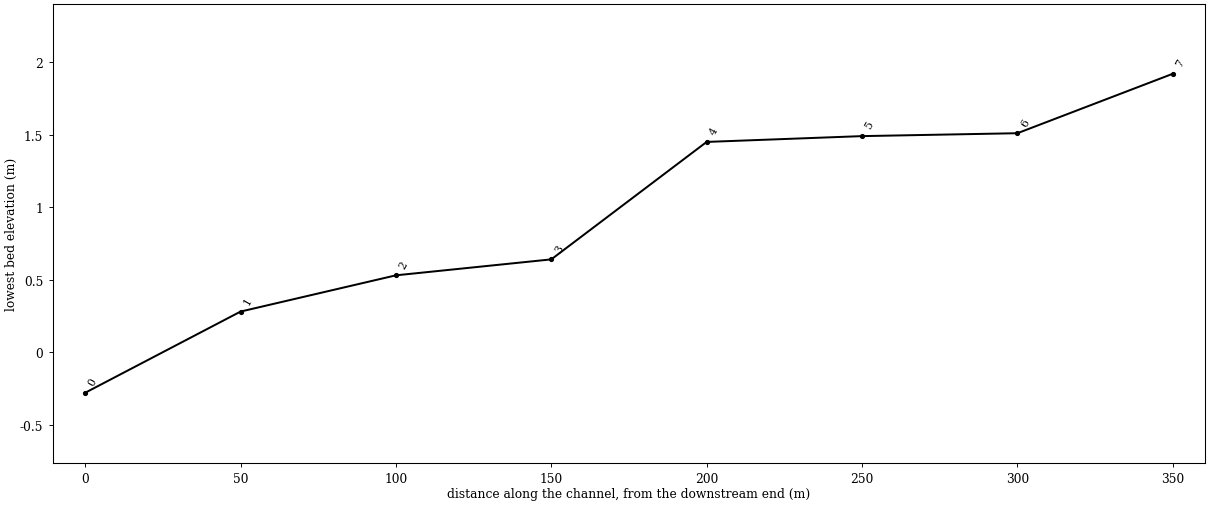
HEC-RAS study HDC.prj: HODONG

--- HDC.g01 (geometry) --- (continued)

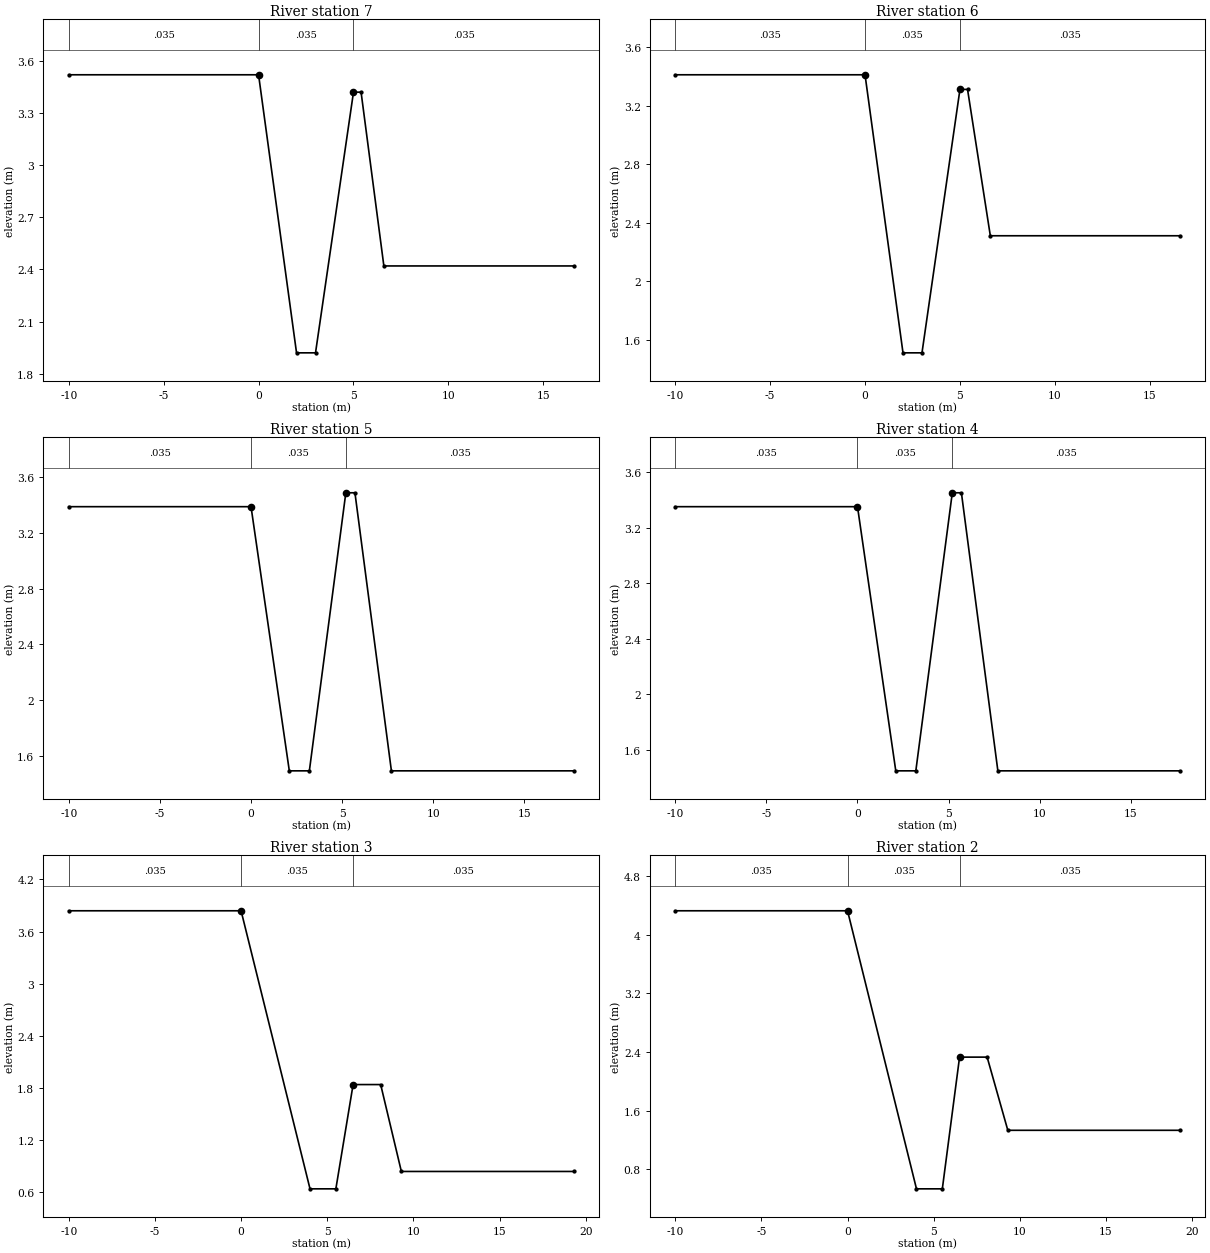
Type RM Length L Ch R = 1 ,7       ,50,50,50
#Sta/Elev= 8
     -10    3.52       0    3.52       2    1.92       3    1.92       5    3.42
     5.4    3.42     6.6    2.42    16.6    2.42
#Mann= 3 , 0 , 0
     -10    .035       0       0    .035       0       5    .035       0
#XS Ineff= 2 , 0
               0      20       5              20
Permanent Ineff=
       F       F
#Block Obstruct= 2 , 0
                               5
Bank Sta=0,5
XS Rating Curve= 0
Exp/Cntr=.3,.1

Type RM Length L Ch R = 1 ,6       ,50,50,50
#Sta/Elev= 8
     -10    3.41       0    3.41       2    1.51       3    1.51       5    3.31
     5.4    3.31     6.6    2.31    16.6    2.31
#Mann= 3 , 0 , 0
     -10    .035       0       0    .035       0       5    .035       0
#XS Ineff= 2 , 0
               0      20       5              20
Permanent Ineff=
       F       F
#Block Obstruct= 2 , 0
                               5
Bank Sta=0,5
XS Rating Curve= 0
Exp/Cntr=.3,.1

Type RM Length L Ch R = 1 ,5       ,50,50,50
#Sta/Elev= 8
     -10    3.39       0    3.39     2.1    1.49     3.2    1.49     5.2    3.49
     5.7    3.49     7.7    1.49    17.7    1.49
#Mann= 3 , 0 , 0
     -10    .035       0       0    .035       0     5.2    .035       0
#XS Ineff= 2 , 0
               0      20     5.2              20
Permanent Ineff=
       F       F
#Block Obstruct= 2 , 0
                             5.2
Bank Sta=0,5.2
XS Rating Curve= 0
Exp/Cntr=.3,.1

Type RM Length L Ch R = 1 ,4       ,50,50,50
#Sta/Elev= 8
     -10    3.35       0    3.35     2.1    1.45     3.2    1.45     5.2    3.45
     5.7    3.45     7.7    1.45    17.7    1.45
#Mann= 3 , 0 , 0
     -10    .035       0       0    .035       0     5.2    .035       0
#XS Ineff= 2 , 0
               0      20     5.2              20
Permanent Ineff=
       F       F
#Block Obstruct= 2 , 0
                             5.2
Bank Sta=0,5.2
XS Rating Curve= 0
Exp/Cntr=.3,.1

Type RM Length L Ch R = 1 ,3       ,50,50,50
#Sta/Elev= 8
     -10    3.84       0    3.84       4     .64     5.5     .64     6.5    1.84
     8.1    1.84     9.3     .84    19.3     .84
#Mann= 3 , 0 , 0
     -10    .035       0       0    .035       0     6.5    .035       0
#XS Ineff= 2 , 0
               0      20     6.5              20
Permanent Ineff=
       F       F
#Block Obstruct= 2 , 0
                             6.5
Bank Sta=0,6.5
XS Rating Curve= 0
Exp/Cntr=.3,.1

Type RM Length L Ch R = 1 ,2       ,50,50,50
#Sta/Elev= 8
     -10    4.33       0    4.33       4     .53     5.5     .53     6.5    2.33
     8.1    2.33     9.3    1.33    19.3    1.33
#Mann= 3 , 0 , 0
     -10    .035       0       0    .035       0     6.5    .035       0
#XS Ineff= 2 , 0
               0      20     6.5              20
Permanent Ineff=
       F       F
#Block Obstruct= 2 , 0
                             6.5
Bank Sta=0,6.5
XS Rating Curve= 0
Exp/Cntr=.3,.1

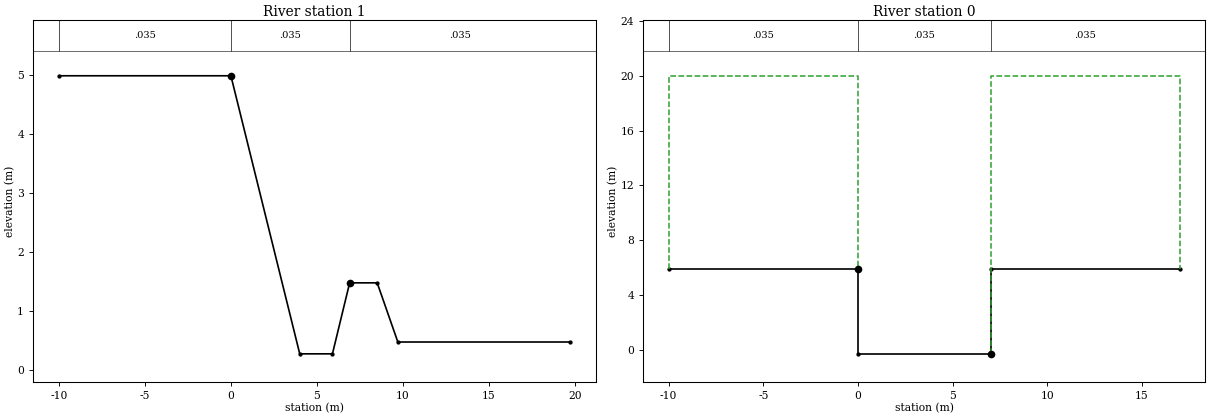
Type RM Length L Ch R = 1 ,1       ,50,50,50
#Sta/Elev= 8
     -10    4.98       0    4.98       4     .28     5.9     .28     6.9    1.48
     8.5    1.48     9.7     .48    19.7     .48
#Mann= 3 , 0 , 0
     -10    .035       0       0    .035       0     6.9    .035       0
#XS Ineff= 2 , 0
               0      20     6.9              20
Permanent Ineff=
       F       F
#Block Obstruct= 2 , 0
                             6.9
Bank Sta=0,6.9
XS Rating Curve= 0
Exp/Cntr=.3,.1

Type RM Length L Ch R = 1 ,0       ,0,0,0
#Sta/Elev= 6
     -10    5.92       0    5.92       0    -.28       7    -.28       7    5.92
      17    5.92
#Mann= 3 , 0 , 0
     -10    .035       0       0    .035       0       7    .035       0
#XS Ineff= 2 , 0
               0      20       7              20
Permanent Ineff=
       F       F
#Block Obstruct= 2 , 0
                               7
Bank Sta=0,7
XS Rating Curve= 0
Exp/Cntr=.3,.1

Chan Stop Cuts=-1