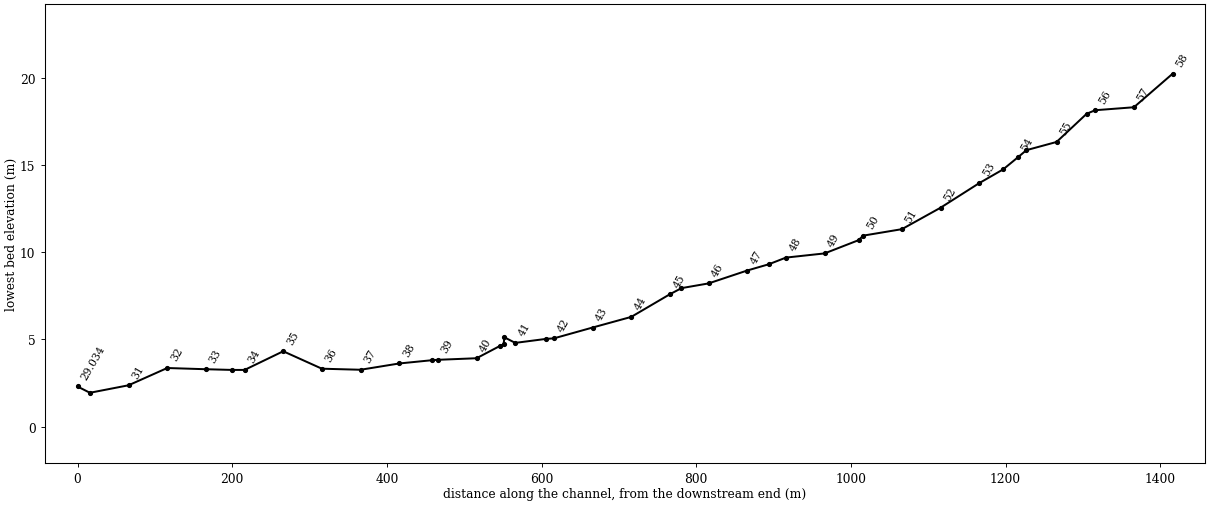
--- mhc.prj (project) ---

Proj Title=myunhwa
Current Plan=p01
Default Exp/Contr=.3,.1
SI Units
Geom File=g01
Flow File=f01
Plan File=p01
Y Axis Title=Elevation
X Axis Title(PF)=Main Channel Distance
X Axis Title(XS)=Station
BEGIN DESCRIPTION:
           BACK WATER COMPUTATION
      APPLICATION OF HEC-2 BY Samju Construction Engineering
      meunwha-ch: 10,20,30,50,80 yr
END DESCRIPTION:
DSS Export Rating Curves= 0
DSS Export Rating Curve Sorted= 0
DSS Export Volume Flow Curves= 0
DXF OffsetX= 0
DXF OffsetY= 0
DXF ScaleX= 1
DXF ScaleY= 10

--- mhc.p01 (plan) ---

Plan Title=Imported Plan 01
Version=Version 3.0.1  Mar 2001
Short Identifier=Imported Pla
Geom File=g01
Flow File=f01
Subcritical Flow
K Sum by GR= 0
Std Step Tol= 0.003
Critical Tol= 0.003
Num of Std Step Trials= 20
Max Error Tol= 0.1
Flow Tol Ratio= 0.001
Split Flow NTrial= 30
Split Flow Tol= 0.02
Split Flow Ratio= 0.02
Log Output Level= 0
Friction Slope Method= 1
Unsteady Friction Slope Method= 2
Parabolic Critical Depth
Global Vel Dist= 0 , 0 , 0
Global Log Level= 0
CheckData=True
Encroach Param=-1 ,0,0, 0
Computation Interval=1HOUR
Output Interval=1HOUR
Run HTab= 0
Run UNet= 0
Run PostProcess= 0
UNET Theta= 1
UNET ZTol= 0.02
UNET ZSATol= 0.1
UNET MxIter= 20
UNET MaxInSteps= 20
UNET DtIC= 0
UNET DtMin= 0
UNET MaxCRTS= 20
UNET WFStab= 2
UNET SFStab= 1
UNET WFX= 1
UNET SFX= 1
UNET Convert EG Bridges=-1
UNET Use Existing IB Tables=-1
Instantaneous Interval=1HOUR
Write IC File= 0
Write Velocity= 0
Write Detailed= 0

--- mhc.f01 (steady flow) ---

Flow Title=Imported Flow 01
Version=Version 3.0.1  Mar 2001
Number of Profiles= 1
Profile Names=PF 1
River Rch & RM=RIVER-1,Reach-1         ,58
     180
Boundary for River Rch & Prof#=RIVER-1,Reach-1         , 1
Up Type= 0
Dn Type= 3
Dn Slope=.0109
DSS Import GetInterval= 0
DSS Import GetPeak= 0
DSS Import FillOption= 0

--- mhc.g01 (geometry) ---

Geom Title=Imported Geom 01
Version=Version 3.0.1  Mar 2001

River Reach=RIVER-1         ,Reach-1
Reach XY= 2
              .5             .95              .5             .05

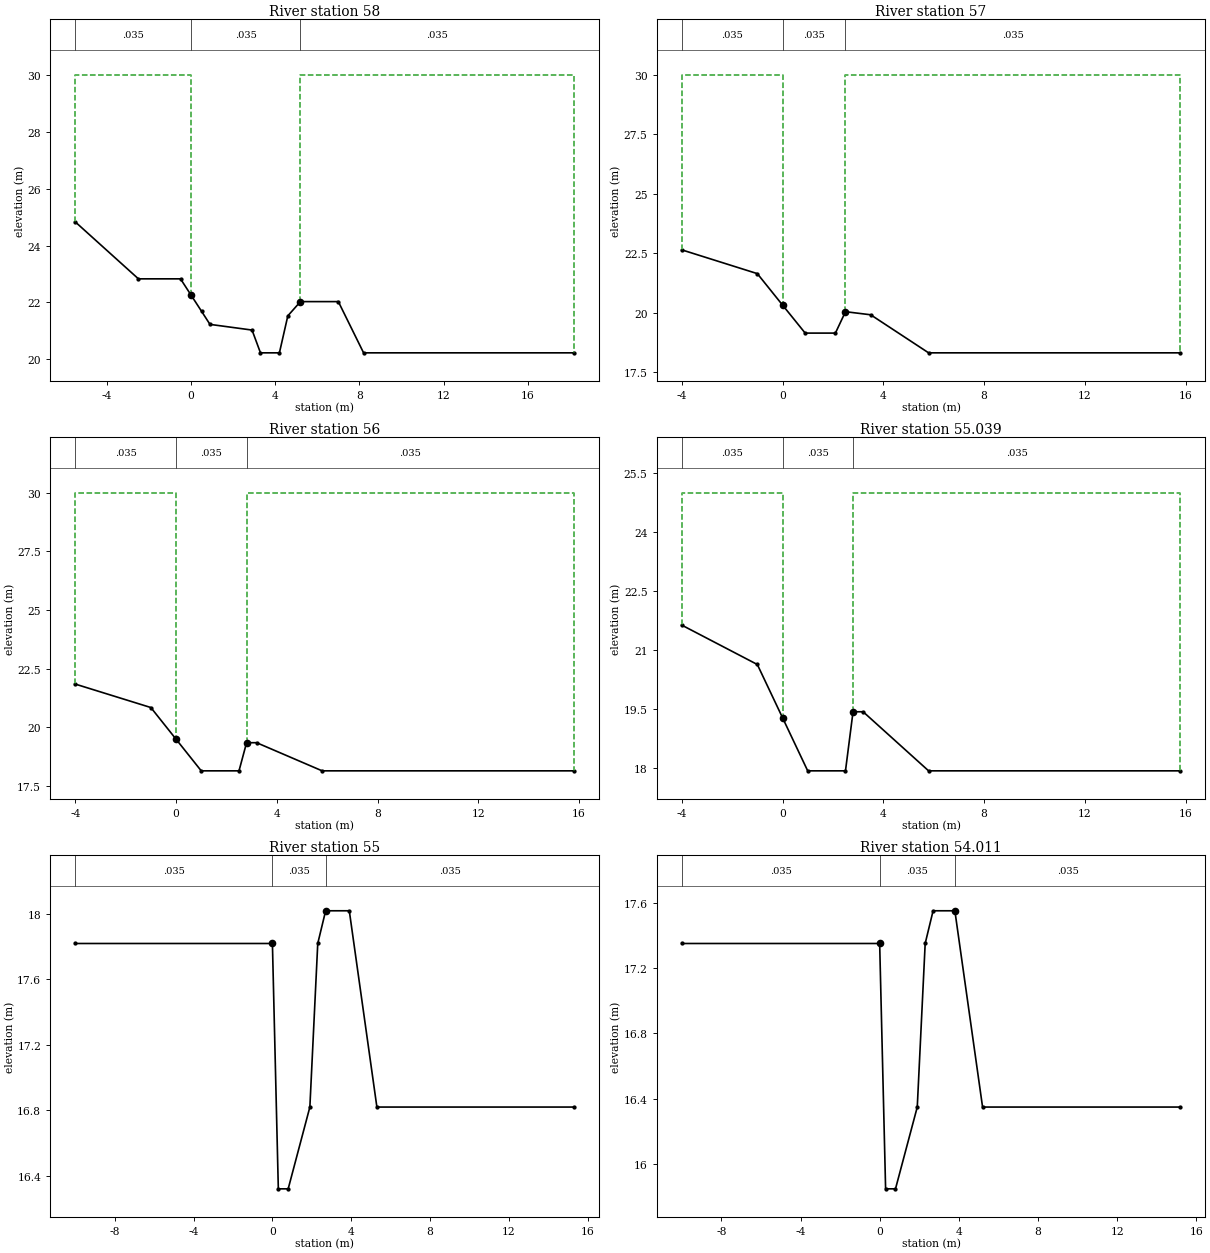
Type RM Length L Ch R = 1 ,58      ,50,50,50
#Sta/Elev= 14
    -5.5   24.83    -2.5   22.83     -.5   22.83       0   22.26      .5   21.69
      .9   21.23     2.9   21.03     3.3   20.23     4.2   20.23     4.6   21.53
     5.2   22.03       7   22.03     8.2   20.23    18.2   20.23
#Mann= 3 , 0 , 0
    -5.5    .035       0       0    .035       0     5.2    .035       0
#XS Ineff= 2 , 0
               0      30     5.2              30
Permanent Ineff=
       F       F
#Block Obstruct= 2 , 0
                             5.2
Bank Sta=0,5.2
XS Rating Curve= 0
Exp/Cntr=.3,.1

Type RM Length L Ch R = 1 ,57      ,50,50,50
#Sta/Elev= 9
      -4   22.64      -1   21.64       0   20.32      .9   19.14     2.1   19.14
     2.5   20.04     3.5   19.91     5.8   18.31    15.8   18.31
#Mann= 3 , 0 , 0
      -4    .035       0       0    .035       0     2.5    .035       0
#XS Ineff= 2 , 0
               0      30     2.5              30
Permanent Ineff=
       F       F
#Block Obstruct= 2 , 0
                             2.5
Bank Sta=0,2.5
XS Rating Curve= 0
Exp/Cntr=.3,.1

Type RM Length L Ch R = 1 ,56      ,11,11,11
#Sta/Elev= 9
      -4   21.84      -1   20.84       0   19.49       1   18.14     2.5   18.14
     2.8   19.34     3.2   19.34     5.8   18.14    15.8   18.14
#Mann= 3 , 0 , 0
      -4    .035       0       0    .035       0     2.8    .035       0
#XS Ineff= 2 , 0
               0      30     2.8              30
Permanent Ineff=
       F       F
#Block Obstruct= 2 , 0
                             2.8
Bank Sta=0,2.8
XS Rating Curve= 0
Exp/Cntr=.3,.1

Type RM Length L Ch R = 1 ,55.039  ,39,39,39
#Sta/Elev= 9
      -4   21.64      -1   20.64       0   19.29       1   17.94     2.5   17.94
     2.8   19.44     3.2   19.44     5.8   17.94    15.8   17.94
#Mann= 3 , 0 , 0
      -4    .035       0       0    .035       0     2.8    .035       0
#XS Ineff= 2 , 0
               0      25     2.8              25
Permanent Ineff=
       F       F
#Block Obstruct= 2 , 0
                             2.8
Bank Sta=0,2.8
XS Rating Curve= 0
Exp/Cntr=.3,.1

Type RM Length L Ch R = 1 ,55      ,39,39,39
#Sta/Elev= 10
     -10   17.82       0   17.82      .3   16.32      .8   16.32     1.9   16.82
     2.3   17.82     2.7   18.02     3.9   18.02     5.3   16.82    15.3   16.82
#Mann= 3 , 0 , 0
     -10    .035       0       0    .035       0     2.7    .035       0
#XS Ineff= 2 , 0
               0      25     2.7              25
Permanent Ineff=
       F       F
#Block Obstruct= 2 , 0
                             2.7
Bank Sta=0,2.7
XS Rating Curve= 0
Exp/Cntr=.3,.1

Type RM Length L Ch R = 1 ,54.011  ,11,11,11
#Sta/Elev= 10
     -10   17.35       0   17.35      .3   15.85      .8   15.85     1.9   16.35
     2.3   17.35     2.7   17.55     3.8   17.55     5.2   16.35    15.2   16.35
#Mann= 3 , 0 , 0
     -10    .035       0       0    .035       0     3.8    .035       0
#XS Ineff= 2 , 0
               0      25     3.8              25
Permanent Ineff=
       F       F
#Block Obstruct= 2 , 0
                             3.8
Bank Sta=0,3.8
XS Rating Curve= 0
Exp/Cntr=.3,.1

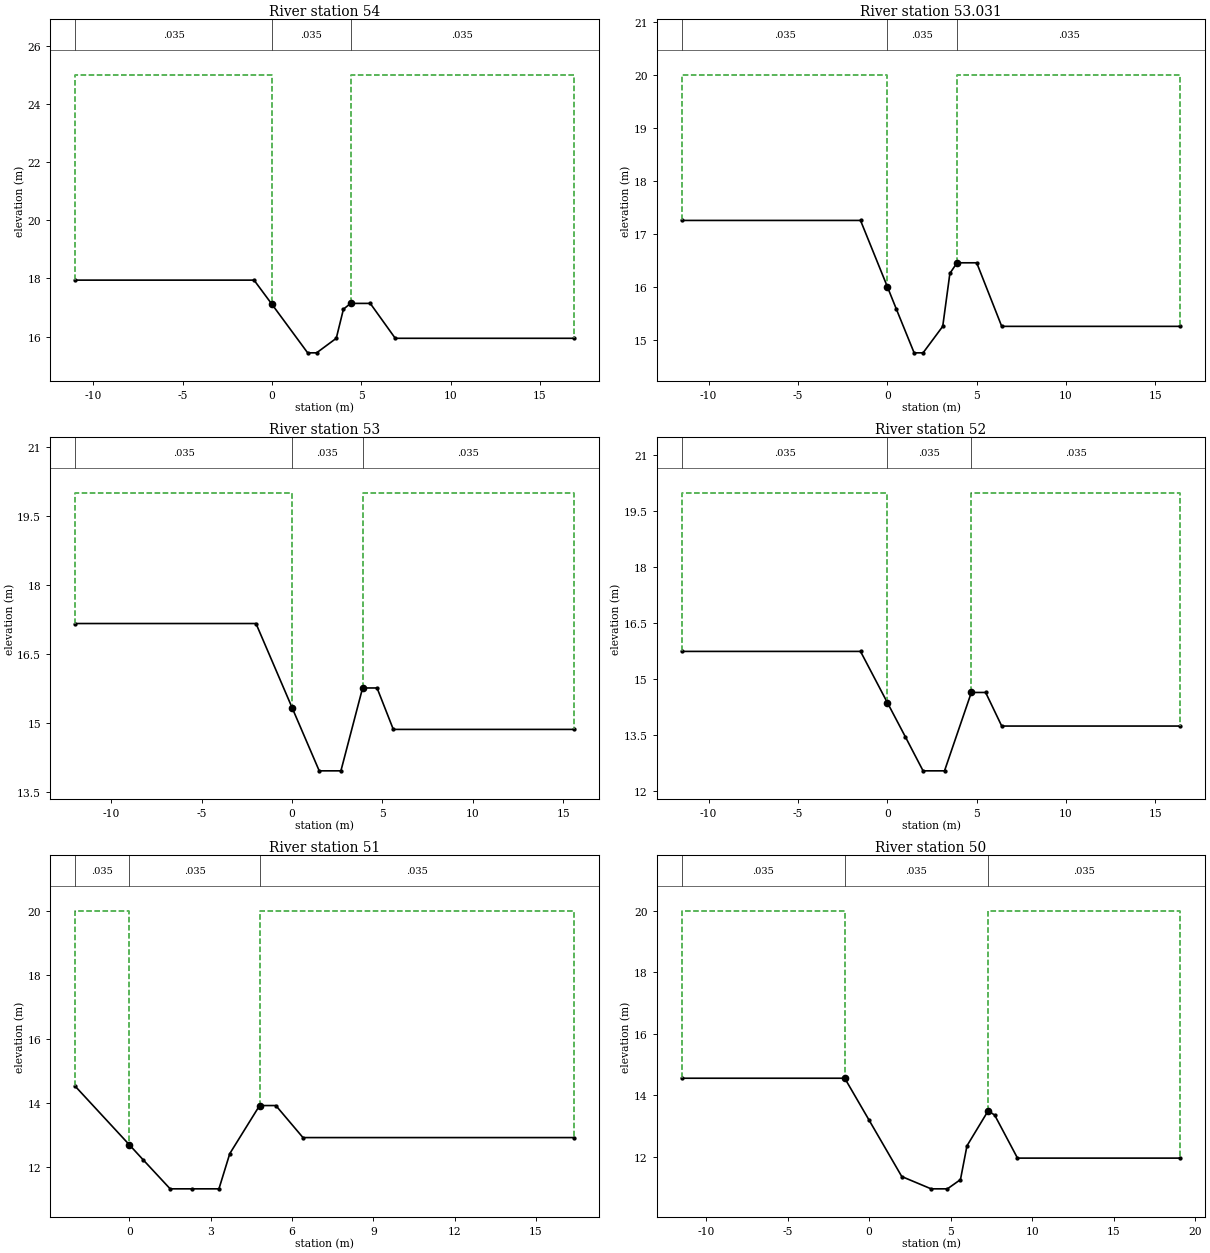
Type RM Length L Ch R = 1 ,54      ,19,19,19
#Sta/Elev= 11
     -11   17.94      -1   17.94       0   17.11       2   15.44     2.5   15.44
     3.6   15.94       4   16.94     4.4   17.14     5.5   17.14     6.9   15.94
    16.9   15.94
#Mann= 3 , 0 , 0
     -11    .035       0       0    .035       0     4.4    .035       0
#XS Ineff= 2 , 0
               0      25     4.4              25
Permanent Ineff=
       F       F
#Block Obstruct= 2 , 0
                             4.4
Bank Sta=0,4.4
XS Rating Curve= 0
Exp/Cntr=.3,.1

Type RM Length L Ch R = 1 ,53.031  ,31,31,31
#Sta/Elev= 12
   -11.5   17.25    -1.5   17.25       0      16      .5   15.58     1.5   14.75
       2   14.75     3.1   15.25     3.5   16.25     3.9   16.45       5   16.45
     6.4   15.25    16.4   15.25
#Mann= 3 , 0 , 0
   -11.5    .035       0       0    .035       0     3.9    .035       0
#XS Ineff= 2 , 0
               0      20     3.9              20
Permanent Ineff=
       F       F
#Block Obstruct= 2 , 0
                             3.9
Bank Sta=0,3.9
XS Rating Curve= 0
Exp/Cntr=.3,.1

Type RM Length L Ch R = 1 ,53      ,50,50,50
#Sta/Elev= 9
     -12   17.16      -2   17.16       0   15.33     1.5   13.96     2.7   13.96
     3.9   15.76     4.7   15.76     5.6   14.86    15.6   14.86
#Mann= 3 , 0 , 0
     -12    .035       0       0    .035       0     3.9    .035       0
#XS Ineff= 2 , 0
               0      20     3.9              20
Permanent Ineff=
       F       F
#Block Obstruct= 2 , 0
                             3.9
Bank Sta=0,3.9
XS Rating Curve= 0
Exp/Cntr=.3,.1

Type RM Length L Ch R = 1 ,52      ,50,50,50
#Sta/Elev= 10
   -11.5   15.75    -1.5   15.75       0   14.38       1   13.47       2   12.55
     3.2   12.55     4.7   14.65     5.5   14.65     6.4   13.75    16.4   13.75
#Mann= 3 , 0 , 0
   -11.5    .035       0       0    .035       0     4.7    .035       0
#XS Ineff= 2 , 0
               0      20     4.7              20
Permanent Ineff=
       F       F
#Block Obstruct= 2 , 0
                             4.7
Bank Sta=0,4.7
XS Rating Curve= 0
Exp/Cntr=.3,.1

Type RM Length L Ch R = 1 ,51      ,50,50,50
#Sta/Elev= 11
      -2   14.52       0   12.69      .5   12.23     1.5   11.32     2.3   11.32
     3.3   11.32     3.7   12.42     4.8   13.92     5.4   13.92     6.4   12.92
    16.4   12.92
#Mann= 3 , 0 , 0
      -2    .035       0       0    .035       0     4.8    .035       0
#XS Ineff= 2 , 0
               0      20     4.8              20
Permanent Ineff=
       F       F
#Block Obstruct= 2 , 0
                             4.8
Bank Sta=0,4.8
XS Rating Curve= 0
Exp/Cntr=.3,.1

Type RM Length L Ch R = 1 ,50      ,6,6,6
#Sta/Elev= 12
   -11.5   14.55    -1.5   14.55       0   13.18       2   11.35     3.8   10.95
     4.8   10.95     5.6   11.25       6   12.35     7.3   13.49     7.7   13.35
     9.1   11.95    19.1   11.95
#Mann= 3 , 0 , 0
   -11.5    .035       0    -1.5    .035       0     7.3    .035       0
#XS Ineff= 2 , 0
            -1.5      20     7.3              20
Permanent Ineff=
       F       F
#Block Obstruct= 2 , 0
            -1.5             7.3
Bank Sta=-1.5,7.3
XS Rating Curve= 0
Exp/Cntr=.3,.1

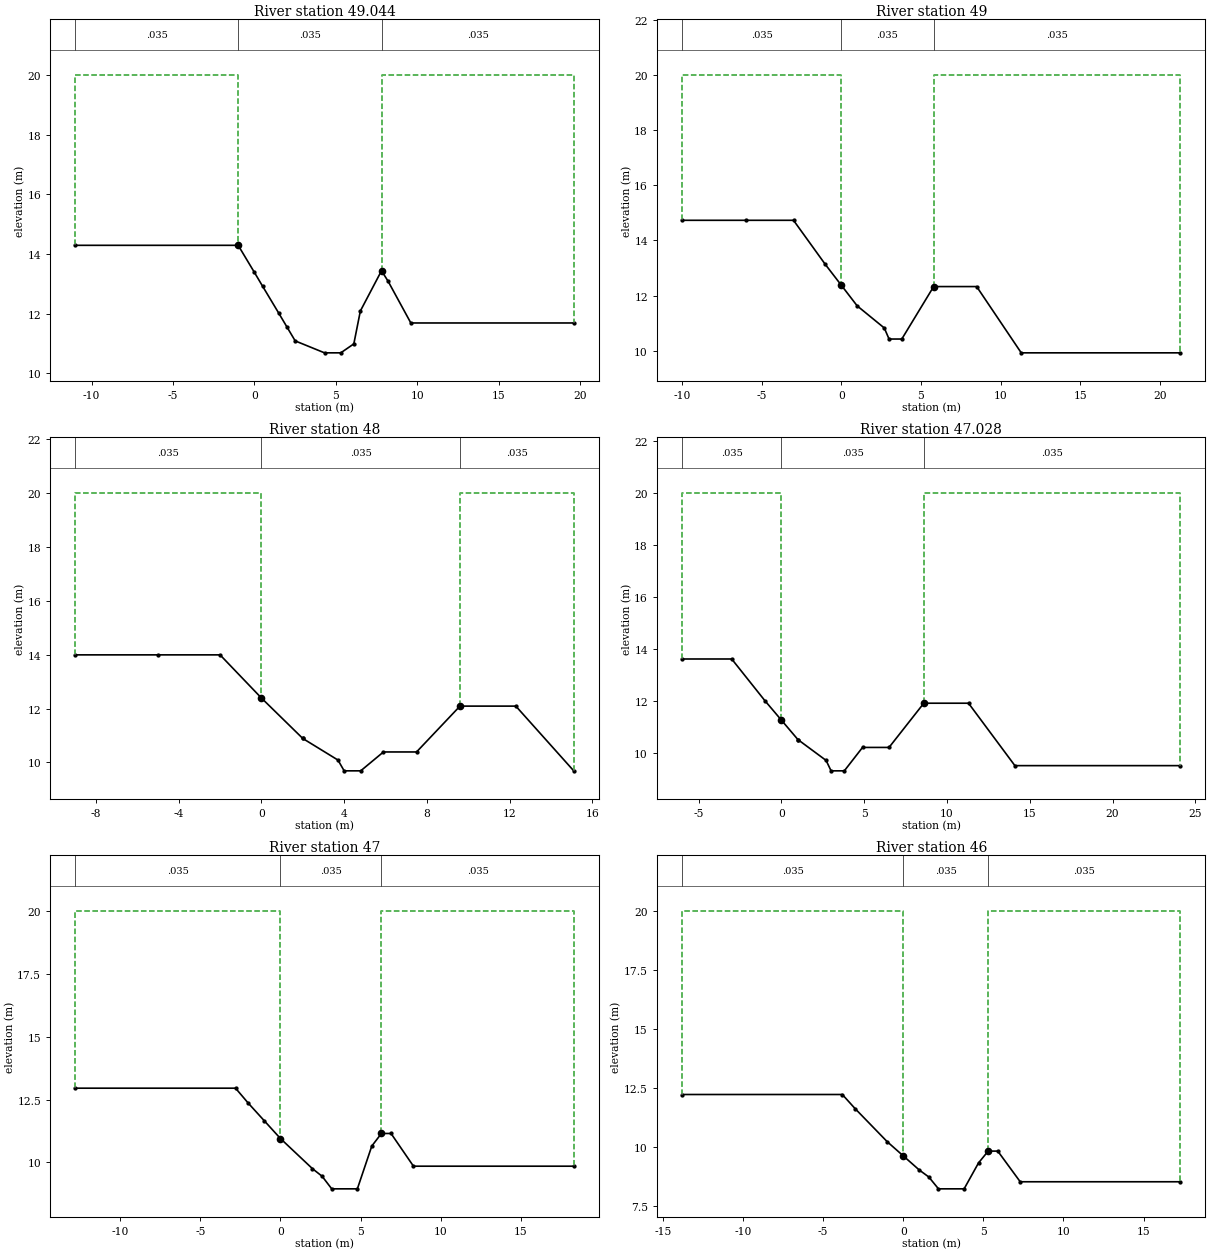
Type RM Length L Ch R = 1 ,49.044  ,44,44,44
#Sta/Elev= 15
     -11   14.29      -1   14.29       0   13.38      .5   12.92     1.5   12.01
       2   11.55     2.5   11.09     4.3   10.69     5.3   10.69     6.1   10.99
     6.5   12.09     7.8   13.44     8.2   13.09     9.6   11.69    19.6   11.69
#Mann= 3 , 0 , 0
     -11    .035       0      -1    .035       0     7.8    .035       0
#XS Ineff= 2 , 0
              -1      20     7.8              20
Permanent Ineff=
       F       F
#Block Obstruct= 2 , 0
              -1             7.8
Bank Sta=-1,7.8
XS Rating Curve= 0
Exp/Cntr=.3,.1

Type RM Length L Ch R = 1 ,49      ,50,50,50
#Sta/Elev= 13
     -10   14.73      -6   14.73      -3   14.73      -1   13.13       0   12.38
       1   11.63     2.7   10.83       3   10.43     3.8   10.43     5.8   12.33
     8.5   12.33    11.3    9.93    21.3    9.93
#Mann= 3 , 0 , 0
     -10    .035       0       0    .035       0     5.8    .035       0
#XS Ineff= 2 , 0
               0      20     5.8              20
Permanent Ineff=
       F       F
#Block Obstruct= 2 , 0
                             5.8
Bank Sta=0,5.8
XS Rating Curve= 0
Exp/Cntr=.3,.1

Type RM Length L Ch R = 1 ,48      ,22,22,22
#Sta/Elev= 14
      -9   13.99      -5   13.99      -2   13.99       0   12.39       2   10.89
       2   10.89     3.7   10.09       4    9.69     4.8    9.69     5.9   10.39
     7.5   10.39     9.6   12.09    12.3   12.09    15.1    9.69
#Mann= 3 , 0 , 0
      -9    .035       0       0    .035       0     9.6    .035       0
#XS Ineff= 2 , 0
               0      20     9.6              20
Permanent Ineff=
       F       F
#Block Obstruct= 2 , 0
                             9.6
Bank Sta=0,9.6
XS Rating Curve= 0
Exp/Cntr=.3,.1

Type RM Length L Ch R = 1 ,47.028  ,28,28,28
#Sta/Elev= 15
      -6   13.61      -3   13.61      -1   12.01       0   11.26       1   10.51
       1   10.51     2.7    9.71       3    9.31     3.8    9.31     4.9   10.21
     6.5   10.21     8.6   11.91    11.3   11.91    14.1    9.51    24.1    9.51
#Mann= 3 , 0 , 0
      -6    .035       0       0    .035       0     8.6    .035       0
#XS Ineff= 2 , 0
               0      20     8.6              20
Permanent Ineff=
       F       F
#Block Obstruct= 2 , 0
                             8.6
Bank Sta=0,8.6
XS Rating Curve= 0
Exp/Cntr=.3,.1

Type RM Length L Ch R = 1 ,47      ,50,50,50
#Sta/Elev= 14
   -12.8   12.95    -2.8   12.95      -2   12.35      -1   11.65       0   10.95
       2    9.75     2.6    9.45     3.2    8.95     4.8    8.95     5.7   10.65
     6.3   11.15     6.9   11.15     8.3    9.85    18.3    9.85
#Mann= 3 , 0 , 0
   -12.8    .035       0       0    .035       0     6.3    .035       0
#XS Ineff= 2 , 0
               0      20     6.3              20
Permanent Ineff=
       F       F
#Block Obstruct= 2 , 0
                             6.3
Bank Sta=0,6.3
XS Rating Curve= 0
Exp/Cntr=.3,.1

Type RM Length L Ch R = 1 ,46      ,35,35,35
#Sta/Elev= 14
   -13.8   12.21    -3.8   12.21      -3   11.61      -1   10.21       0    9.61
       1    9.01     1.6    8.71     2.2    8.21     3.8    8.21     4.7    9.31
     5.3    9.81     5.9    9.81     7.3    8.51    17.3    8.51
#Mann= 3 , 0 , 0
   -13.8    .035       0       0    .035       0     5.3    .035       0
#XS Ineff= 2 , 0
               0      20     5.3              20
Permanent Ineff=
       F       F
#Block Obstruct= 2 , 0
                             5.3
Bank Sta=0,5.3
XS Rating Curve= 0
Exp/Cntr=.3,.1

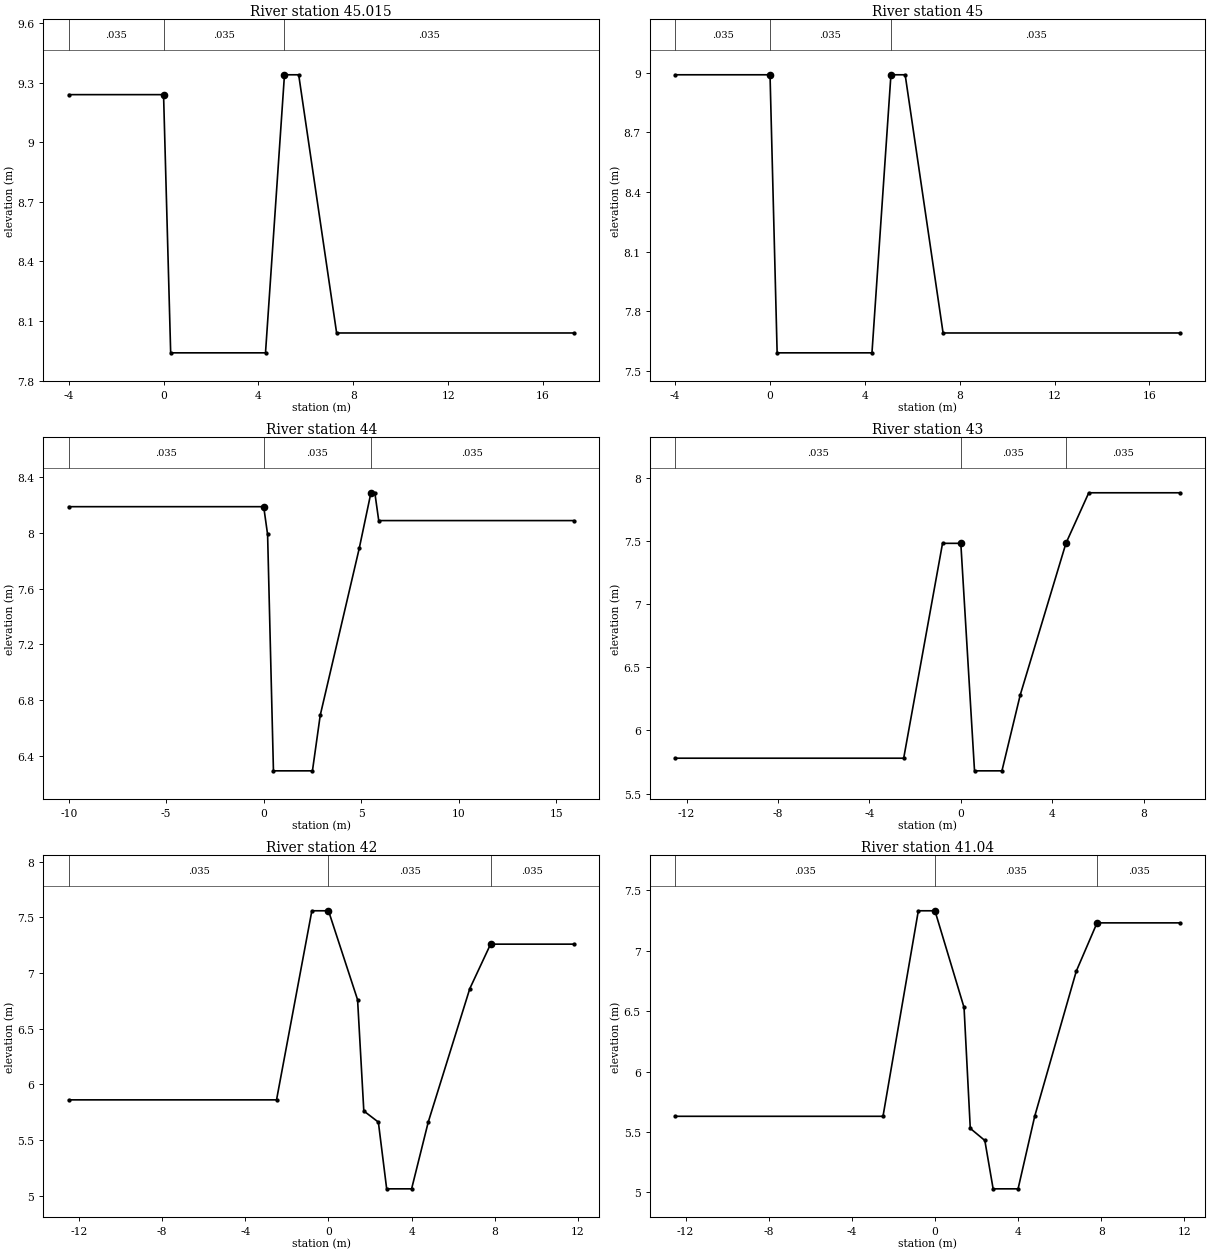
Type RM Length L Ch R = 1 ,45.015  ,15,15,15
#Sta/Elev= 8
      -4    9.24       0    9.24      .3    7.94     4.3    7.94     5.1    9.34
     5.7    9.34     7.3    8.04    17.3    8.04
#Mann= 3 , 0 , 0
      -4    .035       0       0    .035       0     5.1    .035       0
#XS Ineff= 2 , 0
               0      20     5.1              20
Permanent Ineff=
       F       F
#Block Obstruct= 2 , 0
                             5.1
Bank Sta=0,5.1
XS Rating Curve= 0
Exp/Cntr=.3,.1

Type RM Length L Ch R = 1 ,45      ,50,50,50
#Sta/Elev= 8
      -4    8.99       0    8.99      .3    7.59     4.3    7.59     5.1    8.99
     5.7    8.99     7.3    7.69    17.3    7.69
#Mann= 3 , 0 , 0
      -4    .035       0       0    .035       0     5.1    .035       0
#XS Ineff= 2 , 0
               0      20     5.1              20
Permanent Ineff=
       F       F
#Block Obstruct= 2 , 0
                             5.1
Bank Sta=0,5.1
XS Rating Curve= 0
Exp/Cntr=.3,.1

Type RM Length L Ch R = 1 ,44      ,50,50,50
#Sta/Elev= 11
     -10    8.19       0    8.19      .2    7.99      .5    6.29     2.5    6.29
     2.9    6.69     4.9    7.89     5.5    8.29     5.7    8.29     5.9    8.09
    15.9    8.09
#Mann= 3 , 0 , 0
     -10    .035       0       0    .035       0     5.5    .035       0
#XS Ineff= 2 , 0
               0      20     5.5              20
Permanent Ineff=
       F       F
#Block Obstruct= 2 , 0
                             5.5
Bank Sta=0,5.5
XS Rating Curve= 0
Exp/Cntr=.3,.1

Type RM Length L Ch R = 1 ,43      ,50,50,50
#Sta/Elev= 10
   -12.5    5.78    -2.5    5.78     -.8    7.48       0    7.48      .6    5.68
     1.8    5.68     2.6    6.28     4.6    7.48     5.6    7.88     9.6    7.88
#Mann= 3 , 0 , 0
   -12.5    .035       0       0    .035       0     4.6    .035       0
#XS Ineff= 2 , 0
               0      20     4.6              20
Permanent Ineff=
       F       F
#Block Obstruct= 2 , 0
                             4.6
Bank Sta=0,4.6
XS Rating Curve= 0
Exp/Cntr=.3,.1

Type RM Length L Ch R = 1 ,42      ,10,10,10
#Sta/Elev= 13
   -12.5    5.86    -2.5    5.86     -.8    7.56       0    7.56     1.4    6.76
     1.7    5.76     2.4    5.66     2.8    5.06       4    5.06     4.8    5.66
     6.8    6.86     7.8    7.26    11.8    7.26
#Mann= 3 , 0 , 0
   -12.5    .035       0       0    .035       0     7.8    .035       0
#XS Ineff= 2 , 0
               0      20     7.8              20
Permanent Ineff=
       F       F
#Block Obstruct= 2 , 0
                             7.8
Bank Sta=0,7.8
XS Rating Curve= 0
Exp/Cntr=.3,.1

Type RM Length L Ch R = 1 ,41.04   ,40,40,40
#Sta/Elev= 13
   -12.5    5.63    -2.5    5.63     -.8    7.33       0    7.33     1.4    6.53
     1.7    5.53     2.4    5.43     2.8    5.03       4    5.03     4.8    5.63
     6.8    6.83     7.8    7.23    11.8    7.23
#Mann= 3 , 0 , 0
   -12.5    .035       0       0    .035       0     7.8    .035       0
#XS Ineff= 2 , 0
               0      20     7.8              20
Permanent Ineff=
       F       F
#Block Obstruct= 2 , 0
                             7.8
Bank Sta=0,7.8
XS Rating Curve= 0
Exp/Cntr=.3,.1

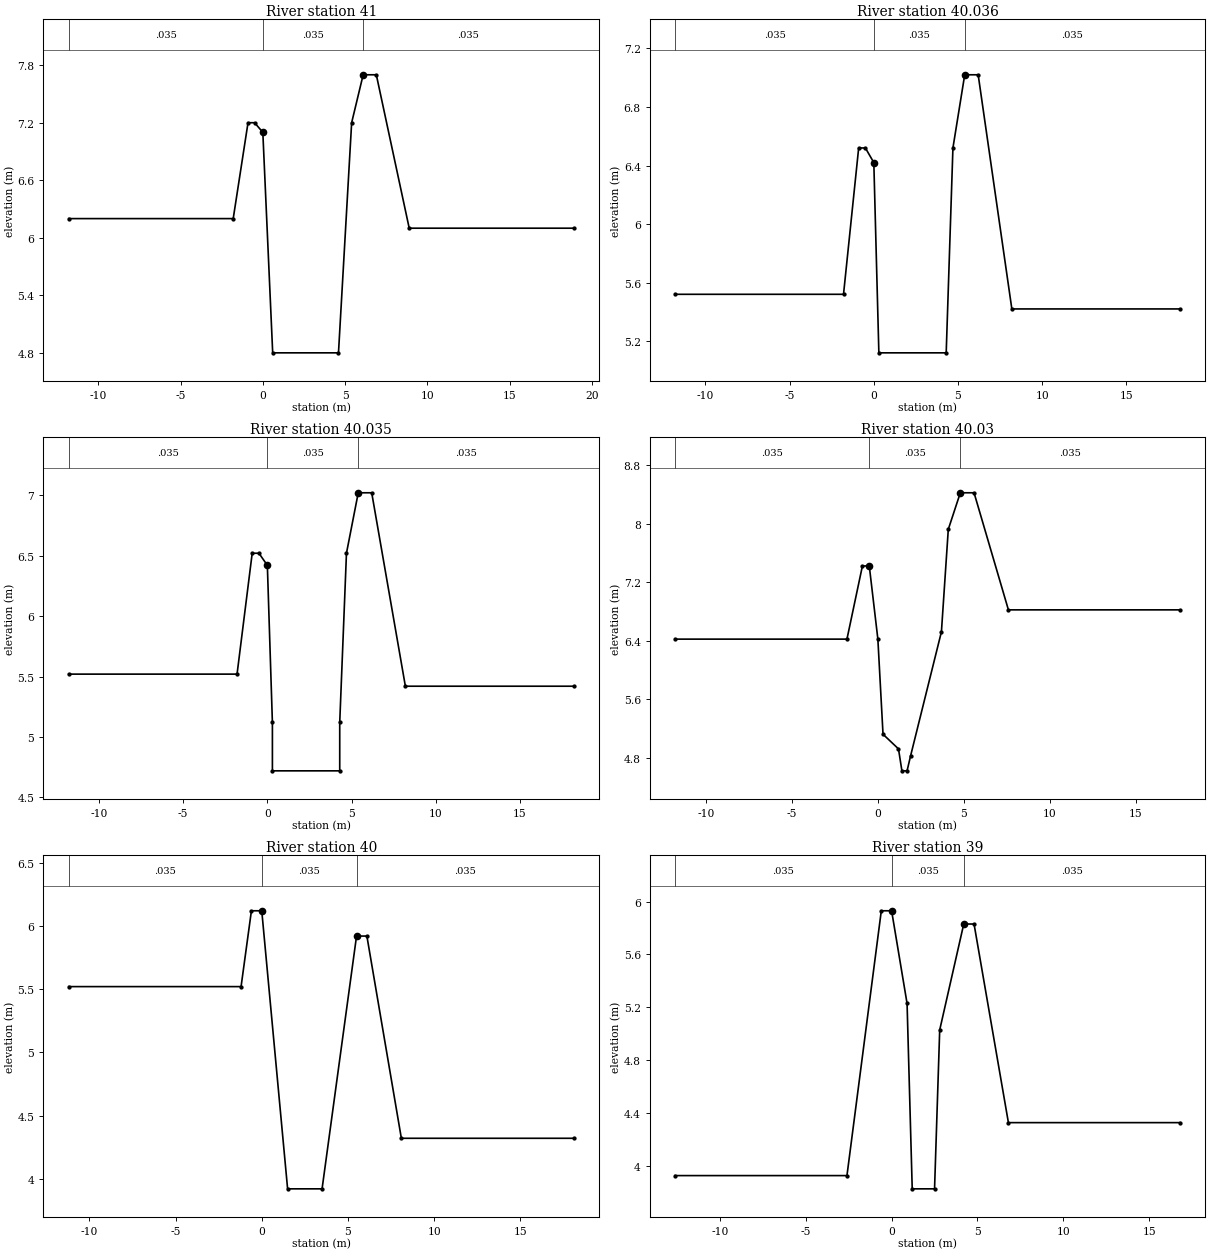
Type RM Length L Ch R = 1 ,41      ,14,14,14
#Sta/Elev= 12
   -11.8     6.2    -1.8     6.2     -.9     7.2     -.5     7.2       0     7.1
      .6     4.8     4.6     4.8     5.4     7.2     6.1     7.7     6.9     7.7
     8.9     6.1    18.9     6.1
#Mann= 3 , 0 , 0
   -11.8    .035       0       0    .035       0     6.1    .035       0
#XS Ineff= 2 , 0
               0      20     6.1              20
Permanent Ineff=
       F       F
#Block Obstruct= 2 , 0
                             6.1
Bank Sta=0,6.1
XS Rating Curve= 0
Exp/Cntr=.3,.1

Type RM Length L Ch R = 1 ,40.036  ,1,1,1
#Sta/Elev= 12
   -11.8    5.52    -1.8    5.52     -.9    6.52     -.5    6.52       0    6.42
      .3    5.12     4.3    5.12     4.7    6.52     5.4    7.02     6.2    7.02
     8.2    5.42    18.2    5.42
#Mann= 3 , 0 , 0
   -11.8    .035       0       0    .035       0     5.4    .035       0
#XS Ineff= 2 , 0
               0      20     5.4              20
Permanent Ineff=
       F       F
#Block Obstruct= 2 , 0
                             5.4
Bank Sta=0,5.4
XS Rating Curve= 0
Exp/Cntr=.3,.1

Type RM Length L Ch R = 1 ,40.035  ,5,5,5
#Sta/Elev= 14
   -11.8    5.52    -1.8    5.52     -.9    6.52     -.5    6.52       0    6.42
      .3    5.12      .3    4.72     4.3    4.72     4.3    5.12     4.7    6.52
     5.4    7.02     6.2    7.02     8.2    5.42    18.2    5.42
#Mann= 3 , 0 , 0
   -11.8    .035       0       0    .035       0     5.4    .035       0
#XS Ineff= 2 , 0
               0      20     5.4              20
Permanent Ineff=
       F       F
#Block Obstruct= 2 , 0
                             5.4
Bank Sta=0,5.4
XS Rating Curve= 0
Exp/Cntr=.3,.1

Type RM Length L Ch R = 1 ,40.03   ,30,30,30
#Sta/Elev= 16
   -11.8    6.42    -1.8    6.42     -.9    7.42     -.5    7.42       0    6.42
      .3    5.12     1.2    4.92     1.4    4.62     1.7    4.62     1.9    4.82
     3.7    6.52     4.1    7.92     4.8    8.42     5.6    8.42     7.6    6.82
    17.6    6.82
#Mann= 3 , 0 , 0
   -11.8    .035       0     -.5    .035       0     4.8    .035       0
#XS Ineff= 2 , 0
             -.5      20     4.8              20
Permanent Ineff=
       F       F
#Block Obstruct= 2 , 0
             -.5             4.8
Bank Sta=-.5,4.8
XS Rating Curve= 0
Exp/Cntr=.3,.1

Type RM Length L Ch R = 1 ,40      ,50,50,50
#Sta/Elev= 10
   -11.2    5.52    -1.2    5.52     -.6    6.12       0    6.12     1.5    3.92
     3.5    3.92     5.5    5.92     6.1    5.92     8.1    4.32    18.1    4.32
#Mann= 3 , 0 , 0
   -11.2    .035       0       0    .035       0     5.5    .035       0
#XS Ineff= 2 , 0
               0      20     5.5              20
Permanent Ineff=
       F       F
#Block Obstruct= 2 , 0
                             5.5
Bank Sta=0,5.5
XS Rating Curve= 0
Exp/Cntr=.3,.1

Type RM Length L Ch R = 1 ,39      ,7,7,7
#Sta/Elev= 12
   -12.6    3.93    -2.6    3.93     -.6    5.93       0    5.93      .9    5.23
     1.2    3.83     2.5    3.83     2.8    5.03     4.2    5.83     4.8    5.83
     6.8    4.33    16.8    4.33
#Mann= 3 , 0 , 0
   -12.6    .035       0       0    .035       0     4.2    .035       0
#XS Ineff= 2 , 0
               0      20     4.2              20
Permanent Ineff=
       F       F
#Block Obstruct= 2 , 0
                             4.2
Bank Sta=0,4.2
XS Rating Curve= 0
Exp/Cntr=.3,.1

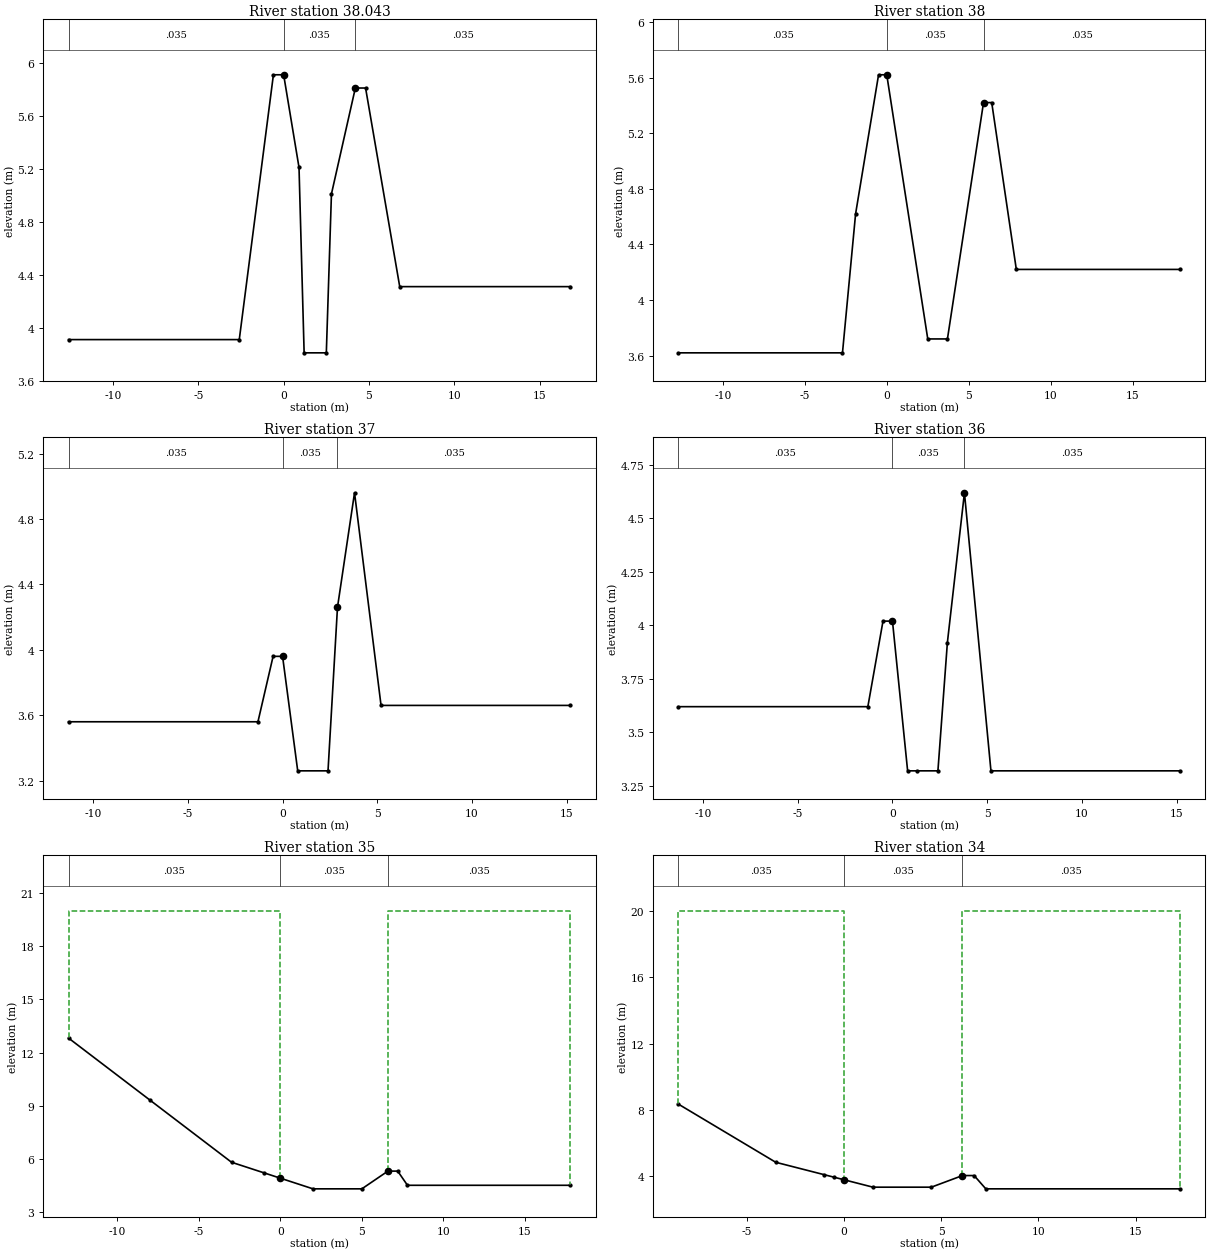
Type RM Length L Ch R = 1 ,38.043  ,43,43,43
#Sta/Elev= 12
   -12.6    3.91    -2.6    3.91     -.6    5.91       0    5.91      .9    5.21
     1.2    3.81     2.5    3.81     2.8    5.01     4.2    5.81     4.8    5.81
     6.8    4.31    16.8    4.31
#Mann= 3 , 0 , 0
   -12.6    .035       0       0    .035       0     4.2    .035       0
#XS Ineff= 2 , 0
               0      20     4.2              20
Permanent Ineff=
       F       F
#Block Obstruct= 2 , 0
                             4.2
Bank Sta=0,4.2
XS Rating Curve= 0
Exp/Cntr=.3,.1

Type RM Length L Ch R = 1 ,38      ,50,50,50
#Sta/Elev= 11
   -12.7    3.62    -2.7    3.62    -1.9    4.62     -.5    5.62       0    5.62
     2.5    3.72     3.7    3.72     5.9    5.42     6.4    5.42     7.9    4.22
    17.9    4.22
#Mann= 3 , 0 , 0
   -12.7    .035       0       0    .035       0     5.9    .035       0
#XS Ineff= 2 , 0
               0      20     5.9              20
Permanent Ineff=
       F       F
#Block Obstruct= 2 , 0
                             5.9
Bank Sta=0,5.9
XS Rating Curve= 0
Exp/Cntr=.3,.1

Type RM Length L Ch R = 1 ,37      ,50,50,50
#Sta/Elev= 10
   -11.3    3.56    -1.3    3.56     -.5    3.96       0    3.96      .8    3.26
     2.4    3.26     2.9    4.26     3.8    4.96     5.2    3.66    15.2    3.66
#Mann= 3 , 0 , 0
   -11.3    .035       0       0    .035       0     2.9    .035       0
#XS Ineff= 2 , 0
               0      20     2.9              20
Permanent Ineff=
       F       F
#Block Obstruct= 2 , 0
                             2.9
Bank Sta=0,2.9
XS Rating Curve= 0
Exp/Cntr=.3,.1

Type RM Length L Ch R = 1 ,36      ,50,50,50
#Sta/Elev= 11
   -11.3    3.62    -1.3    3.62     -.5    4.02       0    4.02      .8    3.32
     1.3    3.32     2.4    3.32     2.9    3.92     3.8    4.62     5.2    3.32
    15.2    3.32
#Mann= 3 , 0 , 0
   -11.3    .035       0       0    .035       0     3.8    .035       0
#XS Ineff= 2 , 0
               0      20     3.8              20
Permanent Ineff=
       F       F
#Block Obstruct= 2 , 0
                             3.8
Bank Sta=0,3.8
XS Rating Curve= 0
Exp/Cntr=.3,.1

Type RM Length L Ch R = 1 ,35      ,50,50,50
#Sta/Elev= 11
     -13   12.82      -8    9.32      -3    5.82      -1    5.22       0    4.92
       2    4.32       5    4.32     6.6    5.32     7.2    5.32     7.8    4.52
    17.8    4.52
#Mann= 3 , 0 , 0
     -13    .035       0       0    .035       0     6.6    .035       0
#XS Ineff= 2 , 0
               0      20     6.6              20
Permanent Ineff=
       F       F
#Block Obstruct= 2 , 0
                             6.6
Bank Sta=0,6.6
XS Rating Curve= 0
Exp/Cntr=.3,.1

Type RM Length L Ch R = 1 ,34      ,16,16,16
#Sta/Elev= 11
    -8.5    8.35    -3.5    4.85      -1     4.1     -.5    3.95       0     3.8
     1.5    3.35     4.5    3.35     6.1    4.05     6.7    4.05     7.3    3.25
    17.3    3.25
#Mann= 3 , 0 , 0
    -8.5    .035       0       0    .035       0     6.1    .035       0
#XS Ineff= 2 , 0
               0      20     6.1              20
Permanent Ineff=
       F       F
#Block Obstruct= 2 , 0
                             6.1
Bank Sta=0,6.1
XS Rating Curve= 0
Exp/Cntr=.3,.1

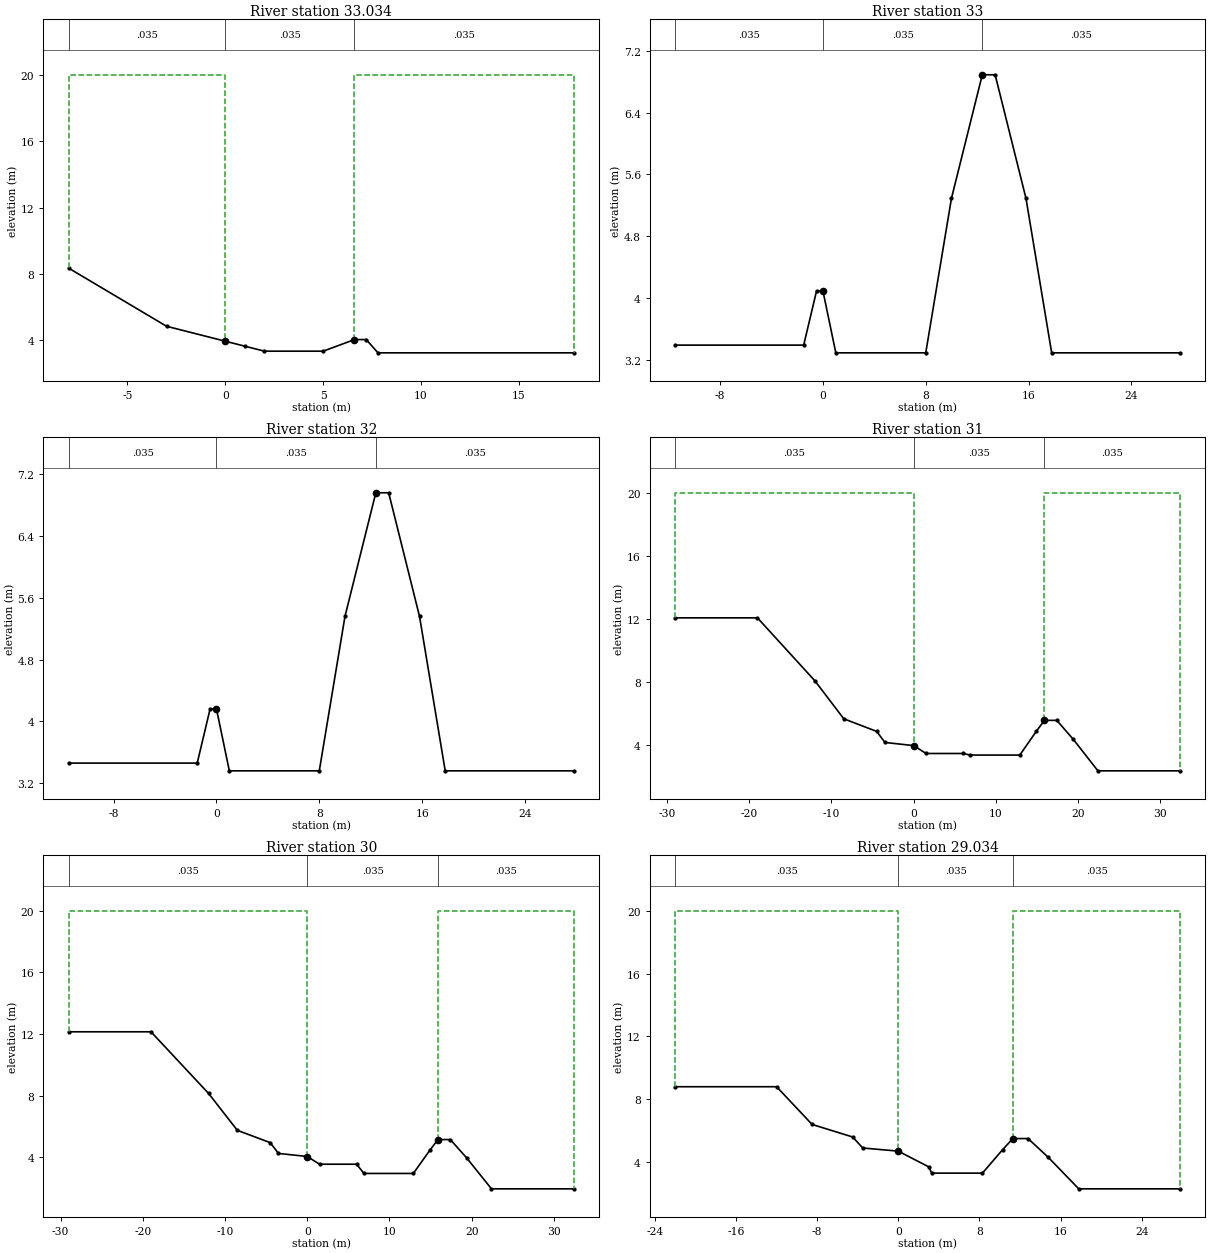
Type RM Length L Ch R = 1 ,33.034  ,34,34,34
#Sta/Elev= 10
      -8    8.35      -3    4.85       0    3.95       1    3.65       2    3.35
       5    3.35     6.6    4.05     7.2    4.05     7.8    3.25    17.8    3.25
#Mann= 3 , 0 , 0
      -8    .035       0       0    .035       0     6.6    .035       0
#XS Ineff= 2 , 0
               0      20     6.6              20
Permanent Ineff=
       F       F
#Block Obstruct= 2 , 0
                             6.6
Bank Sta=0,6.6
XS Rating Curve= 0
Exp/Cntr=.3,.1

Type RM Length L Ch R = 1 ,33      ,50,50,50
#Sta/Elev= 12
   -11.5    3.39    -1.5    3.39     -.5    4.09       0    4.09       1    3.29
       8    3.29      10    5.29    12.4    6.89    13.4    6.89    15.8    5.29
    17.8    3.29    27.8    3.29
#Mann= 3 , 0 , 0
   -11.5    .035       0       0    .035       0    12.4    .035       0
#XS Ineff= 2 , 0
               0      20    12.4              20
Permanent Ineff=
       F       F
#Block Obstruct= 2 , 0
                            12.4
Bank Sta=0,12.4
XS Rating Curve= 0
Exp/Cntr=.3,.1

Type RM Length L Ch R = 1 ,32      ,50,50,50
#Sta/Elev= 12
   -11.5    3.46    -1.5    3.46     -.5    4.16       0    4.16       1    3.36
       8    3.36      10    5.36    12.4    6.96    13.4    6.96    15.8    5.36
    17.8    3.36    27.8    3.36
#Mann= 3 , 0 , 0
   -11.5    .035       0       0    .035       0    12.4    .035       0
#XS Ineff= 2 , 0
               0      20    12.4              20
Permanent Ineff=
       F       F
#Block Obstruct= 2 , 0
                            12.4
Bank Sta=0,12.4
XS Rating Curve= 0
Exp/Cntr=.3,.1

Type RM Length L Ch R = 1 ,31      ,50,50,50
#Sta/Elev= 17
     -29   12.07     -19   12.07     -12    8.07    -8.5    5.67    -4.5    4.87
    -3.5    4.17       0    3.97     1.5    3.47       6    3.47     6.9    3.37
    12.9    3.37    14.9    4.87    15.9    5.57    17.4    5.57    19.4    4.37
    22.4    2.37    32.4    2.37
#Mann= 3 , 0 , 0
     -29    .035       0       0    .035       0    15.9    .035       0
#XS Ineff= 2 , 0
               0      20    15.9              20
Permanent Ineff=
       F       F
#Block Obstruct= 2 , 0
                            15.9
Bank Sta=0,15.9
XS Rating Curve= 0
Exp/Cntr=.3,.1

Type RM Length L Ch R = 1 ,30      ,16,16,16
#Sta/Elev= 17
     -29   12.14     -19   12.14     -12    8.14    -8.5    5.74    -4.5    4.94
    -3.5    4.24       0    4.04     1.5    3.54       6    3.54     6.9    2.94
    12.9    2.94    14.9    4.44    15.9    5.14    17.4    5.14    19.4    3.94
    22.4    1.94    32.4    1.94
#Mann= 3 , 0 , 0
     -29    .035       0       0    .035       0    15.9    .035       0
#XS Ineff= 2 , 0
               0      20    15.9              20
Permanent Ineff=
       F       F
#Block Obstruct= 2 , 0
                            15.9
Bank Sta=0,15.9
XS Rating Curve= 0
Exp/Cntr=.3,.1

Type RM Length L Ch R = 1 ,29.034  ,34,34,34
#Sta/Elev= 15
     -22     8.8     -12     8.8    -8.5     6.4    -4.5     5.6    -3.5     4.9
       0     4.7       3     3.7     3.3     3.3     8.3     3.3    10.3     4.8
    11.3     5.5    12.8     5.5    14.8     4.3    17.8     2.3    27.8     2.3
#Mann= 3 , 0 , 0
     -22    .035       0       0    .035       0    11.3    .035       0
#XS Ineff= 2 , 0
               0      20    11.3              20
Permanent Ineff=
       F       F
#Block Obstruct= 2 , 0
                            11.3
Bank Sta=0,11.3
XS Rating Curve= 0
Exp/Cntr=.3,.1