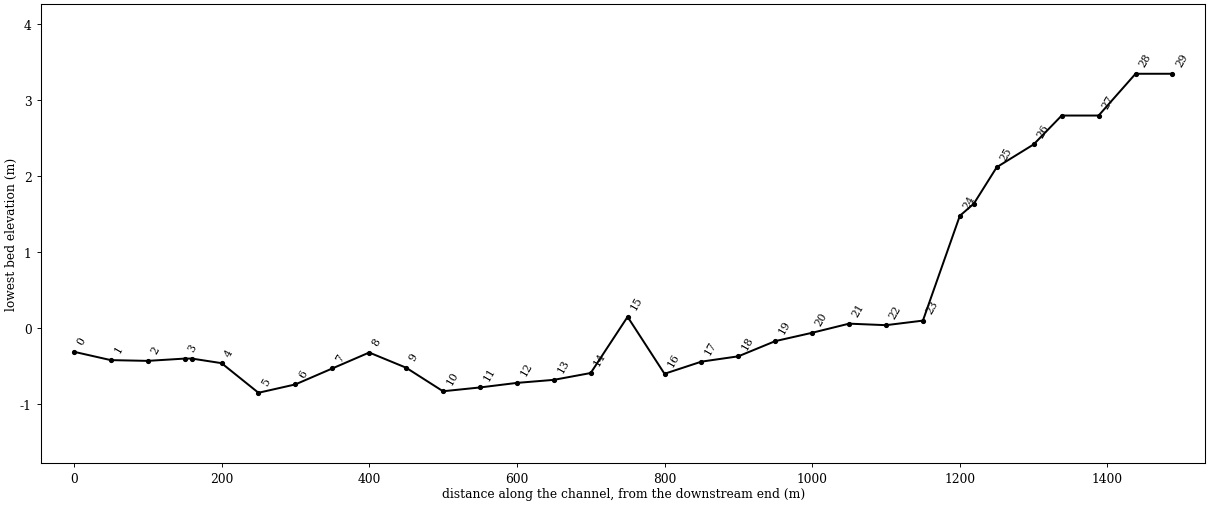
HEC-RAS study mhc.prj: myunhwa

--- mhc.g01 (geometry) --- (continued)

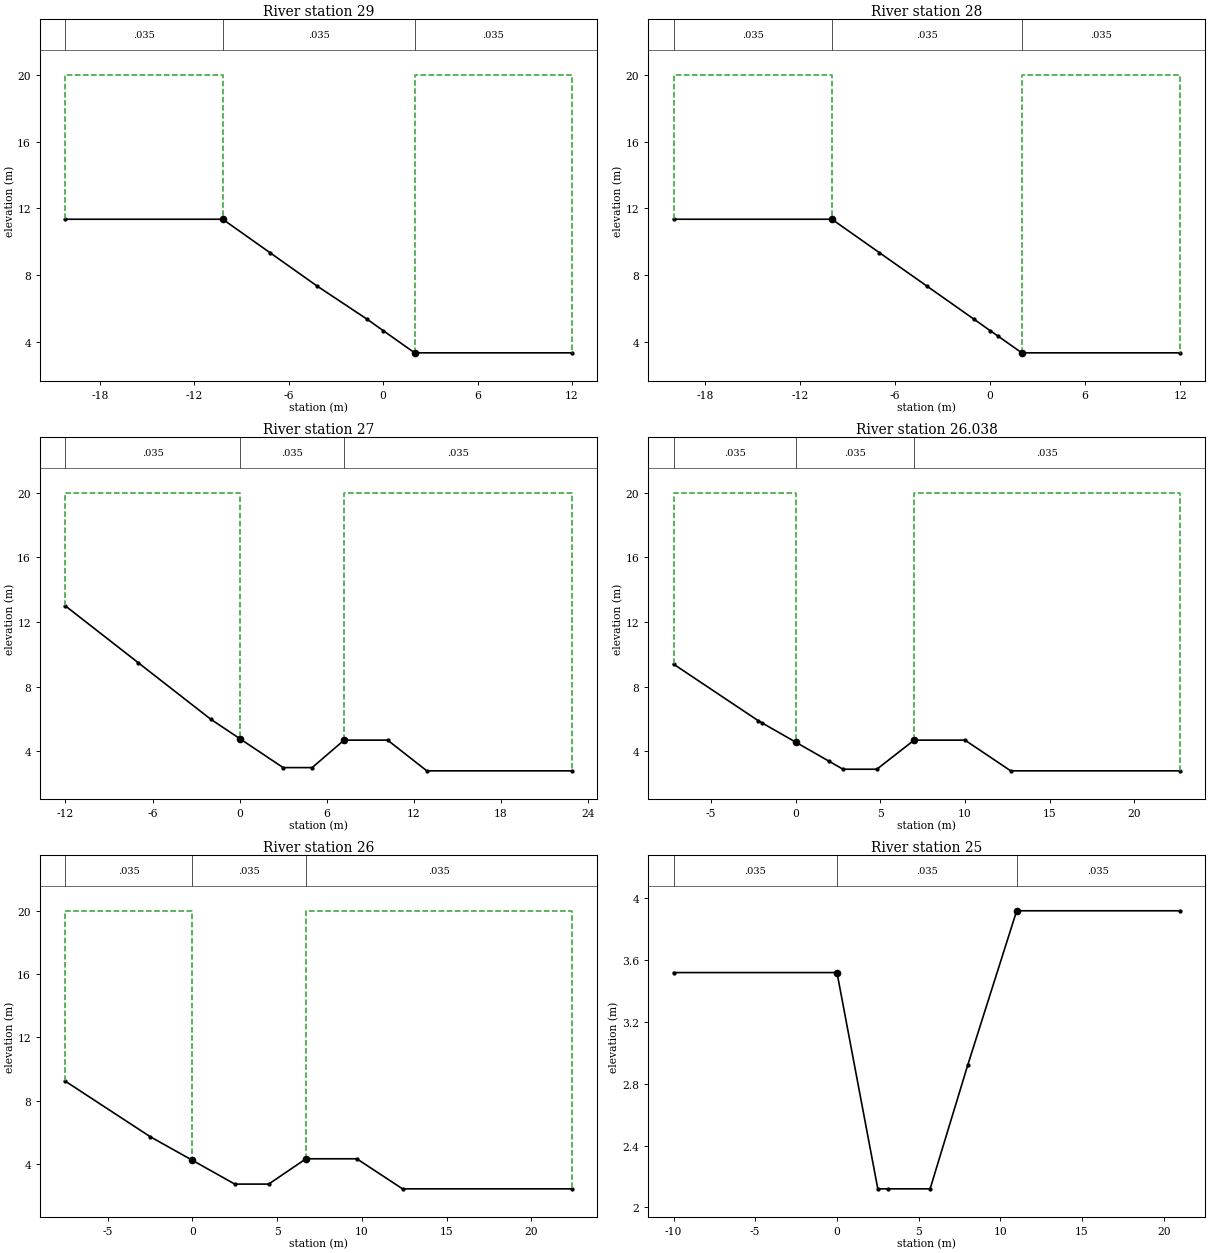
Type RM Length L Ch R = 1 ,29      ,50,50,50
#Sta/Elev= 8
   -20.2   11.35   -10.2   11.35    -7.2    9.35    -4.2    7.35      -1    5.35
       0    4.68       2    3.35      12    3.35
#Mann= 3 , 0 , 0
   -20.2    .035       0   -10.2    .035       0       2    .035       0
#XS Ineff= 2 , 0
           -10.2      20       2              20
Permanent Ineff=
       F       F
#Block Obstruct= 2 , 0
           -10.2               2
Bank Sta=-10.2,2
XS Rating Curve= 0
Exp/Cntr=.3,.1

Type RM Length L Ch R = 1 ,28      ,50,50,50
#Sta/Elev= 9
     -20   11.35     -10   11.35      -7    9.35      -4    7.35      -1    5.35
       0    4.68      .5    4.35       2    3.35      12    3.35
#Mann= 3 , 0 , 0
     -20    .035       0     -10    .035       0       2    .035       0
#XS Ineff= 2 , 0
             -10      20       2              20
Permanent Ineff=
       F       F
#Block Obstruct= 2 , 0
             -10               2
Bank Sta=-10,2
XS Rating Curve= 0
Exp/Cntr=.3,.1

Type RM Length L Ch R = 1 ,27      ,50,50,50
#Sta/Elev= 10
     -12      13      -7     9.5      -2       6       0     4.8       3       3
       5       3     7.2     4.7    10.2     4.7    12.9     2.8    22.9     2.8
#Mann= 3 , 0 , 0
     -12    .035       0       0    .035       0     7.2    .035       0
#XS Ineff= 2 , 0
               0      20     7.2              20
Permanent Ineff=
       F       F
#Block Obstruct= 2 , 0
                             7.2
Bank Sta=0,7.2
XS Rating Curve= 0
Exp/Cntr=.3,.1

Type RM Length L Ch R = 1 ,26.038  ,38,38,38
#Sta/Elev= 11
    -7.2     9.4    -2.2     5.9      -2    5.78       0    4.58       2    3.38
     2.8     2.9     4.8     2.9       7     4.7      10     4.7    12.7     2.8
    22.7     2.8
#Mann= 3 , 0 , 0
    -7.2    .035       0       0    .035       0       7    .035       0
#XS Ineff= 2 , 0
               0      20       7              20
Permanent Ineff=
       F       F
#Block Obstruct= 2 , 0
                               7
Bank Sta=0,7
XS Rating Curve= 0
Exp/Cntr=.3,.1

Type RM Length L Ch R = 1 ,26      ,50,50,50
#Sta/Elev= 9
    -7.5    9.22    -2.5    5.72       0    4.22     2.5    2.72     4.5    2.72
     6.7    4.32     9.7    4.32    12.4    2.42    22.4    2.42
#Mann= 3 , 0 , 0
    -7.5    .035       0       0    .035       0     6.7    .035       0
#XS Ineff= 2 , 0
               0      20     6.7              20
Permanent Ineff=
       F       F
#Block Obstruct= 2 , 0
                             6.7
Bank Sta=0,6.7
XS Rating Curve= 0
Exp/Cntr=.3,.1

Type RM Length L Ch R = 1 ,25      ,31,31,31
#Sta/Elev= 8
     -10    3.52       0    3.52     2.5    2.12     3.1    2.12     5.7    2.12
       8    2.92      11    3.92      21    3.92
#Mann= 3 , 0 , 0
     -10    .035       0       0    .035       0      11    .035       0
#XS Ineff= 2 , 0
               0      20      11              20
Permanent Ineff=
       F       F
#Block Obstruct= 2 , 0
                              11
Bank Sta=0,11
XS Rating Curve= 0
Exp/Cntr=.3,.1

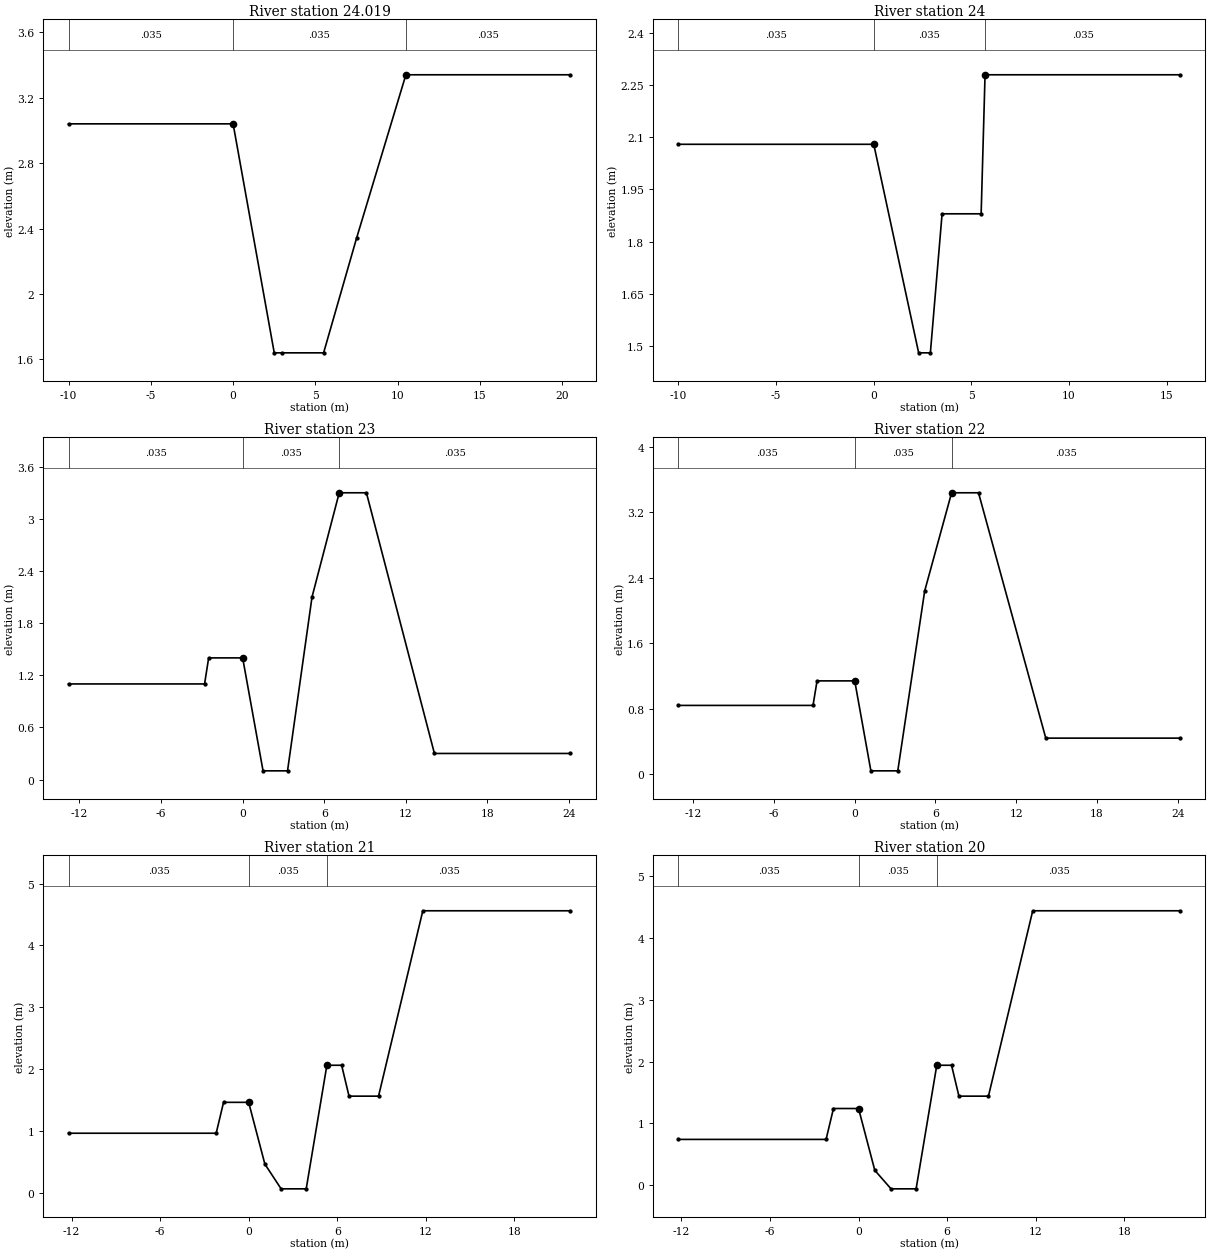
Type RM Length L Ch R = 1 ,24.019  ,19,19,19
#Sta/Elev= 8
     -10    3.04       0    3.04     2.5    1.64       3    1.64     5.5    1.64
     7.5    2.34    10.5    3.34    20.5    3.34
#Mann= 3 , 0 , 0
     -10    .035       0       0    .035       0    10.5    .035       0
#XS Ineff= 2 , 0
               0      20    10.5              20
Permanent Ineff=
       F       F
#Block Obstruct= 2 , 0
                            10.5
Bank Sta=0,10.5
XS Rating Curve= 0
Exp/Cntr=.3,.1

Type RM Length L Ch R = 1 ,24      ,50,50,50
#Sta/Elev= 8
     -10    2.08       0    2.08     2.3    1.48     2.9    1.48     3.5    1.88
     5.5    1.88     5.7    2.28    15.7    2.28
#Mann= 3 , 0 , 0
     -10    .035       0       0    .035       0     5.7    .035       0
#XS Ineff= 2 , 0
               0      20     5.7              20
Permanent Ineff=
       F       F
#Block Obstruct= 2 , 0
                             5.7
Bank Sta=0,5.7
XS Rating Curve= 0
Exp/Cntr=.3,.1

Type RM Length L Ch R = 1 ,23      ,50,50,50
#Sta/Elev= 11
   -12.8     1.1    -2.8     1.1    -2.5     1.4       0     1.4     1.5      .1
     3.3      .1     5.1     2.1     7.1     3.3     9.1     3.3    14.1      .3
    24.1      .3
#Mann= 3 , 0 , 0
   -12.8    .035       0       0    .035       0     7.1    .035       0
#XS Ineff= 2 , 0
               0      20     7.1              20
Permanent Ineff=
       F       F
#Block Obstruct= 2 , 0
                             7.1
Bank Sta=0,7.1
XS Rating Curve= 0
Exp/Cntr=.3,.1

Type RM Length L Ch R = 1 ,22      ,50,50,50
#Sta/Elev= 11
   -13.1     .84    -3.1     .84    -2.8    1.14       0    1.14     1.2     .04
     3.2     .04     5.2    2.24     7.2    3.44     9.2    3.44    14.2     .44
    24.2     .44
#Mann= 3 , 0 , 0
   -13.1    .035       0       0    .035       0     7.2    .035       0
#XS Ineff= 2 , 0
               0      20     7.2              20
Permanent Ineff=
       F       F
#Block Obstruct= 2 , 0
                             7.2
Bank Sta=0,7.2
XS Rating Curve= 0
Exp/Cntr=.3,.1

Type RM Length L Ch R = 1 ,21      ,50,50,50
#Sta/Elev= 13
   -12.2     .96    -2.2     .96    -1.7    1.46       0    1.46     1.1     .46
     2.2     .06     3.9     .06     5.3    2.06     6.3    2.06     6.8    1.56
     8.8    1.56    11.8    4.56    21.8    4.56
#Mann= 3 , 0 , 0
   -12.2    .035       0       0    .035       0     5.3    .035       0
#XS Ineff= 2 , 0
               0      20     5.3              20
Permanent Ineff=
       F       F
#Block Obstruct= 2 , 0
                             5.3
Bank Sta=0,5.3
XS Rating Curve= 0
Exp/Cntr=.3,.1

Type RM Length L Ch R = 1 ,20      ,50,50,50
#Sta/Elev= 13
   -12.2     .74    -2.2     .74    -1.7    1.24       0    1.24     1.1     .24
     2.2    -.06     3.9    -.06     5.3    1.94     6.3    1.94     6.8    1.44
     8.8    1.44    11.8    4.44    21.8    4.44
#Mann= 3 , 0 , 0
   -12.2    .035       0       0    .035       0     5.3    .035       0
#XS Ineff= 2 , 0
               0      20     5.3              20
Permanent Ineff=
       F       F
#Block Obstruct= 2 , 0
                             5.3
Bank Sta=0,5.3
XS Rating Curve= 0
Exp/Cntr=.3,.1

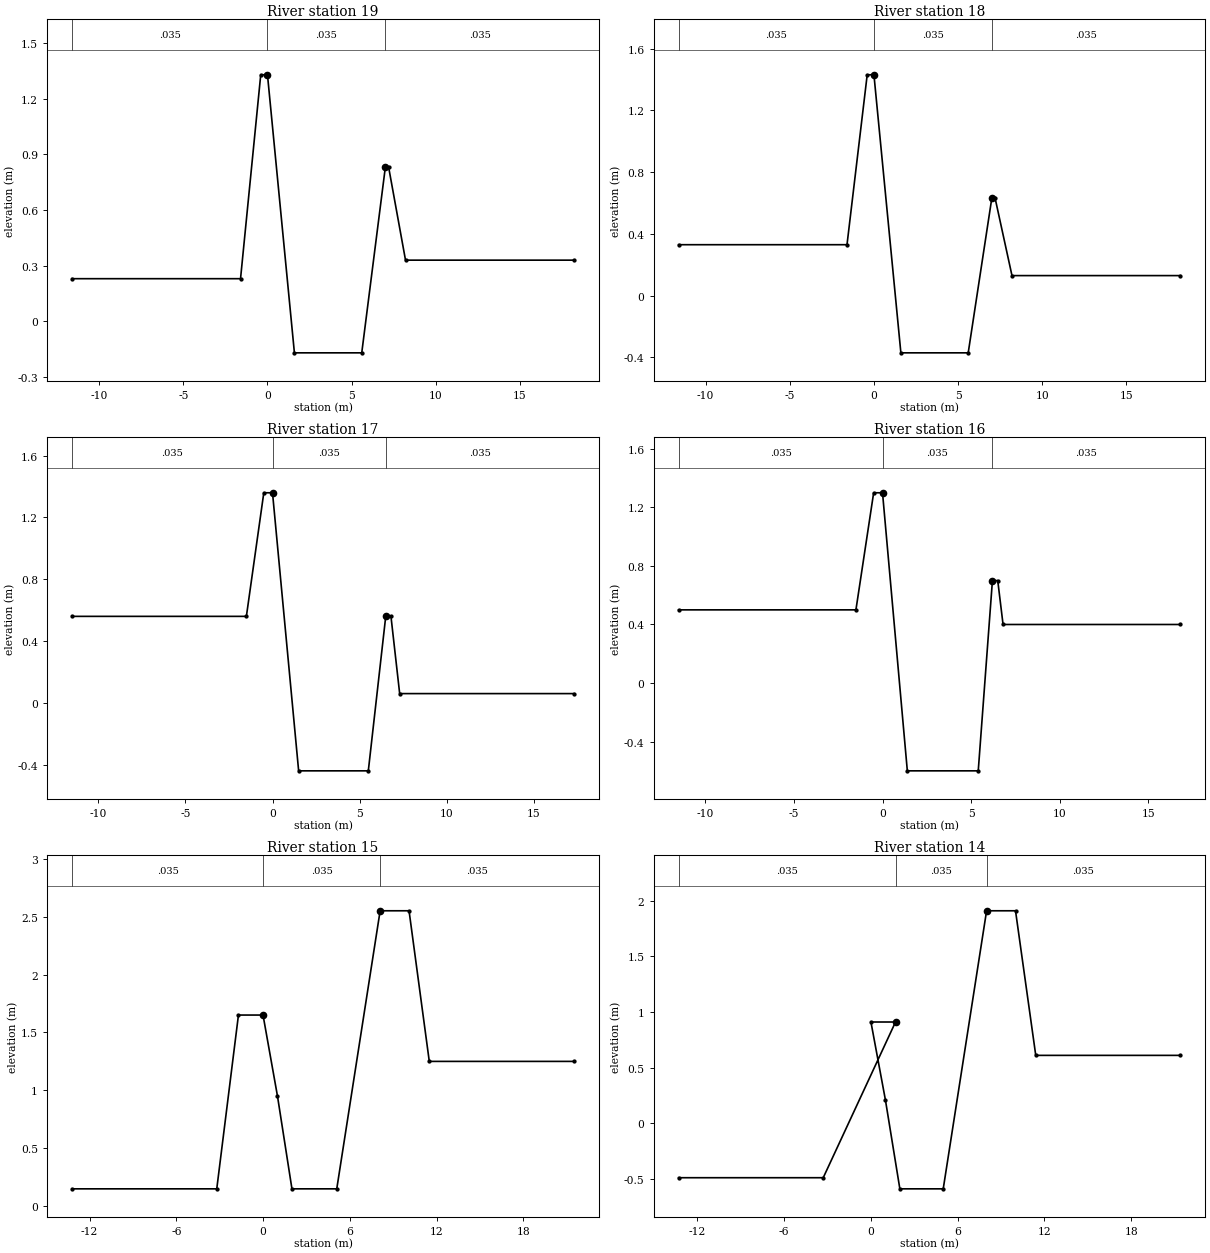
Type RM Length L Ch R = 1 ,19      ,50,50,50
#Sta/Elev= 10
   -11.6     .23    -1.6     .23     -.4    1.33       0    1.33     1.6    -.17
     5.6    -.17       7     .83     7.2     .83     8.2     .33    18.2     .33
#Mann= 3 , 0 , 0
   -11.6    .035       0       0    .035       0       7    .035       0
#XS Ineff= 2 , 0
               0      20       7              20
Permanent Ineff=
       F       F
#Block Obstruct= 2 , 0
                               7
Bank Sta=0,7
XS Rating Curve= 0
Exp/Cntr=.3,.1

Type RM Length L Ch R = 1 ,18      ,50,50,50
#Sta/Elev= 10
   -11.6     .33    -1.6     .33     -.4    1.43       0    1.43     1.6    -.37
     5.6    -.37       7     .63     7.2     .63     8.2     .13    18.2     .13
#Mann= 3 , 0 , 0
   -11.6    .035       0       0    .035       0       7    .035       0
#XS Ineff= 2 , 0
               0      20       7              20
Permanent Ineff=
       F       F
#Block Obstruct= 2 , 0
                               7
Bank Sta=0,7
XS Rating Curve= 0
Exp/Cntr=.3,.1

Type RM Length L Ch R = 1 ,17      ,50,50,50
#Sta/Elev= 10
   -11.5     .56    -1.5     .56     -.5    1.36       0    1.36     1.5    -.44
     5.5    -.44     6.5     .56     6.8     .56     7.3     .06    17.3     .06
#Mann= 3 , 0 , 0
   -11.5    .035       0       0    .035       0     6.5    .035       0
#XS Ineff= 2 , 0
               0      20     6.5              20
Permanent Ineff=
       F       F
#Block Obstruct= 2 , 0
                             6.5
Bank Sta=0,6.5
XS Rating Curve= 0
Exp/Cntr=.3,.1

Type RM Length L Ch R = 1 ,16      ,50,50,50
#Sta/Elev= 10
   -11.5      .5    -1.5      .5     -.5     1.3       0     1.3     1.4     -.6
     5.4     -.6     6.2      .7     6.5      .7     6.8      .4    16.8      .4
#Mann= 3 , 0 , 0
   -11.5    .035       0       0    .035       0     6.2    .035       0
#XS Ineff= 2 , 0
               0      20     6.2              20
Permanent Ineff=
       F       F
#Block Obstruct= 2 , 0
                             6.2
Bank Sta=0,6.2
XS Rating Curve= 0
Exp/Cntr=.3,.1

Type RM Length L Ch R = 1 ,15      ,50,50,50
#Sta/Elev= 11
   -13.2     .15    -3.2     .15    -1.7    1.65       0    1.65       1     .95
       2     .15     5.1     .15     8.1    2.55    10.1    2.55    11.5    1.25
    21.5    1.25
#Mann= 3 , 0 , 0
   -13.2    .035       0       0    .035       0     8.1    .035       0
#XS Ineff= 2 , 0
               0      20     8.1              20
Permanent Ineff=
       F       F
#Block Obstruct= 2 , 0
                             8.1
Bank Sta=0,8.1
XS Rating Curve= 0
Exp/Cntr=.3,.1

Type RM Length L Ch R = 1 ,14      ,50,50,50
#Sta/Elev= 11
   -13.3    -.49    -3.3    -.49     1.7     .91       0     .91       1     .21
       2    -.59       5    -.59       8    1.91      10    1.91    11.4     .61
    21.4     .61
#Mann= 3 , 0 , 0
   -13.3    .035       0     1.7    .035       0       8    .035       0
#XS Ineff= 2 , 0
             1.7      20       8              20
Permanent Ineff=
       F       F
#Block Obstruct= 2 , 0
                               8
Bank Sta=1.7,8
XS Rating Curve= 0
Exp/Cntr=.3,.1

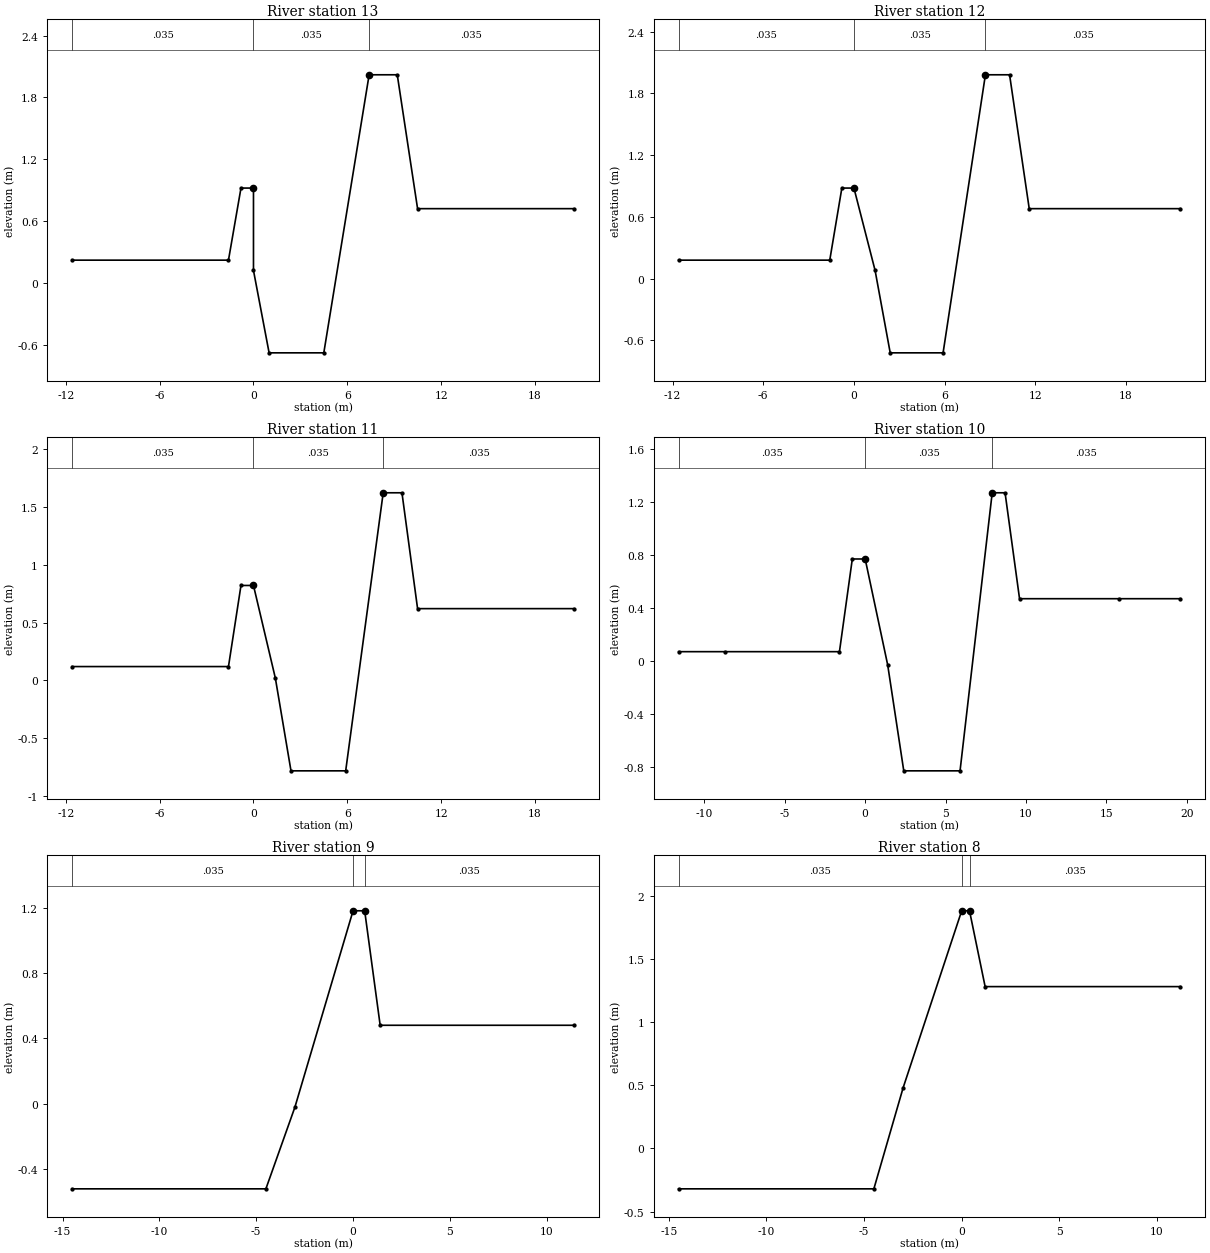
Type RM Length L Ch R = 1 ,13      ,50,50,50
#Sta/Elev= 11
   -11.6     .22    -1.6     .22     -.8     .92       0     .92       0     .12
       1    -.68     4.5    -.68     7.4    2.02     9.2    2.02    10.5     .72
    20.5     .72
#Mann= 3 , 0 , 0
   -11.6    .035       0       0    .035       0     7.4    .035       0
#XS Ineff= 2 , 0
               0      20     7.4              20
Permanent Ineff=
       F       F
#Block Obstruct= 2 , 0
                             7.4
Bank Sta=0,7.4
XS Rating Curve= 0
Exp/Cntr=.3,.1

Type RM Length L Ch R = 1 ,12      ,50,50,50
#Sta/Elev= 11
   -11.6     .18    -1.6     .18     -.8     .88       0     .88     1.4     .08
     2.4    -.72     5.9    -.72     8.7    1.98    10.3    1.98    11.6     .68
    21.6     .68
#Mann= 3 , 0 , 0
   -11.6    .035       0       0    .035       0     8.7    .035       0
#XS Ineff= 2 , 0
               0      20     8.7              20
Permanent Ineff=
       F       F
#Block Obstruct= 2 , 0
                             8.7
Bank Sta=0,8.7
XS Rating Curve= 0
Exp/Cntr=.3,.1

Type RM Length L Ch R = 1 ,11      ,50,50,50
#Sta/Elev= 11
   -11.6     .12    -1.6     .12     -.8     .82       0     .82     1.4     .02
     2.4    -.78     5.9    -.78     8.3    1.62     9.5    1.62    10.5     .62
    20.5     .62
#Mann= 3 , 0 , 0
   -11.6    .035       0       0    .035       0     8.3    .035       0
#XS Ineff= 2 , 0
               0      20     8.3              20
Permanent Ineff=
       F       F
#Block Obstruct= 2 , 0
                             8.3
Bank Sta=0,8.3
XS Rating Curve= 0
Exp/Cntr=.3,.1

Type RM Length L Ch R = 1 ,10      ,50,50,50
#Sta/Elev= 13
   -11.6     .07    -8.7     .07    -1.6     .07     -.8     .77       0     .77
     1.4    -.03     2.4    -.83     5.9    -.83     7.9    1.27     8.7    1.27
     9.6     .47    15.8     .47    19.6     .47
#Mann= 3 , 0 , 0
   -11.6    .035       0       0    .035       0     7.9    .035       0
#XS Ineff= 2 , 0
               0      20     7.9              20
Permanent Ineff=
       F       F
#Block Obstruct= 2 , 0
                             7.9
Bank Sta=0,7.9
XS Rating Curve= 0
Exp/Cntr=.3,.1

Type RM Length L Ch R = 1 ,9       ,50,50,50
#Sta/Elev= 7
   -14.5    -.52    -4.5    -.52      -3    -.02       0    1.18      .6    1.18
     1.4     .48    11.4     .48
#Mann= 3 , 0 , 0
   -14.5    .035       0       0    .035       0      .6    .035       0
#XS Ineff= 2 , 0
               0      20      .6              20
Permanent Ineff=
       F       F
#Block Obstruct= 2 , 0
                              .6
Bank Sta=0,.6
XS Rating Curve= 0
Exp/Cntr=.3,.1

Type RM Length L Ch R = 1 ,8       ,50,50,50
#Sta/Elev= 7
   -14.5    -.32    -4.5    -.32      -3     .48       0    1.88      .4    1.88
     1.2    1.28    11.2    1.28
#Mann= 3 , 0 , 0
   -14.5    .035       0       0    .035       0      .4    .035       0
#XS Ineff= 2 , 0
               0      20      .4              20
Permanent Ineff=
       F       F
#Block Obstruct= 2 , 0
                              .4
Bank Sta=0,.4
XS Rating Curve= 0
Exp/Cntr=.3,.1

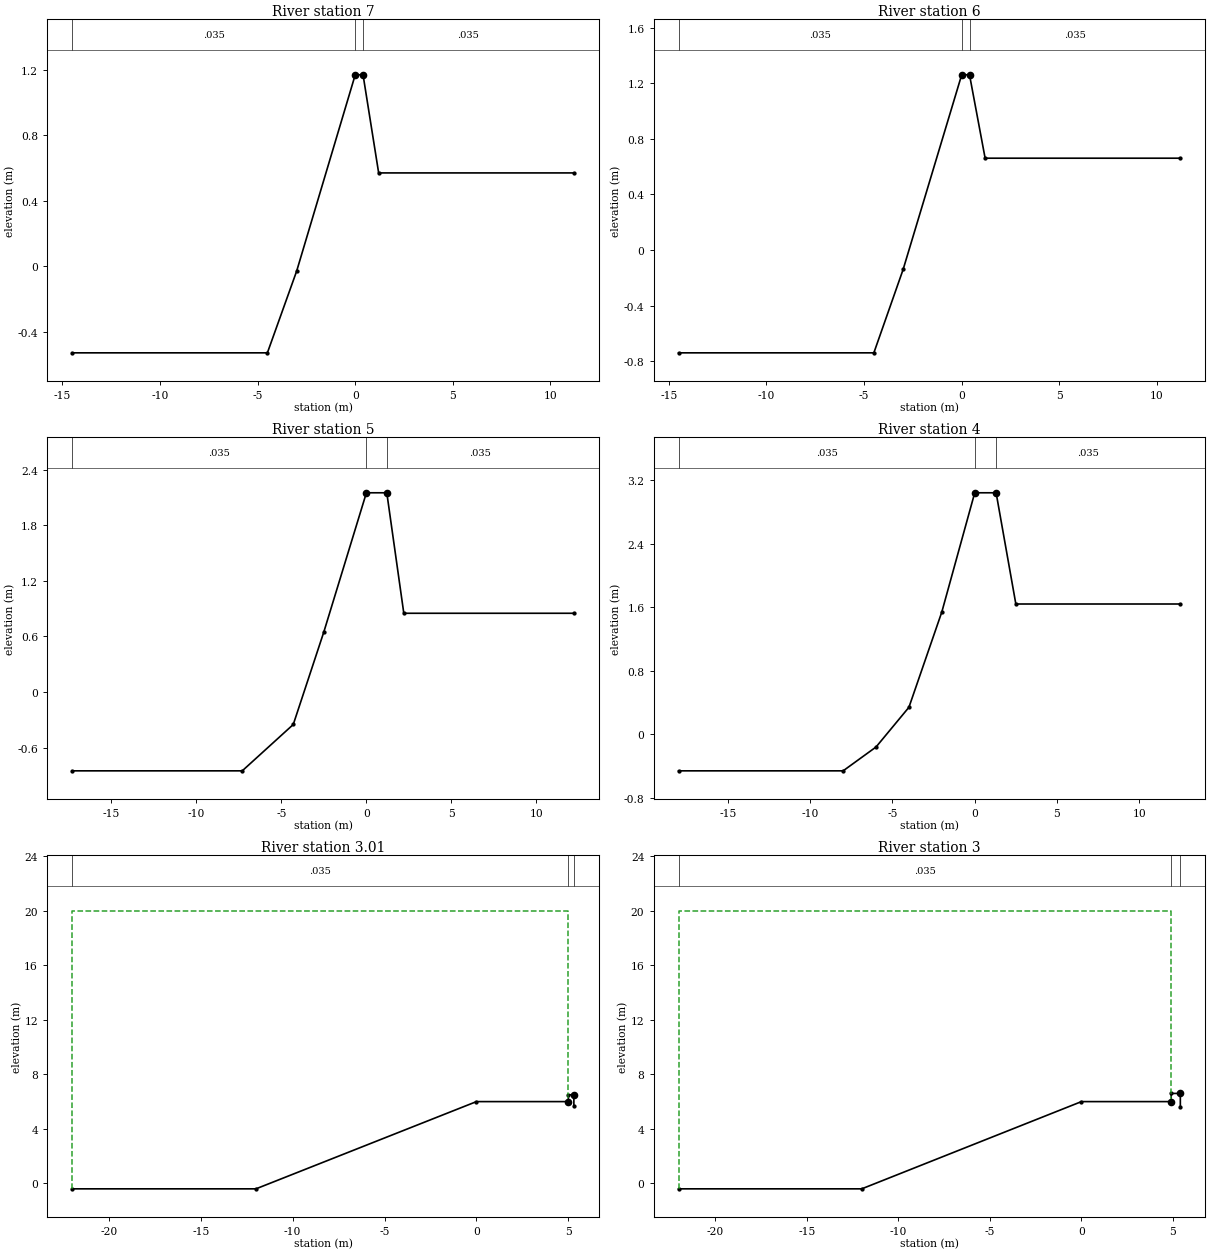
Type RM Length L Ch R = 1 ,7       ,50,50,50
#Sta/Elev= 7
   -14.5    -.53    -4.5    -.53      -3    -.03       0    1.17      .4    1.17
     1.2     .57    11.2     .57
#Mann= 3 , 0 , 0
   -14.5    .035       0       0    .035       0      .4    .035       0
#XS Ineff= 2 , 0
               0      20      .4              20
Permanent Ineff=
       F       F
#Block Obstruct= 2 , 0
                              .4
Bank Sta=0,.4
XS Rating Curve= 0
Exp/Cntr=.3,.1

Type RM Length L Ch R = 1 ,6       ,50,50,50
#Sta/Elev= 7
   -14.5    -.74    -4.5    -.74      -3    -.14       0    1.26      .4    1.26
     1.2     .66    11.2     .66
#Mann= 3 , 0 , 0
   -14.5    .035       0       0    .035       0      .4    .035       0
#XS Ineff= 2 , 0
               0      20      .4              20
Permanent Ineff=
       F       F
#Block Obstruct= 2 , 0
                              .4
Bank Sta=0,.4
XS Rating Curve= 0
Exp/Cntr=.3,.1

Type RM Length L Ch R = 1 ,5       ,50,50,50
#Sta/Elev= 8
   -17.3    -.85    -7.3    -.85    -4.3    -.35    -2.5     .65       0    2.15
     1.2    2.15     2.2     .85    12.2     .85
#Mann= 3 , 0 , 0
   -17.3    .035       0       0    .035       0     1.2    .035       0
#XS Ineff= 2 , 0
               0      20     1.2              20
Permanent Ineff=
       F       F
#Block Obstruct= 2 , 0
                             1.2
Bank Sta=0,1.2
XS Rating Curve= 0
Exp/Cntr=.3,.1

Type RM Length L Ch R = 1 ,4       ,40,40,40
#Sta/Elev= 9
     -18    -.46      -8    -.46      -6    -.16      -4     .34      -2    1.54
       0    3.04     1.3    3.04     2.5    1.64    12.5    1.64
#Mann= 3 , 0 , 0
     -18    .035       0       0    .035       0     1.3    .035       0
#XS Ineff= 2 , 0
               0      20     1.3              20
Permanent Ineff=
       F       F
#Block Obstruct= 2 , 0
                             1.3
Bank Sta=0,1.3
XS Rating Curve= 0
Exp/Cntr=.3,.1

Type RM Length L Ch R = 1 ,3.01    ,10,10,10
#Sta/Elev= 7
     -22     -.4     -12     -.4       0       6       5       6       5     6.5
     5.3     6.5     5.3     5.7
#Mann= 3 , 0 , 0
     -22    .035       0       5    .035       0     5.3    .035       0
#XS Ineff= 2 , 0
               5      20     5.3              20
Permanent Ineff=
       F       F
#Block Obstruct= 2 , 0
               5             5.3
Bank Sta=5,5.3
XS Rating Curve= 0
Exp/Cntr=.3,.1

Type RM Length L Ch R = 1 ,3       ,50,50,50
#Sta/Elev= 7
     -22     -.4     -12     -.4       0       6     4.9       6     4.9     6.6
     5.4     6.6     5.4     5.6
#Mann= 3 , 0 , 0
     -22    .035       0     4.9    .035       0     5.4    .035       0
#XS Ineff= 2 , 0
             4.9      20     5.4              20
Permanent Ineff=
       F       F
#Block Obstruct= 2 , 0
             4.9             5.4
Bank Sta=4.9,5.4
XS Rating Curve= 0
Exp/Cntr=.3,.1

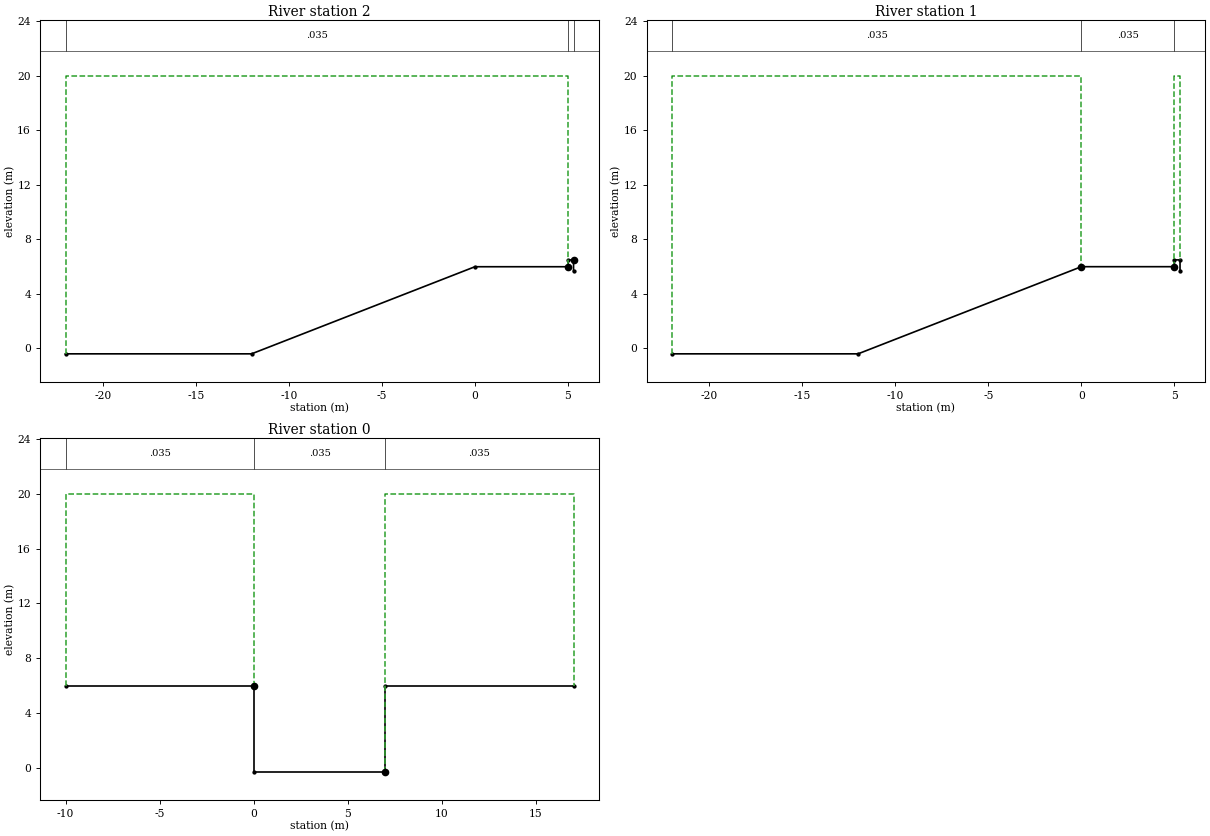
Type RM Length L Ch R = 1 ,2       ,50,50,50
#Sta/Elev= 7
     -22    -.43     -12    -.43       0    5.97       5    5.97       5    6.47
     5.3    6.47     5.3    5.67
#Mann= 3 , 0 , 0
     -22    .035       0       5    .035       0     5.3    .035       0
#XS Ineff= 2 , 0
               5      20     5.3              20
Permanent Ineff=
       F       F
#Block Obstruct= 2 , 0
               5             5.3
Bank Sta=5,5.3
XS Rating Curve= 0
Exp/Cntr=.3,.1

Type RM Length L Ch R = 1 ,1       ,50,50,50
#Sta/Elev= 7
     -22    -.42     -12    -.42       0    5.98       5    5.98       5    6.48
     5.3    6.48     5.3    5.68
#Mann= 3 , 0 , 0
     -22    .035       0       0    .035       0       5    .035       0
#XS Ineff= 2 , 0
               0      20       5              20
Permanent Ineff=
       F       F
#Block Obstruct= 2 , 0
                               5
Bank Sta=0,5
XS Rating Curve= 0
Exp/Cntr=.3,.1

Type RM Length L Ch R = 1 ,0       ,0,0,0
#Sta/Elev= 6
     -10    5.99       0    5.99       0    -.31       7    -.31       7    5.99
      17    5.99
#Mann= 3 , 0 , 0
     -10    .035       0       0    .035       0       7    .035       0
#XS Ineff= 2 , 0
               0      20       7              20
Permanent Ineff=
       F       F
#Block Obstruct= 2 , 0
                               7
Bank Sta=0,7
XS Rating Curve= 0
Exp/Cntr=.3,.1

Chan Stop Cuts=-1