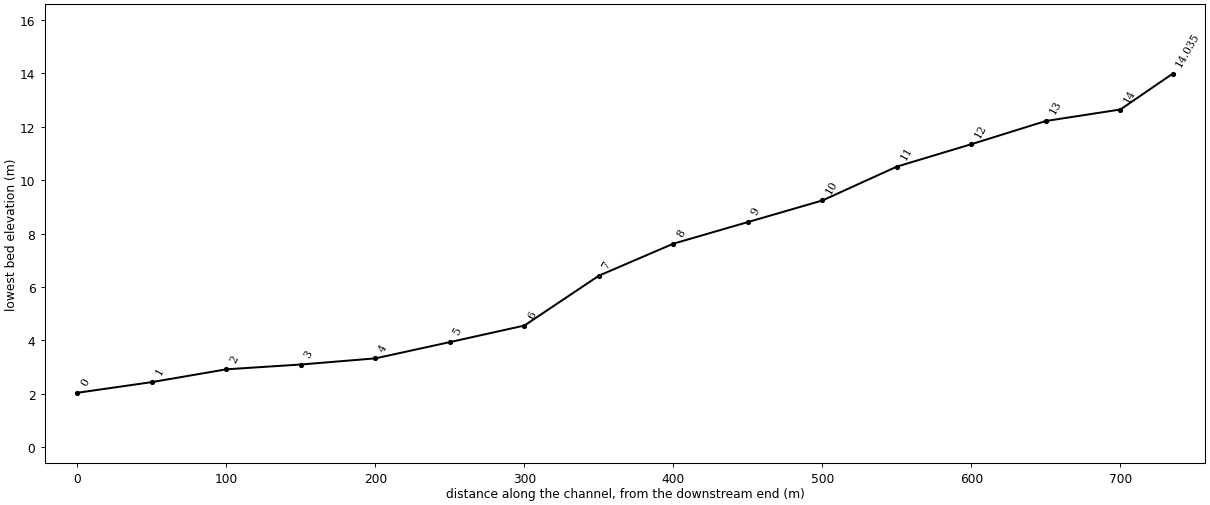
--- jkc.prj (project) ---

Proj Title=julkul
Current Plan=p01
Default Exp/Contr=.3,.1
SI Units
Geom File=g01
Flow File=f01
Plan File=p01
Y Axis Title=Elevation
X Axis Title(PF)=Main Channel Distance
X Axis Title(XS)=Station
BEGIN DESCRIPTION:
           BACK WATER COMPUTATION
      APPLICATION OF HEC-2 BY Samju Construction Engineering
      gealgol-ch: 10,20,30,50,80 yr
END DESCRIPTION:
DSS Export Rating Curves= 0
DSS Export Rating Curve Sorted= 0
DSS Export Volume Flow Curves= 0
DXF OffsetX= 0
DXF OffsetY= 0
DXF ScaleX= 1
DXF ScaleY= 10

--- jkc.p01 (plan) ---

Plan Title=Imported Plan 01
Version=Version 3.0.1  Mar 2001
Short Identifier=Imported Pla
Geom File=g01
Flow File=f01
Subcritical Flow
K Sum by GR= 0
Std Step Tol= 0.003
Critical Tol= 0.003
Num of Std Step Trials= 20
Max Error Tol= 0.1
Flow Tol Ratio= 0.001
Split Flow NTrial= 30
Split Flow Tol= 0.02
Split Flow Ratio= 0.02
Log Output Level= 0
Friction Slope Method= 1
Unsteady Friction Slope Method= 2
Parabolic Critical Depth
Global Vel Dist= 0 , 0 , 0
Global Log Level= 0
CheckData=True
Encroach Param=-1 ,0,0, 0
Computation Interval=1HOUR
Output Interval=1HOUR
Run HTab= 0
Run UNet= 0
Run PostProcess= 0
UNET Theta= 1
UNET ZTol= 0.02
UNET ZSATol= 0.1
UNET MxIter= 20
UNET MaxInSteps= 20
UNET DtIC= 0
UNET DtMin= 0
UNET MaxCRTS= 20
UNET WFStab= 2
UNET SFStab= 1
UNET WFX= 1
UNET SFX= 1
UNET Convert EG Bridges=-1
UNET Use Existing IB Tables=-1
Instantaneous Interval=1HOUR
Write IC File= 0
Write Velocity= 0
Write Detailed= 0

--- jkc.f01 (steady flow) ---

Flow Title=Imported Flow 01
Version=Version 3.0.1  Mar 2001
Number of Profiles= 5
Profile Names=10yr,20yr,30yr,50yr,80yr
River Rch & RM=RIVER-1,Reach-1         ,14.035
   17.68   19.49   20.54   21.87   23.09
River Rch & RM=JULGOL,JULGOL          ,14.035
   17.68   19.49   20.54   21.87   23.09
Boundary for River Rch & Prof#=JULGOL,JULGOL          , 1
Up Type= 0
Dn Type= 3
Dn Slope=.017
Boundary for River Rch & Prof#=JULGOL,JULGOL          , 2
Up Type= 0
Dn Type= 3
Dn Slope=.017
Boundary for River Rch & Prof#=JULGOL,JULGOL          , 3
Up Type= 0
Dn Type= 3
Dn Slope=.017
Boundary for River Rch & Prof#=JULGOL,JULGOL          , 4
Up Type= 0
Dn Type= 3
Dn Slope=.017
Boundary for River Rch & Prof#=JULGOL,JULGOL          , 5
Up Type= 0
Dn Type= 3
Dn Slope=.017
DSS Import GetInterval= 0
DSS Import GetPeak= 0
DSS Import FillOption= 0

--- jkc.g01 (geometry) ---

Geom Title=Imported Geom 01
Version=Version 3.0.1  Mar 2001

River Reach=JULGOL          ,JULGOL
Reach XY= 2
              .5             .95              .5             .05

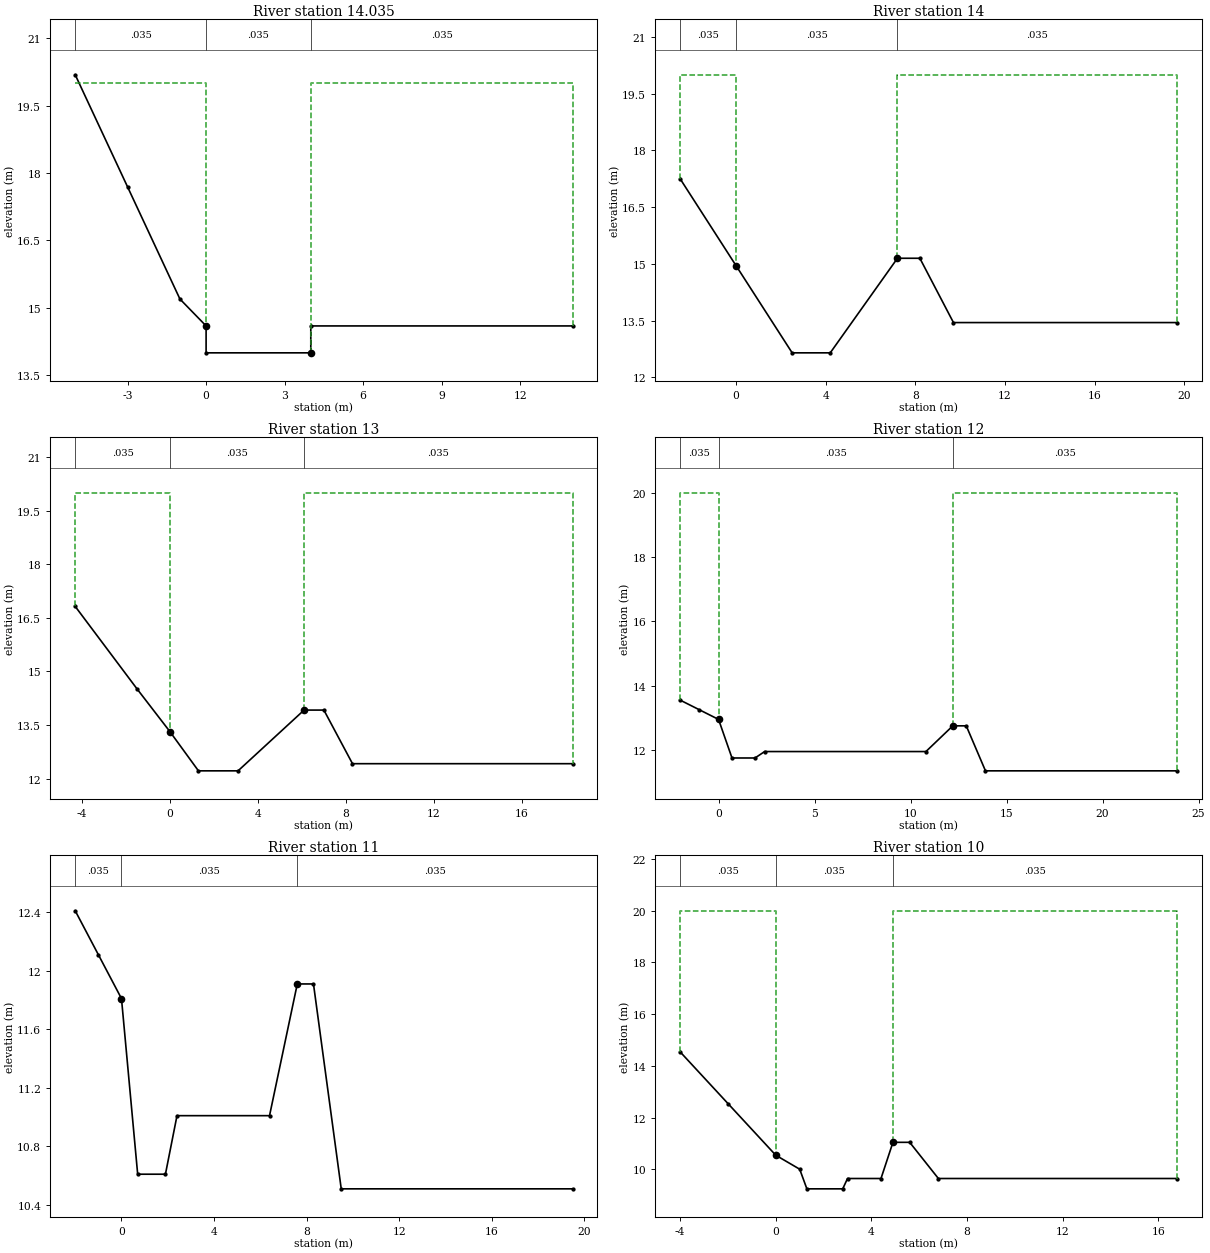
Type RM Length L Ch R = 1 ,14.035  ,35,35,35
#Sta/Elev= 8
      -5   20.19      -3   17.69      -1   15.19       0   14.59       0   13.99
       4   13.99       4   14.59      14   14.59
#Mann= 3 , 0 , 0
      -5    .035       0       0    .035       0       4    .035       0
#XS Ineff= 2 , 0
               0      20       4              20
Permanent Ineff=
       F       F
#Block Obstruct= 2 , 0
                               4
Bank Sta=0,4
XS Rating Curve= 0
Exp/Cntr=.3,.1

Type RM Length L Ch R = 1 ,14      ,50,50,50
#Sta/Elev= 8
    -2.5   17.25       0   14.95     2.5   12.65     4.2   12.65     7.2   15.15
     8.2   15.15     9.7   13.45    19.7   13.45
#Mann= 3 , 0 , 0
    -2.5    .035       0       0    .035       0     7.2    .035       0
#XS Ineff= 2 , 0
               0      20     7.2              20
Permanent Ineff=
       F       F
#Block Obstruct= 2 , 0
                             7.2
Bank Sta=0,7.2
XS Rating Curve= 0
Exp/Cntr=.3,.1

Type RM Length L Ch R = 1 ,13      ,50,50,50
#Sta/Elev= 9
    -4.3   16.82    -1.5   14.52       0   13.32     1.3   12.22     3.1   12.22
     6.1   13.92       7   13.92     8.3   12.42    18.3   12.42
#Mann= 3 , 0 , 0
    -4.3    .035       0       0    .035       0     6.1    .035       0
#XS Ineff= 2 , 0
               0      20     6.1              20
Permanent Ineff=
       F       F
#Block Obstruct= 2 , 0
                             6.1
Bank Sta=0,6.1
XS Rating Curve= 0
Exp/Cntr=.3,.1

Type RM Length L Ch R = 1 ,12      ,50,50,50
#Sta/Elev= 11
      -2   13.55      -1   13.25       0   12.95      .7   11.75     1.9   11.75
     2.4   11.95    10.8   11.95    12.2   12.75    12.9   12.75    13.9   11.35
    23.9   11.35
#Mann= 3 , 0 , 0
      -2    .035       0       0    .035       0    12.2    .035       0
#XS Ineff= 2 , 0
               0      20    12.2              20
Permanent Ineff=
       F       F
#Block Obstruct= 2 , 0
                            12.2
Bank Sta=0,12.2
XS Rating Curve= 0
Exp/Cntr=.3,.1

Type RM Length L Ch R = 1 ,11      ,50,50,50
#Sta/Elev= 11
      -2   12.41      -1   12.11       0   11.81      .7   10.61     1.9   10.61
     2.4   11.01     6.4   11.01     7.6   11.91     8.3   11.91     9.5   10.51
    19.5   10.51
#Mann= 3 , 0 , 0
      -2    .035       0       0    .035       0     7.6    .035       0
#XS Ineff= 2 , 0
               0      20     7.6              20
Permanent Ineff=
       F       F
#Block Obstruct= 2 , 0
                             7.6
Bank Sta=0,7.6
XS Rating Curve= 0
Exp/Cntr=.3,.1

Type RM Length L Ch R = 1 ,10      ,50,50,50
#Sta/Elev= 12
      -4   14.54      -2   12.54       0   10.54       1      10     1.3    9.24
     2.8    9.24       3    9.64     4.4    9.64     4.9   11.04     5.6   11.04
     6.8    9.64    16.8    9.64
#Mann= 3 , 0 , 0
      -4    .035       0       0    .035       0     4.9    .035       0
#XS Ineff= 2 , 0
               0      20     4.9              20
Permanent Ineff=
       F       F
#Block Obstruct= 2 , 0
                             4.9
Bank Sta=0,4.9
XS Rating Curve= 0
Exp/Cntr=.3,.1

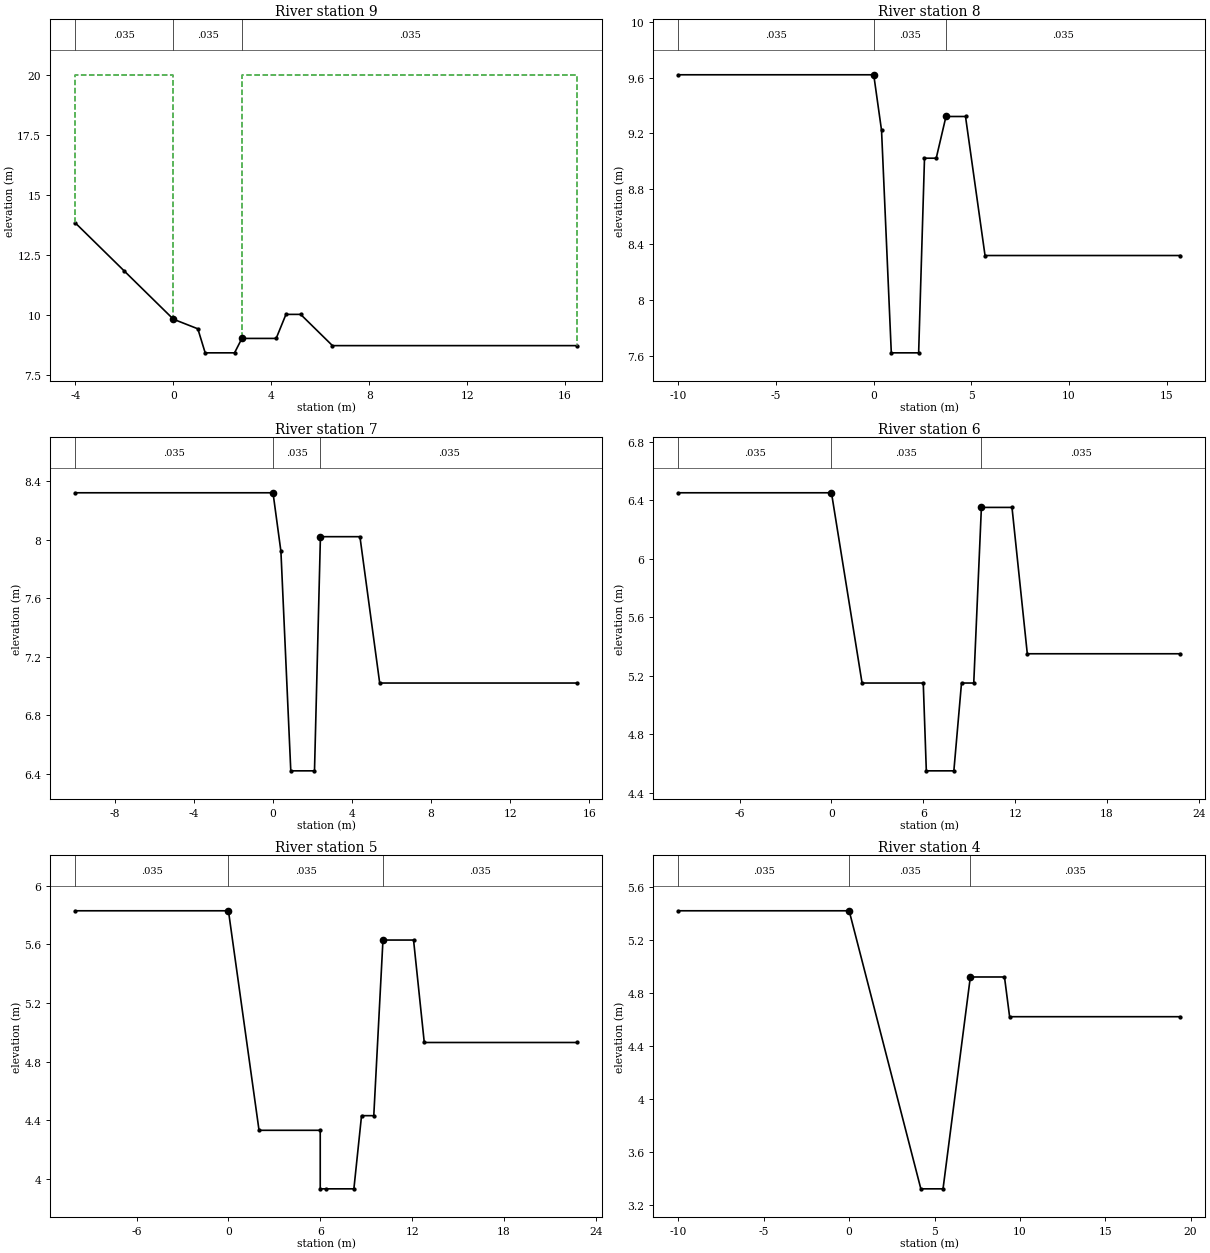
Type RM Length L Ch R = 1 ,9       ,50,50,50
#Sta/Elev= 12
      -4   13.83      -2   11.83       0    9.83       1    9.43     1.3    8.43
     2.5    8.43     2.8    9.03     4.2    9.03     4.6   10.03     5.2   10.03
     6.5    8.73    16.5    8.73
#Mann= 3 , 0 , 0
      -4    .035       0       0    .035       0     2.8    .035       0
#XS Ineff= 2 , 0
               0      20     2.8              20
Permanent Ineff=
       F       F
#Block Obstruct= 2 , 0
                             2.8
Bank Sta=0,2.8
XS Rating Curve= 0
Exp/Cntr=.3,.1

Type RM Length L Ch R = 1 ,8       ,50,50,50
#Sta/Elev= 11
     -10    9.62       0    9.62      .4    9.22      .9    7.62     2.3    7.62
     2.6    9.02     3.2    9.02     3.7    9.32     4.7    9.32     5.7    8.32
    15.7    8.32
#Mann= 3 , 0 , 0
     -10    .035       0       0    .035       0     3.7    .035       0
#XS Ineff= 2 , 0
               0      20     3.7              20
Permanent Ineff=
       F       F
#Block Obstruct= 2 , 0
                             3.7
Bank Sta=0,3.7
XS Rating Curve= 0
Exp/Cntr=.3,.1

Type RM Length L Ch R = 1 ,7       ,50,50,50
#Sta/Elev= 9
     -10    8.32       0    8.32      .4    7.92      .9    6.42     2.1    6.42
     2.4    8.02     4.4    8.02     5.4    7.02    15.4    7.02
#Mann= 3 , 0 , 0
     -10    .035       0       0    .035       0     2.4    .035       0
#XS Ineff= 2 , 0
               0      20     2.4              20
Permanent Ineff=
       F       F
#Block Obstruct= 2 , 0
                             2.4
Bank Sta=0,2.4
XS Rating Curve= 0
Exp/Cntr=.3,.1

Type RM Length L Ch R = 1 ,6       ,50,50,50
#Sta/Elev= 12
     -10    6.45       0    6.45       2    5.15       6    5.15     6.2    4.55
       8    4.55     8.5    5.15     9.3    5.15     9.8    6.35    11.8    6.35
    12.8    5.35    22.8    5.35
#Mann= 3 , 0 , 0
     -10    .035       0       0    .035       0     9.8    .035       0
#XS Ineff= 2 , 0
               0      20     9.8              20
Permanent Ineff=
       F       F
#Block Obstruct= 2 , 0
                             9.8
Bank Sta=0,9.8
XS Rating Curve= 0
Exp/Cntr=.3,.1

Type RM Length L Ch R = 1 ,5       ,50,50,50
#Sta/Elev= 13
     -10    5.83       0    5.83       2    4.33       6    4.33       6    3.93
     6.4    3.93     8.2    3.93     8.7    4.43     9.5    4.43    10.1    5.63
    12.1    5.63    12.8    4.93    22.8    4.93
#Mann= 3 , 0 , 0
     -10    .035       0       0    .035       0    10.1    .035       0
#XS Ineff= 2 , 0
               0      20    10.1              20
Permanent Ineff=
       F       F
#Block Obstruct= 2 , 0
                            10.1
Bank Sta=0,10.1
XS Rating Curve= 0
Exp/Cntr=.3,.1

Type RM Length L Ch R = 1 ,4       ,50,50,50
#Sta/Elev= 8
     -10    5.42       0    5.42     4.2    3.32     5.5    3.32     7.1    4.92
     9.1    4.92     9.4    4.62    19.4    4.62
#Mann= 3 , 0 , 0
     -10    .035       0       0    .035       0     7.1    .035       0
#XS Ineff= 2 , 0
               0      20     7.1              20
Permanent Ineff=
       F       F
#Block Obstruct= 2 , 0
                             7.1
Bank Sta=0,7.1
XS Rating Curve= 0
Exp/Cntr=.3,.1

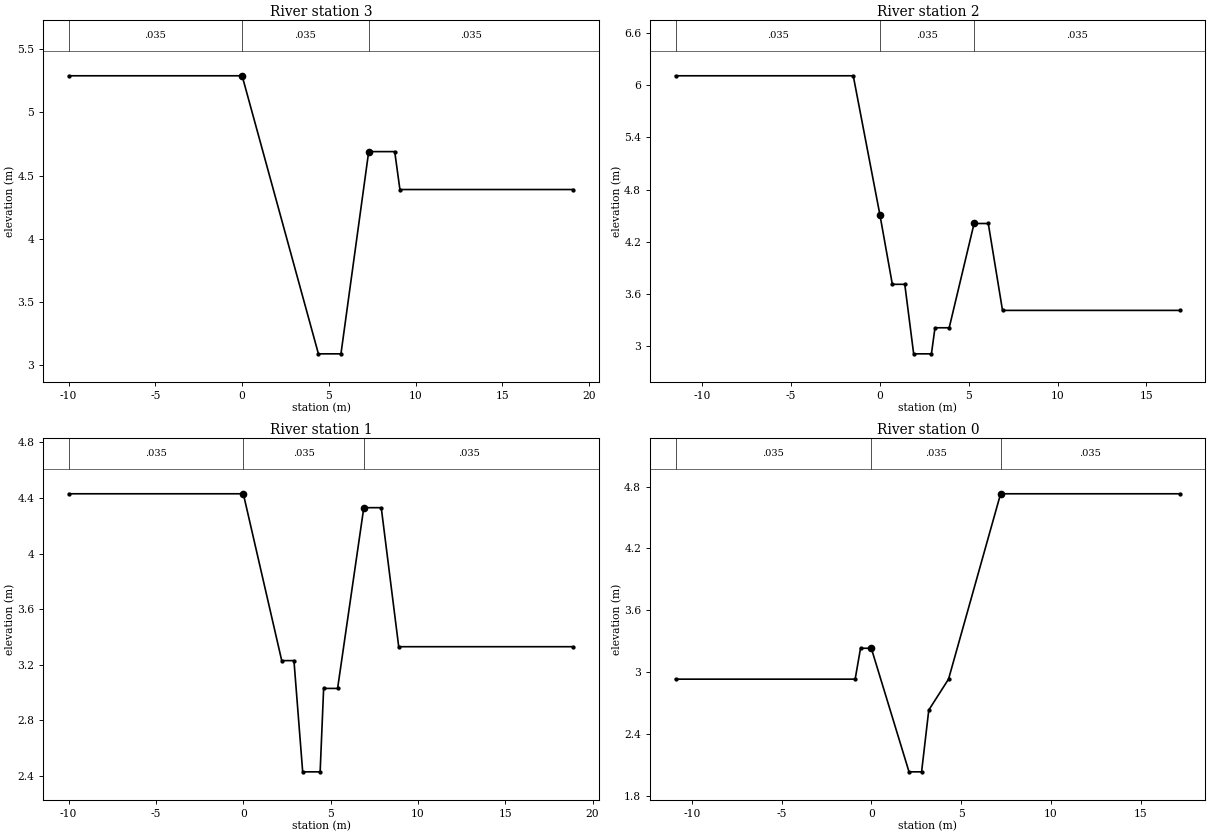
Type RM Length L Ch R = 1 ,3       ,50,50,50
#Sta/Elev= 8
     -10    5.29       0    5.29     4.4    3.09     5.7    3.09     7.3    4.69
     8.8    4.69     9.1    4.39    19.1    4.39
#Mann= 3 , 0 , 0
     -10    .035       0       0    .035       0     7.3    .035       0
#XS Ineff= 2 , 0
               0      20     7.3              20
Permanent Ineff=
       F       F
#Block Obstruct= 2 , 0
                             7.3
Bank Sta=0,7.3
XS Rating Curve= 0
Exp/Cntr=.3,.1

Type RM Length L Ch R = 1 ,2       ,50,50,50
#Sta/Elev= 13
   -11.5    6.11    -1.5    6.11       0    4.51      .7    3.71     1.4    3.71
     1.9    2.91     2.9    2.91     3.1    3.21     3.9    3.21     5.3    4.41
     6.1    4.41     6.9    3.41    16.9    3.41
#Mann= 3 , 0 , 0
   -11.5    .035       0       0    .035       0     5.3    .035       0
#XS Ineff= 2 , 0
               0      20     5.3              20
Permanent Ineff=
       F       F
#Block Obstruct= 2 , 0
                             5.3
Bank Sta=0,5.3
XS Rating Curve= 0
Exp/Cntr=.3,.1

Type RM Length L Ch R = 1 ,1       ,50,50,50
#Sta/Elev= 12
     -10    4.43       0    4.43     2.2    3.23     2.9    3.23     3.4    2.43
     4.4    2.43     4.6    3.03     5.4    3.03     6.9    4.33     7.9    4.33
     8.9    3.33    18.9    3.33
#Mann= 3 , 0 , 0
     -10    .035       0       0    .035       0     6.9    .035       0
#XS Ineff= 2 , 0
               0      20     6.9              20
Permanent Ineff=
       F       F
#Block Obstruct= 2 , 0
                             6.9
Bank Sta=0,6.9
XS Rating Curve= 0
Exp/Cntr=.3,.1

Type RM Length L Ch R = 1 ,0       ,0,0,0
#Sta/Elev= 10
   -10.9    2.93     -.9    2.93     -.6    3.23       0    3.23     2.1    2.03
     2.8    2.03     3.2    2.63     4.3    2.93     7.2    4.73    17.2    4.73
#Mann= 3 , 0 , 0
   -10.9    .035       0       0    .035       0     7.2    .035       0
#XS Ineff= 2 , 0
               0      20     7.2              20
Permanent Ineff=
       F       F
#Block Obstruct= 2 , 0
                             7.2
Bank Sta=0,7.2
XS Rating Curve= 0
Exp/Cntr=.3,.1

Chan Stop Cuts=-1