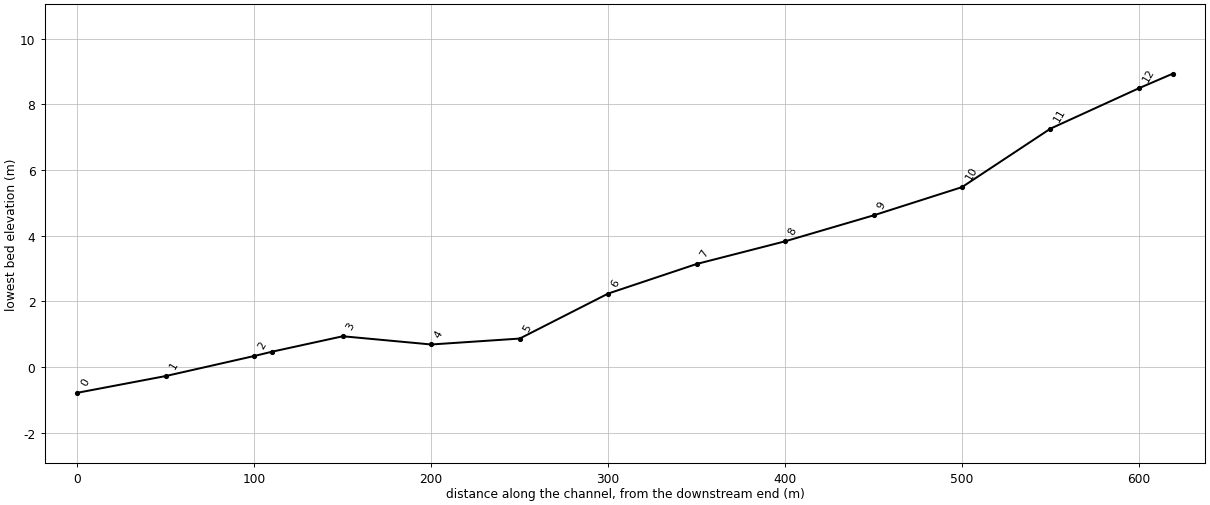
--- skc.prj (project) ---

Proj Title=sakok
Current Plan=p01
Default Exp/Contr=.3,.1
SI Units
Geom File=g01
Flow File=f01
Plan File=p01
Y Axis Title=Elevation
X Axis Title(PF)=Main Channel Distance
X Axis Title(XS)=Station
BEGIN DESCRIPTION:
           BACK WATER COMPUTATION
      APPLICATION OF HEC-2 BY Samju Construction Engineering
      sakok-ch: 10,20,30,50,80 yr
END DESCRIPTION:
DSS Export Rating Curves= 0
DSS Export Rating Curve Sorted= 0
DSS Export Volume Flow Curves= 0
DXF OffsetX= 0
DXF OffsetY= 0
DXF ScaleX= 1
DXF ScaleY= 10

--- skc.p01 (plan) ---

Plan Title=Imported Plan 01
Version=Version 3.0.1  Mar 2001
Short Identifier=Imported Pla
Geom File=g01
Flow File=f01
Subcritical Flow
K Sum by GR= 0
Std Step Tol= 0.003
Critical Tol= 0.003
Num of Std Step Trials= 20
Max Error Tol= 0.1
Flow Tol Ratio= 0.001
Split Flow NTrial= 30
Split Flow Tol= 0.02
Split Flow Ratio= 0.02
Log Output Level= 0
Friction Slope Method= 1
Unsteady Friction Slope Method= 2
Parabolic Critical Depth
Global Vel Dist= 0 , 0 , 0
Global Log Level= 0
CheckData=True
Encroach Param=-1 ,0,0, 0
Computation Interval=1HOUR
Output Interval=1HOUR
Run HTab= 0
Run UNet= 0
Run PostProcess= 0
UNET Theta= 1
UNET ZTol= 0.02
UNET ZSATol= 0.1
UNET MxIter= 20
UNET MaxInSteps= 20
UNET DtIC= 0
UNET DtMin= 0
UNET MaxCRTS= 20
UNET WFStab= 2
UNET SFStab= 1
UNET WFX= 1
UNET SFX= 1
UNET Convert EG Bridges=-1
UNET Use Existing IB Tables=-1
Instantaneous Interval=1HOUR
Write IC File= 0
Write Velocity= 0
Write Detailed= 0

--- skc.f01 (steady flow) ---

Flow Title=Imported Flow 01
Version=Version 3.0.1  Mar 2001
Number of Profiles= 5
Profile Names=10yr,20yr,30yr,50yr,80yr
River Rch & RM=RIVER-1,Reach-1         ,12.019
    5.69    6.27    6.61    7.04    7.43
River Rch & RM=SAKOK,SAKOK           ,12.019
    5.69    6.27    6.61    7.04    7.43
Boundary for River Rch & Prof#=SAKOK,SAKOK           , 1
Up Type= 0
Dn Type= 3
Dn Slope=.016
Boundary for River Rch & Prof#=SAKOK,SAKOK           , 2
Up Type= 0
Dn Type= 3
Dn Slope=.016
Boundary for River Rch & Prof#=SAKOK,SAKOK           , 3
Up Type= 0
Dn Type= 3
Dn Slope=.016
Boundary for River Rch & Prof#=SAKOK,SAKOK           , 4
Up Type= 0
Dn Type= 3
Dn Slope=.016
Boundary for River Rch & Prof#=SAKOK,SAKOK           , 5
Up Type= 0
Dn Type= 3
Dn Slope=.016
DSS Import GetInterval= 0
DSS Import GetPeak= 0
DSS Import FillOption= 0

--- skc.g01 (geometry) ---

Geom Title=Imported Geom 01
Version=Version 3.0.1  Mar 2001

River Reach=SAKOK           ,SAKOK
Reach XY= 2
              .5             .95              .5             .05

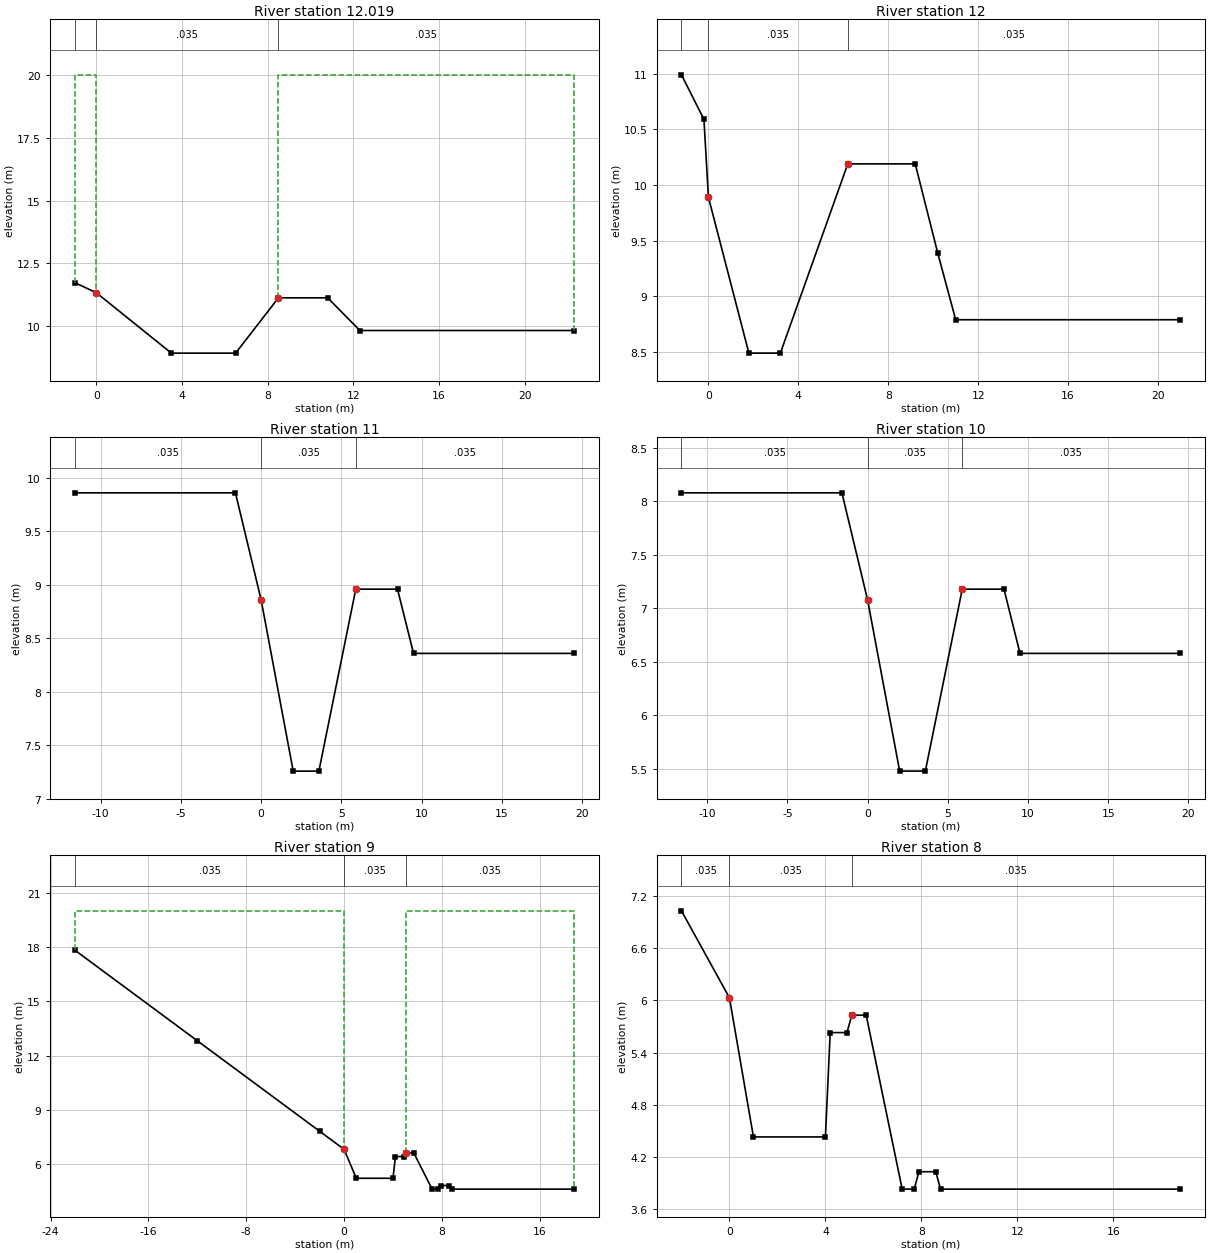
Type RM Length L Ch R = 1 ,12.019  ,19,19,19
#Sta/Elev= 8
      -1   11.73       0   11.33     3.5    8.93     6.5    8.93     8.5   11.13
    10.8   11.13    12.3    9.83    22.3    9.83
#Mann= 3 , 0 , 0
      -1    .035       0       0    .035       0     8.5    .035       0
#XS Ineff= 2 , 0
               0      20     8.5              20
Permanent Ineff=
       F       F
#Block Obstruct= 2 , 0
                             8.5
Bank Sta=0,8.5
XS Rating Curve= 0
Exp/Cntr=.3,.1

Type RM Length L Ch R = 1 ,12      ,50,50,50
#Sta/Elev= 10
    -1.2   10.99     -.2   10.59       0    9.89     1.8    8.49     3.2    8.49
     6.2   10.19     9.2   10.19    10.2    9.39      11    8.79      21    8.79
#Mann= 3 , 0 , 0
    -1.2    .035       0       0    .035       0     6.2    .035       0
#XS Ineff= 2 , 0
               0      20     6.2              20
Permanent Ineff=
       F       F
#Block Obstruct= 2 , 0
                             6.2
Bank Sta=0,6.2
XS Rating Curve= 0
Exp/Cntr=.3,.1

Type RM Length L Ch R = 1 ,11      ,50,50,50
#Sta/Elev= 9
   -11.6    9.86    -1.6    9.86       0    8.86       2    7.26     3.6    7.26
     5.9    8.96     8.5    8.96     9.5    8.36    19.5    8.36
#Mann= 3 , 0 , 0
   -11.6    .035       0       0    .035       0     5.9    .035       0
#XS Ineff= 2 , 0
               0      20     5.9              20
Permanent Ineff=
       F       F
#Block Obstruct= 2 , 0
                             5.9
Bank Sta=0,5.9
XS Rating Curve= 0
Exp/Cntr=.3,.1

Type RM Length L Ch R = 1 ,10      ,50,50,50
#Sta/Elev= 9
   -11.6    8.08    -1.6    8.08       0    7.08       2    5.48     3.6    5.48
     5.9    7.18     8.5    7.18     9.5    6.58    19.5    6.58
#Mann= 3 , 0 , 0
   -11.6    .035       0       0    .035       0     5.9    .035       0
#XS Ineff= 2 , 0
               0      20     5.9              20
Permanent Ineff=
       F       F
#Block Obstruct= 2 , 0
                             5.9
Bank Sta=0,5.9
XS Rating Curve= 0
Exp/Cntr=.3,.1

Type RM Length L Ch R = 1 ,9       ,50,50,50
#Sta/Elev= 16
     -22   17.82     -12   12.82      -2    7.82       0    6.82       1    5.22
       4    5.22     4.2    6.42     4.9    6.42     5.1    6.62     5.7    6.62
     7.2    4.62     7.7    4.62     7.9    4.82     8.6    4.82     8.8    4.62
    18.8    4.62
#Mann= 3 , 0 , 0
     -22    .035       0       0    .035       0     5.1    .035       0
#XS Ineff= 2 , 0
               0      20     5.1              20
Permanent Ineff=
       F       F
#Block Obstruct= 2 , 0
                             5.1
Bank Sta=0,5.1
XS Rating Curve= 0
Exp/Cntr=.3,.1

Type RM Length L Ch R = 1 ,8       ,50,50,50
#Sta/Elev= 14
      -2    7.03       0    6.03       1    4.43       4    4.43     4.2    5.63
     4.9    5.63     5.1    5.83     5.7    5.83     7.2    3.83     7.7    3.83
     7.9    4.03     8.6    4.03     8.8    3.83    18.8    3.83
#Mann= 3 , 0 , 0
      -2    .035       0       0    .035       0     5.1    .035       0
#XS Ineff= 2 , 0
               0      20     5.1              20
Permanent Ineff=
       F       F
#Block Obstruct= 2 , 0
                             5.1
Bank Sta=0,5.1
XS Rating Curve= 0
Exp/Cntr=.3,.1

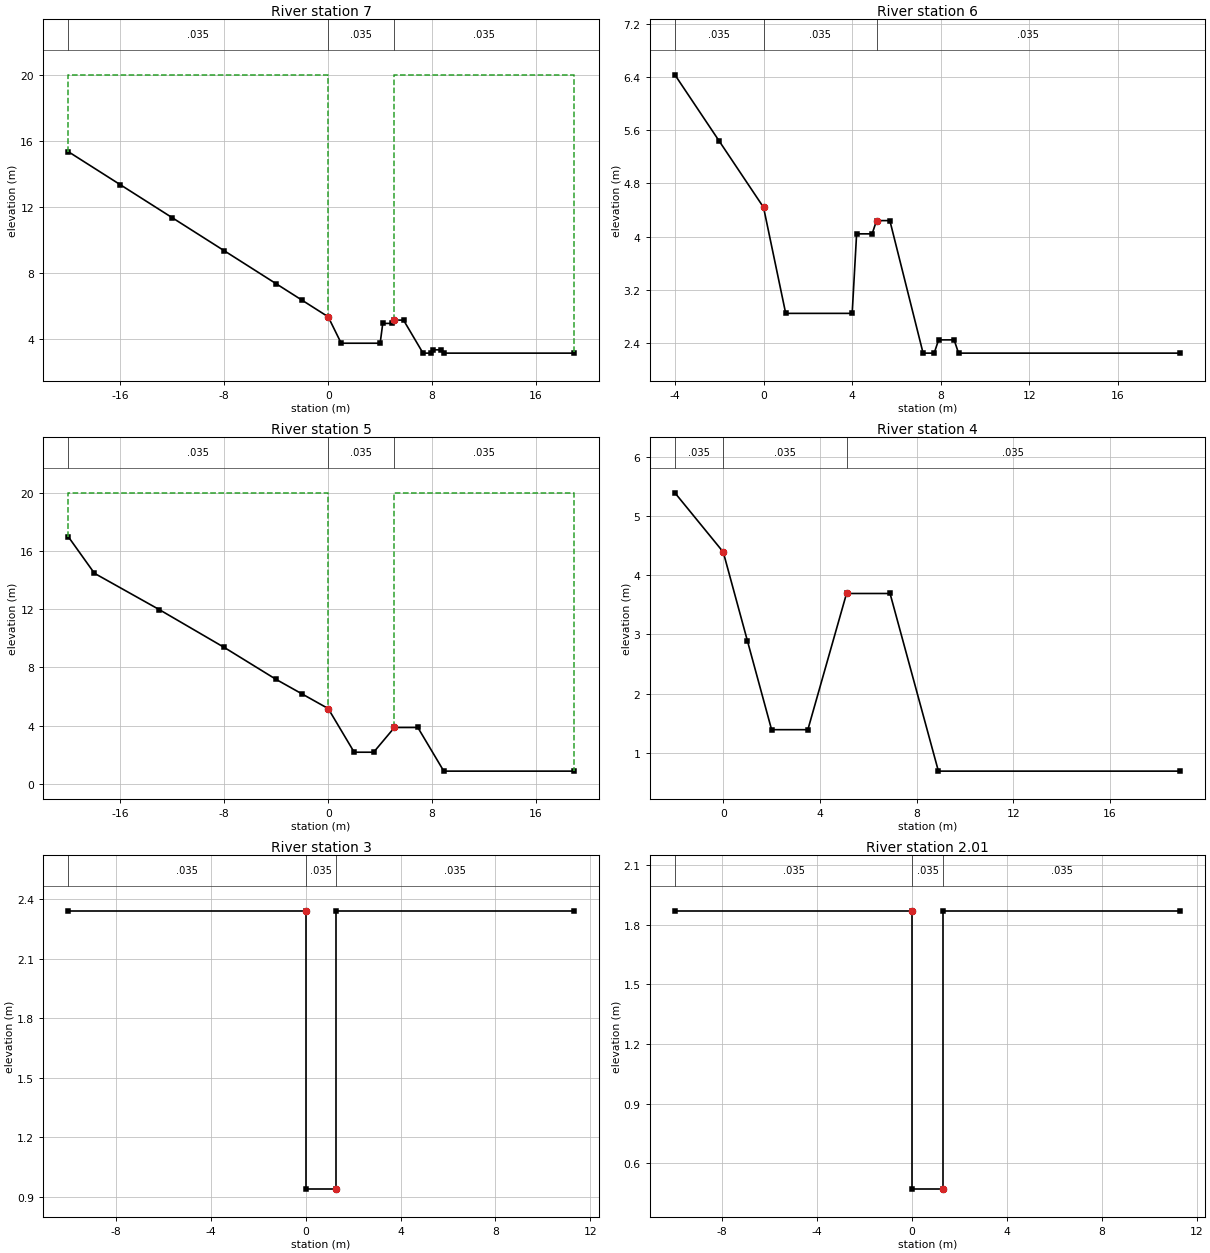
Type RM Length L Ch R = 1 ,7       ,50,50,50
#Sta/Elev= 19
     -20   15.34     -16   13.34     -12   11.34      -8    9.34      -4    7.34
      -2    6.34       0    5.34       1    3.74       4    3.74     4.2    4.94
     4.9    4.94     5.1    5.14     5.8    5.14     7.3    3.14     7.9    3.14
     8.1    3.34     8.7    3.34     8.9    3.14    18.9    3.14
#Mann= 3 , 0 , 0
     -20    .035       0       0    .035       0     5.1    .035       0
#XS Ineff= 2 , 0
               0      20     5.1              20
Permanent Ineff=
       F       F
#Block Obstruct= 2 , 0
                             5.1
Bank Sta=0,5.1
XS Rating Curve= 0
Exp/Cntr=.3,.1

Type RM Length L Ch R = 1 ,6       ,50,50,50
#Sta/Elev= 15
      -4    6.44      -2    5.44       0    4.44       1    2.84       4    2.84
     4.2    4.04     4.9    4.04     5.1    4.24     5.7    4.24     7.2    2.24
     7.7    2.24     7.9    2.44     8.6    2.44     8.8    2.24    18.8    2.24
#Mann= 3 , 0 , 0
      -4    .035       0       0    .035       0     5.1    .035       0
#XS Ineff= 2 , 0
               0      20     5.1              20
Permanent Ineff=
       F       F
#Block Obstruct= 2 , 0
                             5.1
Bank Sta=0,5.1
XS Rating Curve= 0
Exp/Cntr=.3,.1

Type RM Length L Ch R = 1 ,5       ,50,50,50
#Sta/Elev= 13
     -20   16.97     -18   14.47     -13   11.97      -8    9.37      -4    7.17
      -2    6.17       0    5.17       2    2.17     3.5    2.17     5.1    3.87
     6.9    3.87     8.9     .87    18.9     .87
#Mann= 3 , 0 , 0
     -20    .035       0       0    .035       0     5.1    .035       0
#XS Ineff= 2 , 0
               0      20     5.1              20
Permanent Ineff=
       F       F
#Block Obstruct= 2 , 0
                             5.1
Bank Sta=0,5.1
XS Rating Curve= 0
Exp/Cntr=.3,.1

Type RM Length L Ch R = 1 ,4       ,50,50,50
#Sta/Elev= 9
      -2    5.39       0    4.39       1    2.89       2    1.39     3.5    1.39
     5.1    3.69     6.9    3.69     8.9     .69    18.9     .69
#Mann= 3 , 0 , 0
      -2    .035       0       0    .035       0     5.1    .035       0
#XS Ineff= 2 , 0
               0      20     5.1              20
Permanent Ineff=
       F       F
#Block Obstruct= 2 , 0
                             5.1
Bank Sta=0,5.1
XS Rating Curve= 0
Exp/Cntr=.3,.1

Type RM Length L Ch R = 1 ,3       ,40,40,40
#Sta/Elev= 6
     -10    2.34       0    2.34       0     .94     1.3     .94     1.3    2.34
    11.3    2.34
#Mann= 3 , 0 , 0
     -10    .035       0       0    .035       0     1.3    .035       0
#XS Ineff= 2 , 0
               0      20     1.3              20
Permanent Ineff=
       F       F
#Block Obstruct= 2 , 0
                             1.3
Bank Sta=0,1.3
XS Rating Curve= 0
Exp/Cntr=.3,.1

Type RM Length L Ch R = 1 ,2.01    ,10,10,10
#Sta/Elev= 6
     -10    1.87       0    1.87       0     .47     1.3     .47     1.3    1.87
    11.3    1.87
#Mann= 3 , 0 , 0
     -10    .035       0       0    .035       0     1.3    .035       0
#XS Ineff= 2 , 0
               0      20     1.3              20
Permanent Ineff=
       F       F
#Block Obstruct= 2 , 0
                             1.3
Bank Sta=0,1.3
XS Rating Curve= 0
Exp/Cntr=.3,.1

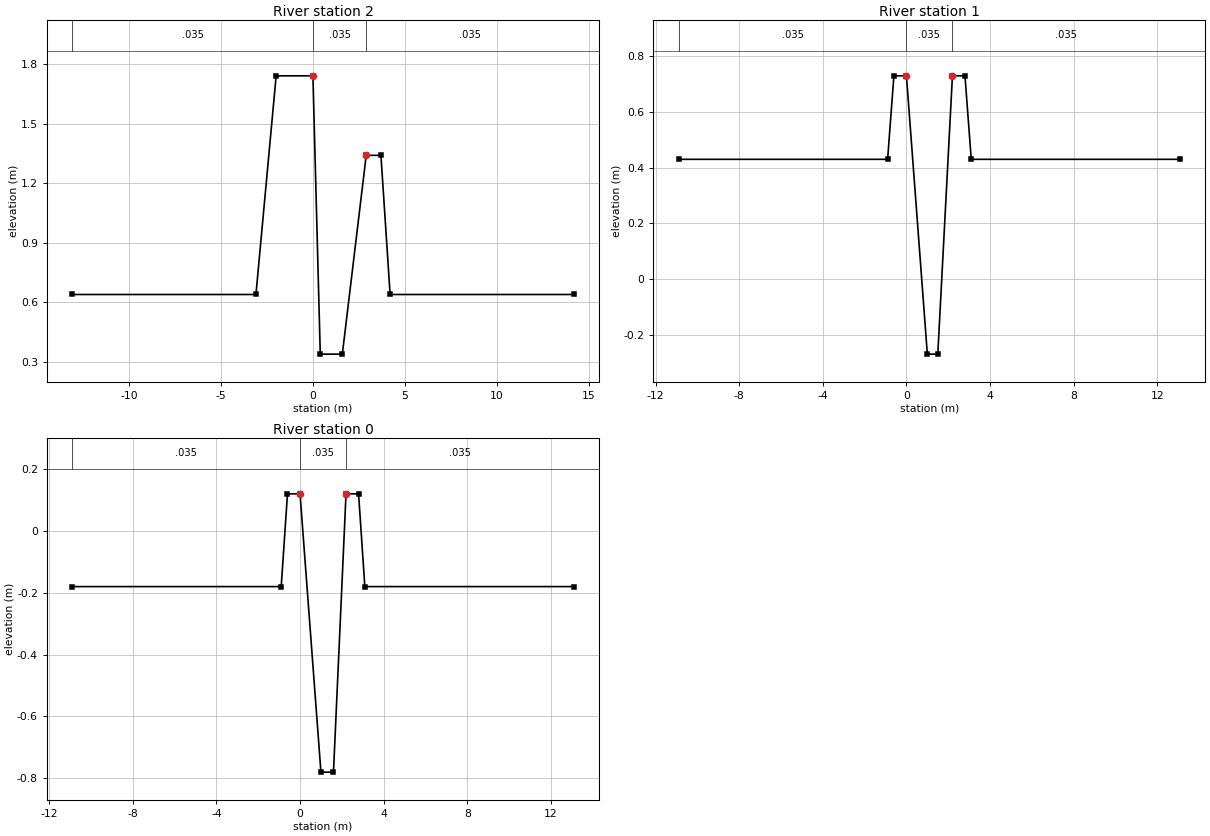
Type RM Length L Ch R = 1 ,2       ,50,50,50
#Sta/Elev= 10
   -13.1     .64    -3.1     .64      -2    1.74       0    1.74      .4     .34
     1.6     .34     2.9    1.34     3.7    1.34     4.2     .64    14.2     .64
#Mann= 3 , 0 , 0
   -13.1    .035       0       0    .035       0     2.9    .035       0
#XS Ineff= 2 , 0
               0      20     2.9              20
Permanent Ineff=
       F       F
#Block Obstruct= 2 , 0
                             2.9
Bank Sta=0,2.9
XS Rating Curve= 0
Exp/Cntr=.3,.1

Type RM Length L Ch R = 1 ,1       ,50,50,50
#Sta/Elev= 10
   -10.9     .43     -.9     .43     -.6     .73       0     .73       1    -.27
     1.5    -.27     2.2     .73     2.8     .73     3.1     .43    13.1     .43
#Mann= 3 , 0 , 0
   -10.9    .035       0       0    .035       0     2.2    .035       0
#XS Ineff= 2 , 0
               0      20     2.2              20
Permanent Ineff=
       F       F
#Block Obstruct= 2 , 0
                             2.2
Bank Sta=0,2.2
XS Rating Curve= 0
Exp/Cntr=.3,.1

Type RM Length L Ch R = 1 ,0       ,0,0,0
#Sta/Elev= 10
   -10.9    -.18     -.9    -.18     -.6     .12       0     .12       1    -.78
     1.6    -.78     2.2     .12     2.8     .12     3.1    -.18    13.1    -.18
#Mann= 3 , 0 , 0
   -10.9    .035       0       0    .035       0     2.2    .035       0
#XS Ineff= 2 , 0
               0      20     2.2              20
Permanent Ineff=
       F       F
#Block Obstruct= 2 , 0
                             2.2
Bank Sta=0,2.2
XS Rating Curve= 0
Exp/Cntr=.3,.1

Chan Stop Cuts=-1