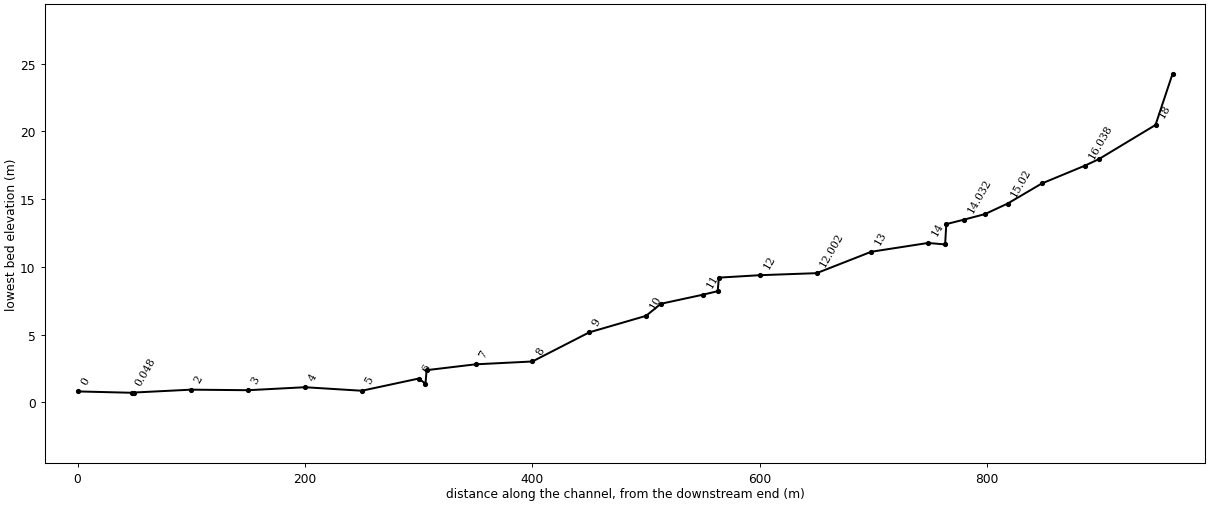
--- sjc.prj (project) ---

Proj Title=sajung
Current Plan=p01
Default Exp/Contr=.3,.1
SI Units
Geom File=g01
Flow File=f01
Plan File=p01
Y Axis Title=Elevation
X Axis Title(PF)=Main Channel Distance
X Axis Title(XS)=Station
BEGIN DESCRIPTION:
           BACK WATER COMPUTATION
      APPLICATION OF HEC-2 BY Samju Construction Engineering
      sajung-ch: 10,20,30,50,80 yr
END DESCRIPTION:
DSS Export Rating Curves= 0
DSS Export Rating Curve Sorted= 0
DSS Export Volume Flow Curves= 0
DXF OffsetX= 0
DXF OffsetY= 0
DXF ScaleX= 1
DXF ScaleY= 10

--- sjc.p01 (plan) ---

Plan Title=Imported Plan 01
Version=Version 3.0.1  Mar 2001
Short Identifier=Imported Pla
Geom File=g01
Flow File=f01
Subcritical Flow
K Sum by GR= 0
Std Step Tol= 0.003
Critical Tol= 0.003
Num of Std Step Trials= 20
Max Error Tol= 0.1
Flow Tol Ratio= 0.001
Split Flow NTrial= 30
Split Flow Tol= 0.02
Split Flow Ratio= 0.02
Log Output Level= 0
Friction Slope Method= 1
Unsteady Friction Slope Method= 2
Parabolic Critical Depth
Global Vel Dist= 0 , 0 , 0
Global Log Level= 0
CheckData=True
Encroach Param=-1 ,0,0, 0
Computation Interval=1HOUR
Output Interval=1HOUR
Run HTab= 0
Run UNet= 0
Run PostProcess= 0
UNET Theta= 1
UNET ZTol= 0.02
UNET ZSATol= 0.1
UNET MxIter= 20
UNET MaxInSteps= 20
UNET DtIC= 0
UNET DtMin= 0
UNET MaxCRTS= 20
UNET WFStab= 2
UNET SFStab= 1
UNET WFX= 1
UNET SFX= 1
UNET Convert EG Bridges=-1
UNET Use Existing IB Tables=-1
Instantaneous Interval=1HOUR
Write IC File= 0
Write Velocity= 0
Write Detailed= 0

--- sjc.f01 (steady flow) ---

Flow Title=Imported Flow 01
Version=Version 3.0.1  Mar 2001
Number of Profiles= 5
Profile Names=10yr,20yr,30yr,50yr,80yr
River Rch & RM=RIVER-1,Reach-1         ,18.015
   12.19   13.43   14.15   15.06    15.9
River Rch & RM=SAJUNG,SAJUNG          ,18.015
   12.19   13.43   14.15   15.06    15.9
Boundary for River Rch & Prof#=SAJUNG,SAJUNG          , 1
Up Type= 0
Dn Type= 3
Dn Slope=.027
Boundary for River Rch & Prof#=SAJUNG,SAJUNG          , 2
Up Type= 0
Dn Type= 3
Dn Slope=.027
Boundary for River Rch & Prof#=SAJUNG,SAJUNG          , 3
Up Type= 0
Dn Type= 3
Dn Slope=.027
Boundary for River Rch & Prof#=SAJUNG,SAJUNG          , 4
Up Type= 0
Dn Type= 3
Dn Slope=.027
Boundary for River Rch & Prof#=SAJUNG,SAJUNG          , 5
Up Type= 0
Dn Type= 3
Dn Slope=.027
DSS Import GetInterval= 0
DSS Import GetPeak= 0
DSS Import FillOption= 0

--- sjc.g01 (geometry) ---

Geom Title=Imported Geom 01
Version=Version 3.0.1  Mar 2001

River Reach=SAJUNG          ,SAJUNG
Reach XY= 2
              .5             .95              .5             .05

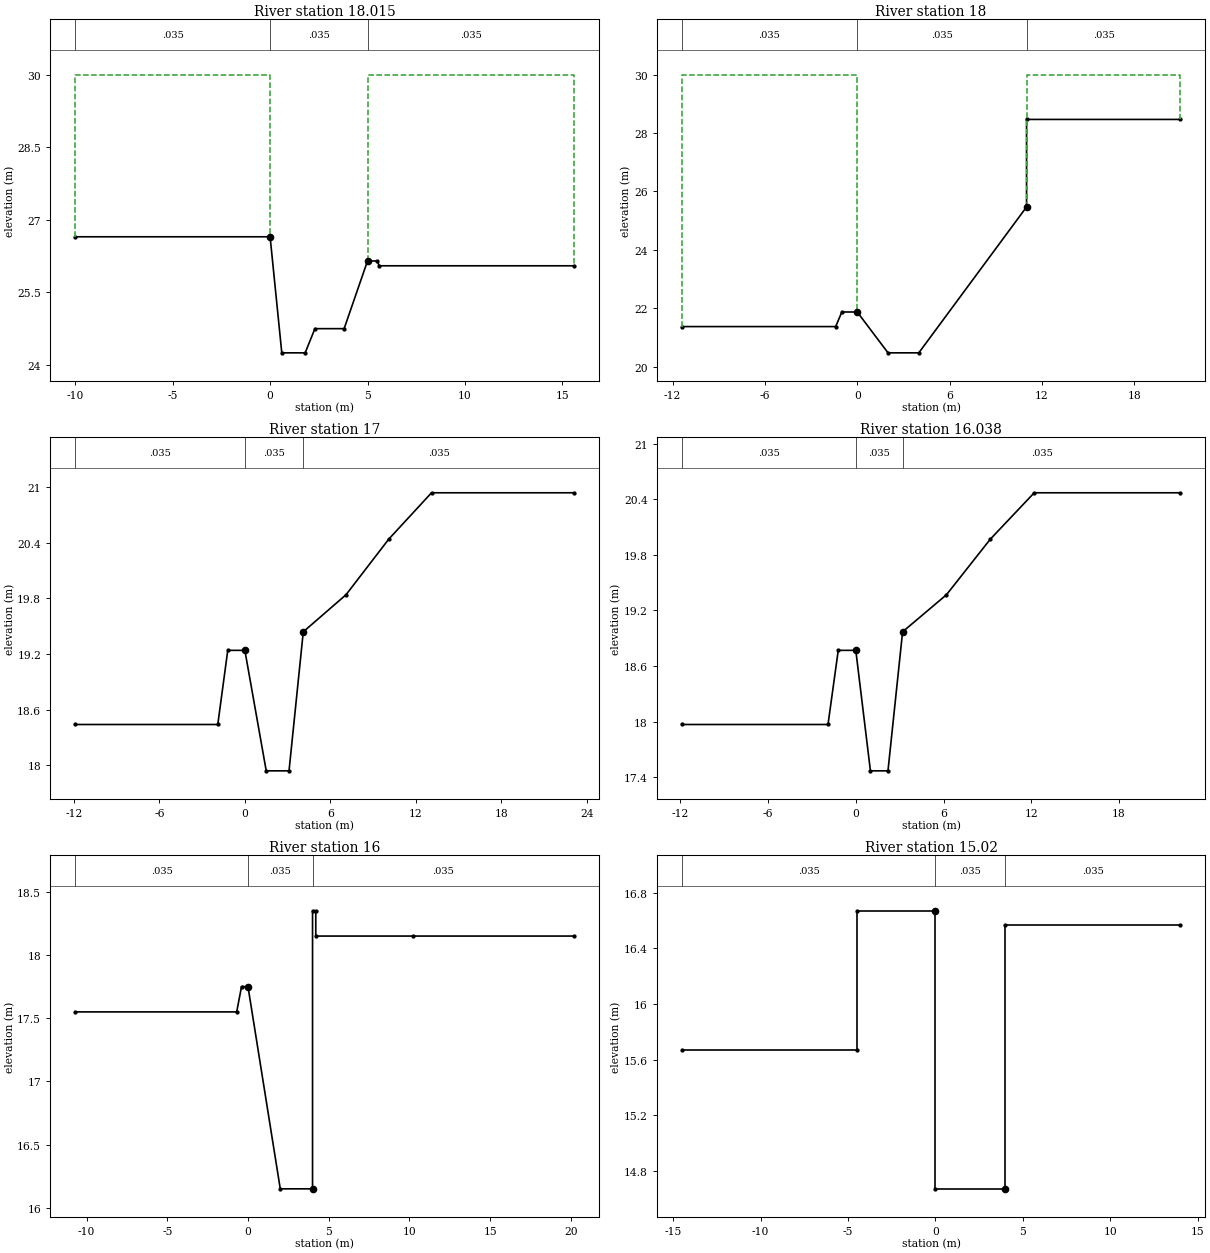
Type RM Length L Ch R = 1 ,18.015  ,15,15,15
#Sta/Elev= 10
     -10   26.65       0   26.65      .6   24.25     1.8   24.25     2.3   24.75
     3.8   24.75       5   26.15     5.5   26.15     5.6   26.05    15.6   26.05
#Mann= 3 , 0 , 0
     -10    .035       0       0    .035       0       5    .035       0
#XS Ineff= 2 , 0
               0      30       5              30
Permanent Ineff=
       F       F
#Block Obstruct= 2 , 0
                               5
Bank Sta=0,5
XS Rating Curve= 0
Exp/Cntr=.3,.1

Type RM Length L Ch R = 1 ,18      ,50,50,50
#Sta/Elev= 9
   -11.4   21.37    -1.4   21.37      -1   21.87       0   21.87       2   20.47
       4   20.47      11   25.47      11   28.47      21   28.47
#Mann= 3 , 0 , 0
   -11.4    .035       0       0    .035       0      11    .035       0
#XS Ineff= 2 , 0
               0      30      11              30
Permanent Ineff=
       F       F
#Block Obstruct= 2 , 0
                              11
Bank Sta=0,11
XS Rating Curve= 0
Exp/Cntr=.3,.1

Type RM Length L Ch R = 1 ,17      ,12,12,12
#Sta/Elev= 11
   -11.9   18.44    -1.9   18.44    -1.2   19.24       0   19.24     1.5   17.94
     3.1   17.94     4.1   19.44     7.1   19.84    10.1   20.44    13.1   20.94
    23.1   20.94
#Mann= 3 , 0 , 0
   -11.9    .035       0       0    .035       0     4.1    .035       0
#XS Ineff= 2 , 0
               0      30     4.1              30
Permanent Ineff=
       F       F
#Block Obstruct= 2 , 0
                             4.1
Bank Sta=0,4.1
XS Rating Curve= 0
Exp/Cntr=.3,.1

Type RM Length L Ch R = 1 ,16.038  ,38,38,38
#Sta/Elev= 11
   -11.9   17.97    -1.9   17.97    -1.2   18.77       0   18.77       1   17.47
     2.2   17.47     3.2   18.97     6.2   19.37     9.2   19.97    12.2   20.47
    22.2   20.47
#Mann= 3 , 0 , 0
   -11.9    .035       0       0    .035       0     3.2    .035       0
#XS Ineff= 2 , 0
               0      30     3.2              30
Permanent Ineff=
       F       F
#Block Obstruct= 2 , 0
                             3.2
Bank Sta=0,3.2
XS Rating Curve= 0
Exp/Cntr=.3,.1

Type RM Length L Ch R = 1 ,16      ,30,30,30
#Sta/Elev= 11
   -10.7   17.55     -.7   17.55     -.4   17.75       0   17.75       2   16.15
       4   16.15       4   18.35     4.2   18.35     4.2   18.15    10.2   18.15
    20.2   18.15
#Mann= 3 , 0 , 0
   -10.7    .035       0       0    .035       0       4    .035       0
#XS Ineff= 2 , 0
               0      30       4              30
Permanent Ineff=
       F       F
#Block Obstruct= 2 , 0
                               4
Bank Sta=0,4
XS Rating Curve= 0
Exp/Cntr=.3,.1

Type RM Length L Ch R = 1 ,15.02   ,20,20,20
#Sta/Elev= 8
   -14.5   15.67    -4.5   15.67    -4.5   16.67       0   16.67       0   14.67
       4   14.67       4   16.57      14   16.57
#Mann= 3 , 0 , 0
   -14.5    .035       0       0    .035       0       4    .035       0
#XS Ineff= 2 , 0
               0      30       4              30
Permanent Ineff=
       F       F
#Block Obstruct= 2 , 0
                               4
Bank Sta=0,4
XS Rating Curve= 0
Exp/Cntr=.3,.1

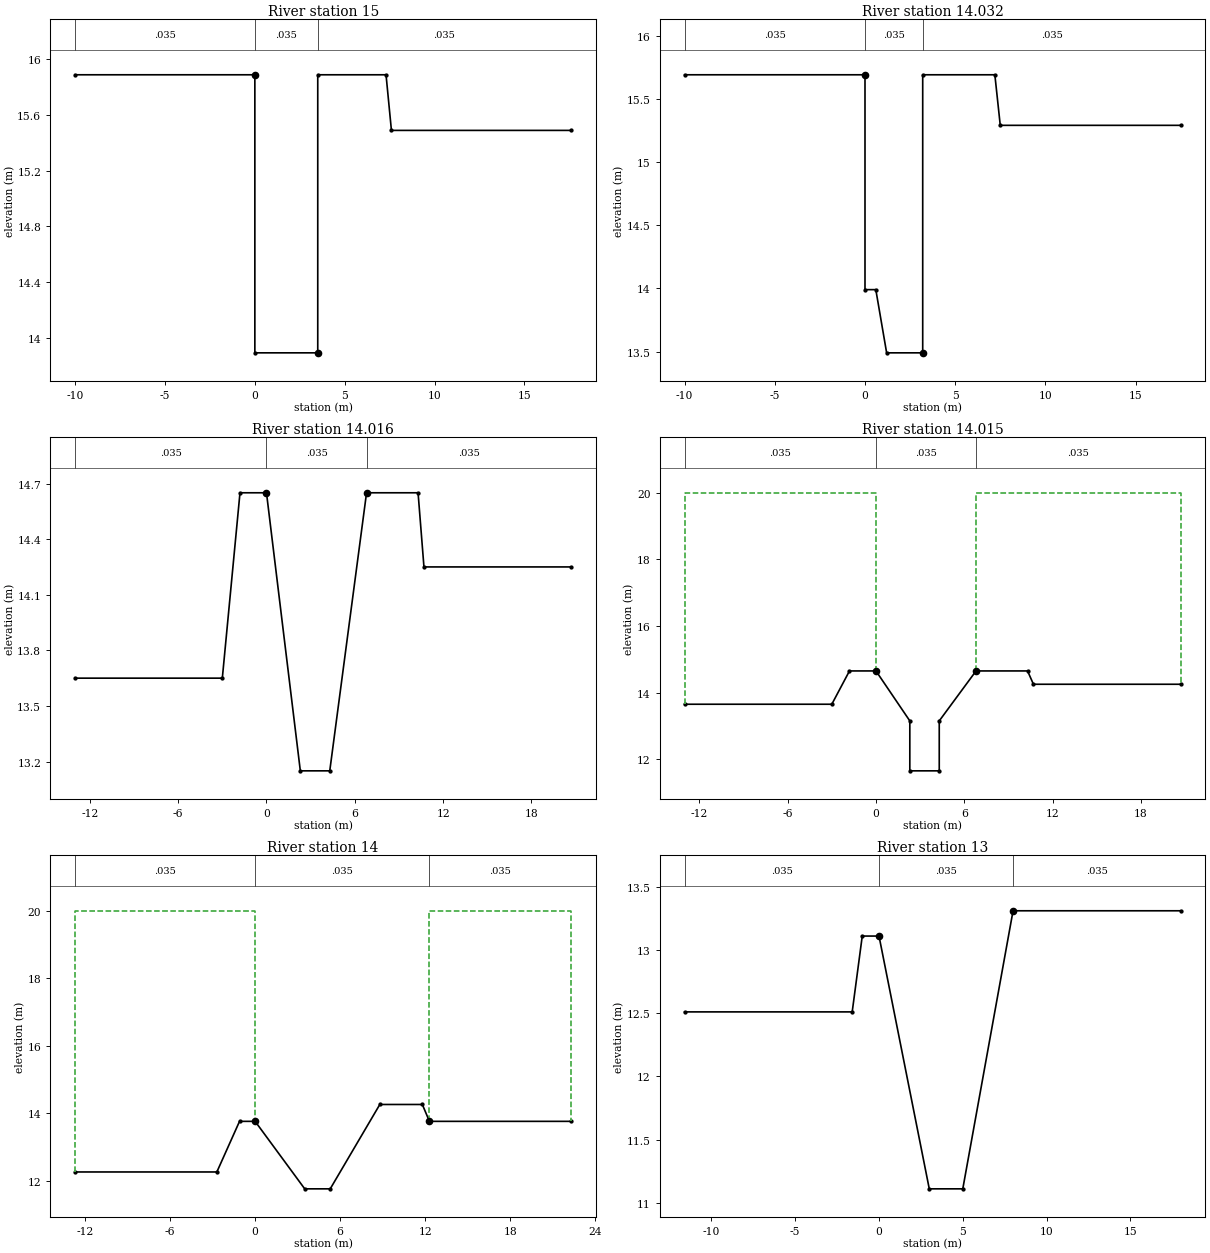
Type RM Length L Ch R = 1 ,15      ,18,18,18
#Sta/Elev= 8
     -10   15.89       0   15.89       0   13.89     3.5   13.89     3.5   15.89
     7.3   15.89     7.6   15.49    17.6   15.49
#Mann= 3 , 0 , 0
     -10    .035       0       0    .035       0     3.5    .035       0
#XS Ineff= 2 , 0
               0      30     3.5              30
Permanent Ineff=
       F       F
#Block Obstruct= 2 , 0
                             3.5
Bank Sta=0,3.5
XS Rating Curve= 0
Exp/Cntr=.3,.1

Type RM Length L Ch R = 1 ,14.032  ,16,16,16
#Sta/Elev= 10
     -10   15.69       0   15.69       0   13.99      .6   13.99     1.2   13.49
     3.2   13.49     3.2   15.69     7.2   15.69     7.5   15.29    17.5   15.29
#Mann= 3 , 0 , 0
     -10    .035       0       0    .035       0     3.2    .035       0
#XS Ineff= 2 , 0
               0      30     3.2              30
Permanent Ineff=
       F       F
#Block Obstruct= 2 , 0
                             3.2
Bank Sta=0,3.2
XS Rating Curve= 0
Exp/Cntr=.3,.1

Type RM Length L Ch R = 1 ,14.016  ,1,1,1
#Sta/Elev= 10
     -13   13.65      -3   13.65    -1.8   14.65       0   14.65     2.3   13.15
     4.3   13.15     6.8   14.65    10.3   14.65    10.7   14.25    20.7   14.25
#Mann= 3 , 0 , 0
     -13    .035       0       0    .035       0     6.8    .035       0
#XS Ineff= 2 , 0
               0      20     6.8              20
Permanent Ineff=
       F       F
#Block Obstruct= 2 , 0
                             6.8
Bank Sta=0,6.8
XS Rating Curve= 0
Exp/Cntr=.3,.1

Type RM Length L Ch R = 1 ,14.015  ,15,15,15
#Sta/Elev= 12
     -13   13.65      -3   13.65    -1.8   14.65       0   14.65     2.3   13.15
     2.3   11.65     4.3   11.65     4.3   13.15     6.8   14.65    10.3   14.65
    10.7   14.25    20.7   14.25
#Mann= 3 , 0 , 0
     -13    .035       0       0    .035       0     6.8    .035       0
#XS Ineff= 2 , 0
               0      20     6.8              20
Permanent Ineff=
       F       F
#Block Obstruct= 2 , 0
                             6.8
Bank Sta=0,6.8
XS Rating Curve= 0
Exp/Cntr=.3,.1

Type RM Length L Ch R = 1 ,14      ,50,50,50
#Sta/Elev= 10
   -12.7   12.26    -2.7   12.26    -1.1   13.76       0   13.76     3.5   11.76
     5.3   11.76     8.8   14.26    11.8   14.26    12.3   13.76    22.3   13.76
#Mann= 3 , 0 , 0
   -12.7    .035       0       0    .035       0    12.3    .035       0
#XS Ineff= 2 , 0
               0      20    12.3              20
Permanent Ineff=
       F       F
#Block Obstruct= 2 , 0
                            12.3
Bank Sta=0,12.3
XS Rating Curve= 0
Exp/Cntr=.3,.1

Type RM Length L Ch R = 1 ,13      ,48,48,48
#Sta/Elev= 8
   -11.6   12.51    -1.6   12.51      -1   13.11       0   13.11       3   11.11
       5   11.11       8   13.31      18   13.31
#Mann= 3 , 0 , 0
   -11.6    .035       0       0    .035       0       8    .035       0
#XS Ineff= 2 , 0
               0      20       8              20
Permanent Ineff=
       F       F
#Block Obstruct= 2 , 0
                               8
Bank Sta=0,8
XS Rating Curve= 0
Exp/Cntr=.3,.1

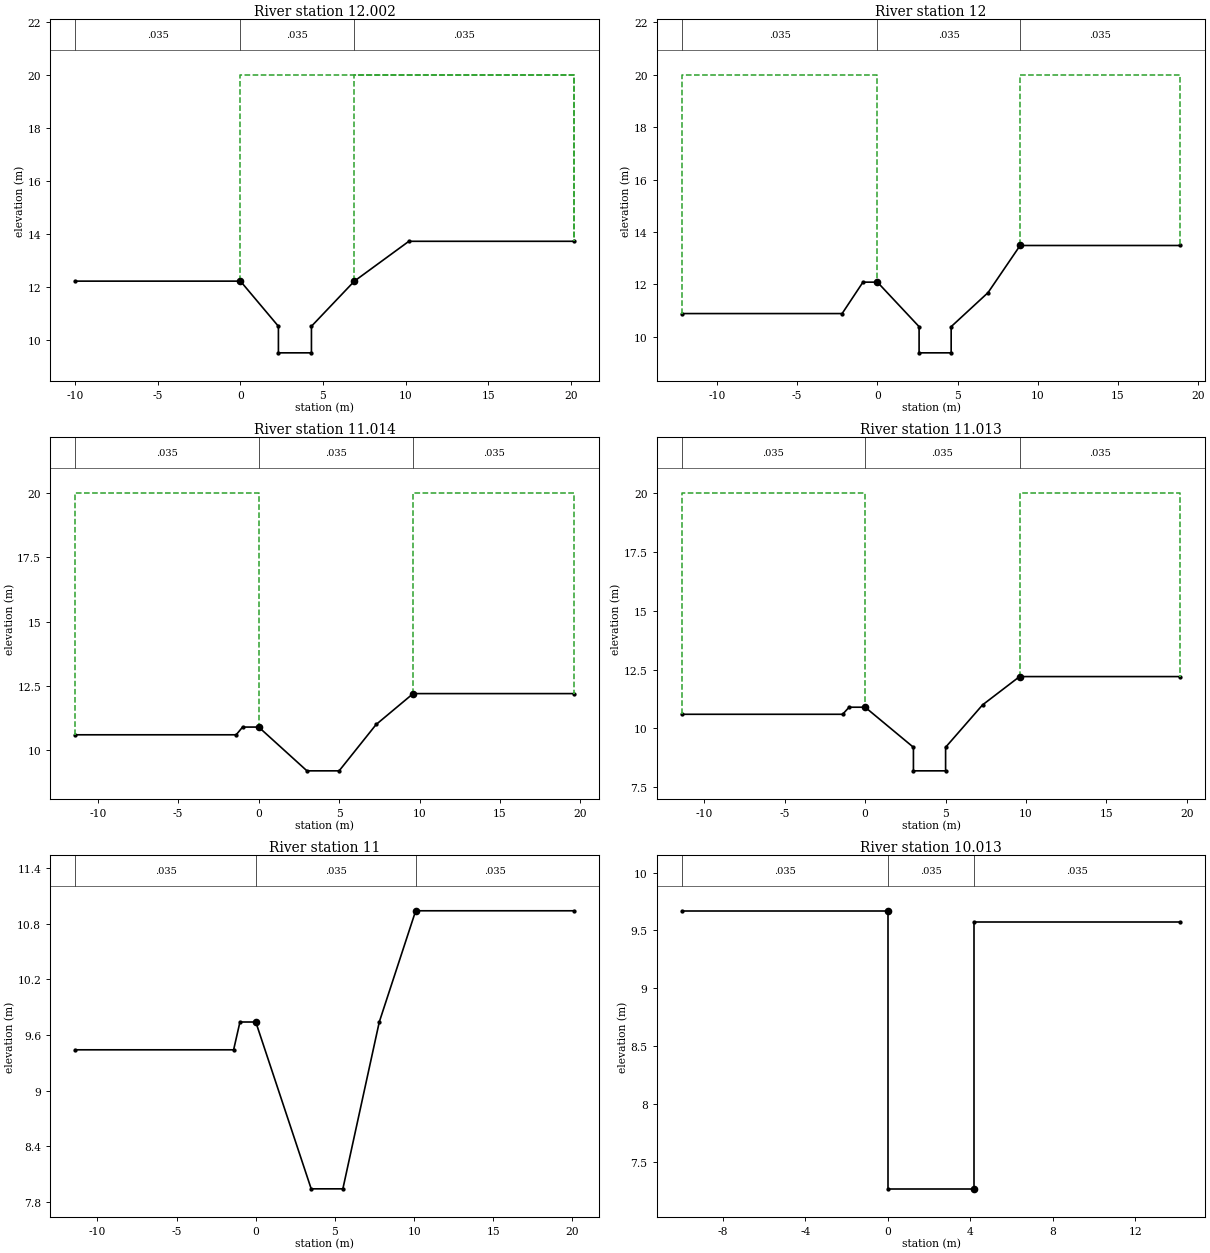
Type RM Length L Ch R = 1 ,12.002  ,50,50,50
#Sta/Elev= 9
     -10   12.23       0   12.23     2.3   10.53     2.3    9.53     4.3    9.53
     4.3   10.53     6.9   12.23    10.2   13.73    20.2   13.73
#Mann= 3 , 0 , 0
     -10    .035       0       0    .035       0     6.9    .035       0
#XS Ineff= 2 , 0
       0       0      20     6.9       0      20
Permanent Ineff=
       F       F
Bank Sta=0,6.9
XS Rating Curve= 0
Exp/Cntr=.3,.1

Type RM Length L Ch R = 1 ,12      ,36,36,36
#Sta/Elev= 11
   -12.2   10.88    -2.2   10.88     -.9   12.08       0   12.08     2.6   10.38
     2.6    9.38     4.6    9.38     4.6   10.38     6.9   11.68     8.9   13.48
    18.9   13.48
#Mann= 3 , 0 , 0
   -12.2    .035       0       0    .035       0     8.9    .035       0
#XS Ineff= 2 , 0
               0      20     8.9              20
Permanent Ineff=
       F       F
#Block Obstruct= 2 , 0
                             8.9
Bank Sta=0,8.9
XS Rating Curve= 0
Exp/Cntr=.3,.1

Type RM Length L Ch R = 1 ,11.014  ,1,1,1
#Sta/Elev= 9
   -11.4    10.6    -1.4    10.6      -1    10.9       0    10.9       3     9.2
       5     9.2     7.3      11     9.6    12.2    19.6    12.2
#Mann= 3 , 0 , 0
   -11.4    .035       0       0    .035       0     9.6    .035       0
#XS Ineff= 2 , 0
               0      20     9.6              20
Permanent Ineff=
       F       F
#Block Obstruct= 2 , 0
                             9.6
Bank Sta=0,9.6
XS Rating Curve= 0
Exp/Cntr=.3,.1

Type RM Length L Ch R = 1 ,11.013  ,13,13,13
#Sta/Elev= 11
   -11.4    10.6    -1.4    10.6      -1    10.9       0    10.9       3     9.2
       3     8.2       5     8.2       5     9.2     7.3      11     9.6    12.2
    19.6    12.2
#Mann= 3 , 0 , 0
   -11.4    .035       0       0    .035       0     9.6    .035       0
#XS Ineff= 2 , 0
               0      20     9.6              20
Permanent Ineff=
       F       F
#Block Obstruct= 2 , 0
                             9.6
Bank Sta=0,9.6
XS Rating Curve= 0
Exp/Cntr=.3,.1

Type RM Length L Ch R = 1 ,11      ,37,37,37
#Sta/Elev= 9
   -11.4    9.44    -1.4    9.44      -1    9.74       0    9.74     3.5    7.94
     5.5    7.94     7.8    9.74    10.1   10.94    20.1   10.94
#Mann= 3 , 0 , 0
   -11.4    .035       0       0    .035       0    10.1    .035       0
#XS Ineff= 2 , 0
               0      20    10.1              20
Permanent Ineff=
       F       F
#Block Obstruct= 2 , 0
                            10.1
Bank Sta=0,10.1
XS Rating Curve= 0
Exp/Cntr=.3,.1

Type RM Length L Ch R = 1 ,10.013  ,13,13,13
#Sta/Elev= 6
     -10    9.67       0    9.67       0    7.27     4.2    7.27     4.2    9.57
    14.2    9.57
#Mann= 3 , 0 , 0
     -10    .035       0       0    .035       0     4.2    .035       0
#XS Ineff= 2 , 0
               0      20     4.2              20
Permanent Ineff=
       F       F
#Block Obstruct= 2 , 0
                             4.2
Bank Sta=0,4.2
XS Rating Curve= 0
Exp/Cntr=.3,.1

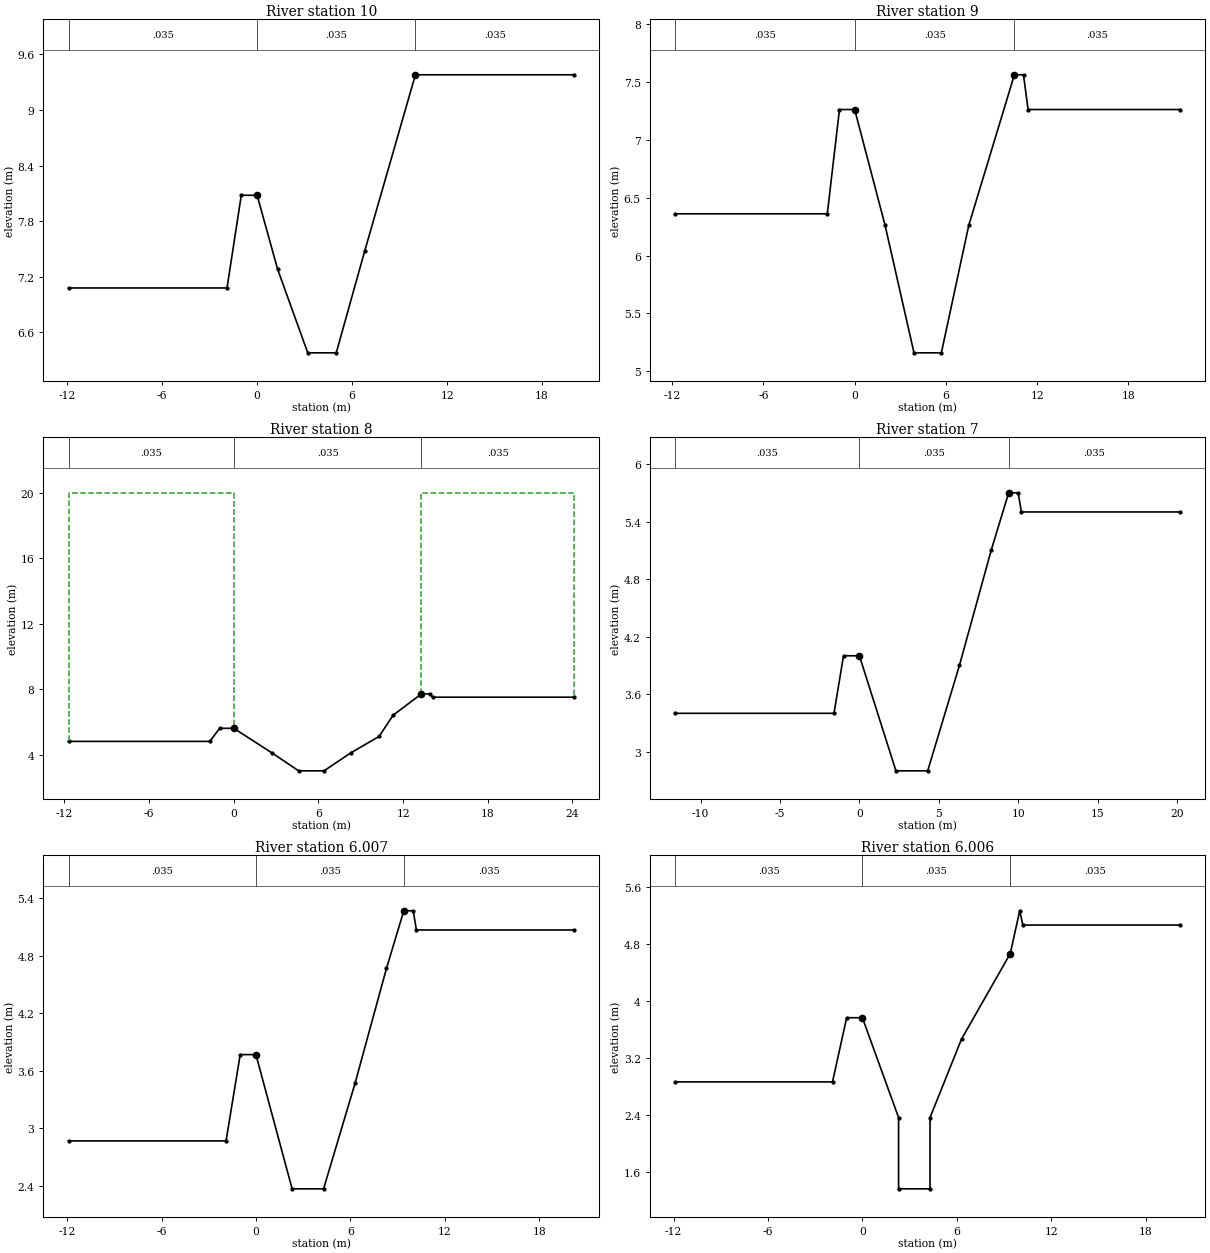
Type RM Length L Ch R = 1 ,10      ,50,50,50
#Sta/Elev= 10
   -11.9    7.08    -1.9    7.08      -1    8.08       0    8.08     1.3    7.28
     3.2    6.38       5    6.38     6.8    7.48      10    9.38      20    9.38
#Mann= 3 , 0 , 0
   -11.9    .035       0       0    .035       0      10    .035       0
#XS Ineff= 2 , 0
               0      20      10              20
Permanent Ineff=
       F       F
#Block Obstruct= 2 , 0
                              10
Bank Sta=0,10
XS Rating Curve= 0
Exp/Cntr=.3,.1

Type RM Length L Ch R = 1 ,9       ,50,50,50
#Sta/Elev= 12
   -11.8    6.36    -1.8    6.36      -1    7.26       0    7.26       2    6.26
     3.9    5.16     5.7    5.16     7.5    6.26    10.5    7.56    11.1    7.56
    11.4    7.26    21.4    7.26
#Mann= 3 , 0 , 0
   -11.8    .035       0       0    .035       0    10.5    .035       0
#XS Ineff= 2 , 0
       0       0      20    10.5       0      20
Permanent Ineff=
       F       F
#Block Obstruct= 2 , 0
                            10.5
Bank Sta=0,10.5
XS Rating Curve= 0
Exp/Cntr=.3,.1

Type RM Length L Ch R = 1 ,8       ,50,50,50
#Sta/Elev= 14
   -11.7    4.81    -1.7    4.81      -1    5.61       0    5.61     2.7    4.11
     4.6    3.01     6.4    3.01     8.3    4.11    10.3    5.11    11.3    6.41
    13.3    7.71    13.9    7.71    14.1    7.51    24.1    7.51
#Mann= 3 , 0 , 0
   -11.7    .035       0       0    .035       0    13.3    .035       0
#XS Ineff= 2 , 0
               0      20    13.3              20
Permanent Ineff=
       F       F
#Block Obstruct= 2 , 0
                            13.3
Bank Sta=0,13.3
XS Rating Curve= 0
Exp/Cntr=.3,.1

Type RM Length L Ch R = 1 ,7       ,43,43,43
#Sta/Elev= 12
   -11.6     3.4    -1.6     3.4      -1       4       0       4     2.3     2.8
     4.3     2.8     6.3     3.9     8.3     5.1     9.4     5.7      10     5.7
    10.2     5.5    20.2     5.5
#Mann= 3 , 0 , 0
   -11.6    .035       0       0    .035       0     9.4    .035       0
#XS Ineff= 2 , 0
       0       0      20     9.4       0      20
Permanent Ineff=
       F       F
#Block Obstruct= 2 , 0
                             9.4
Bank Sta=0,9.4
XS Rating Curve= 0
Exp/Cntr=.3,.1

Type RM Length L Ch R = 1 ,6.007   ,1,1,1
#Sta/Elev= 12
   -11.9    2.87    -1.9    2.87      -1    3.77       0    3.77     2.3    2.37
     4.3    2.37     6.3    3.47     8.3    4.67     9.4    5.27      10    5.27
    10.2    5.07    20.2    5.07
#Mann= 3 , 0 , 0
   -11.9    .035       0       0    .035       0     9.4    .035       0
#XS Ineff= 2 , 0
               0      20     9.4              20
Permanent Ineff=
       F       F
#Block Obstruct= 2 , 0
                             9.4
Bank Sta=0,9.4
XS Rating Curve= 0
Exp/Cntr=.3,.1

Type RM Length L Ch R = 1 ,6.006   ,6,6,6
#Sta/Elev= 13
   -11.9    2.87    -1.9    2.87      -1    3.77       0    3.77     2.3    2.37
     2.3    1.37     4.3    1.37     4.3    2.37     6.3    3.47     9.4    4.67
      10    5.27    10.2    5.07    20.2    5.07
#Mann= 3 , 0 , 0
   -11.9    .035       0       0    .035       0     9.4    .035       0
#XS Ineff= 2 , 0
               0      20     9.4              20
Permanent Ineff=
       F       F
#Block Obstruct= 2 , 0
                             9.4
Bank Sta=0,9.4
XS Rating Curve= 0
Exp/Cntr=.3,.1

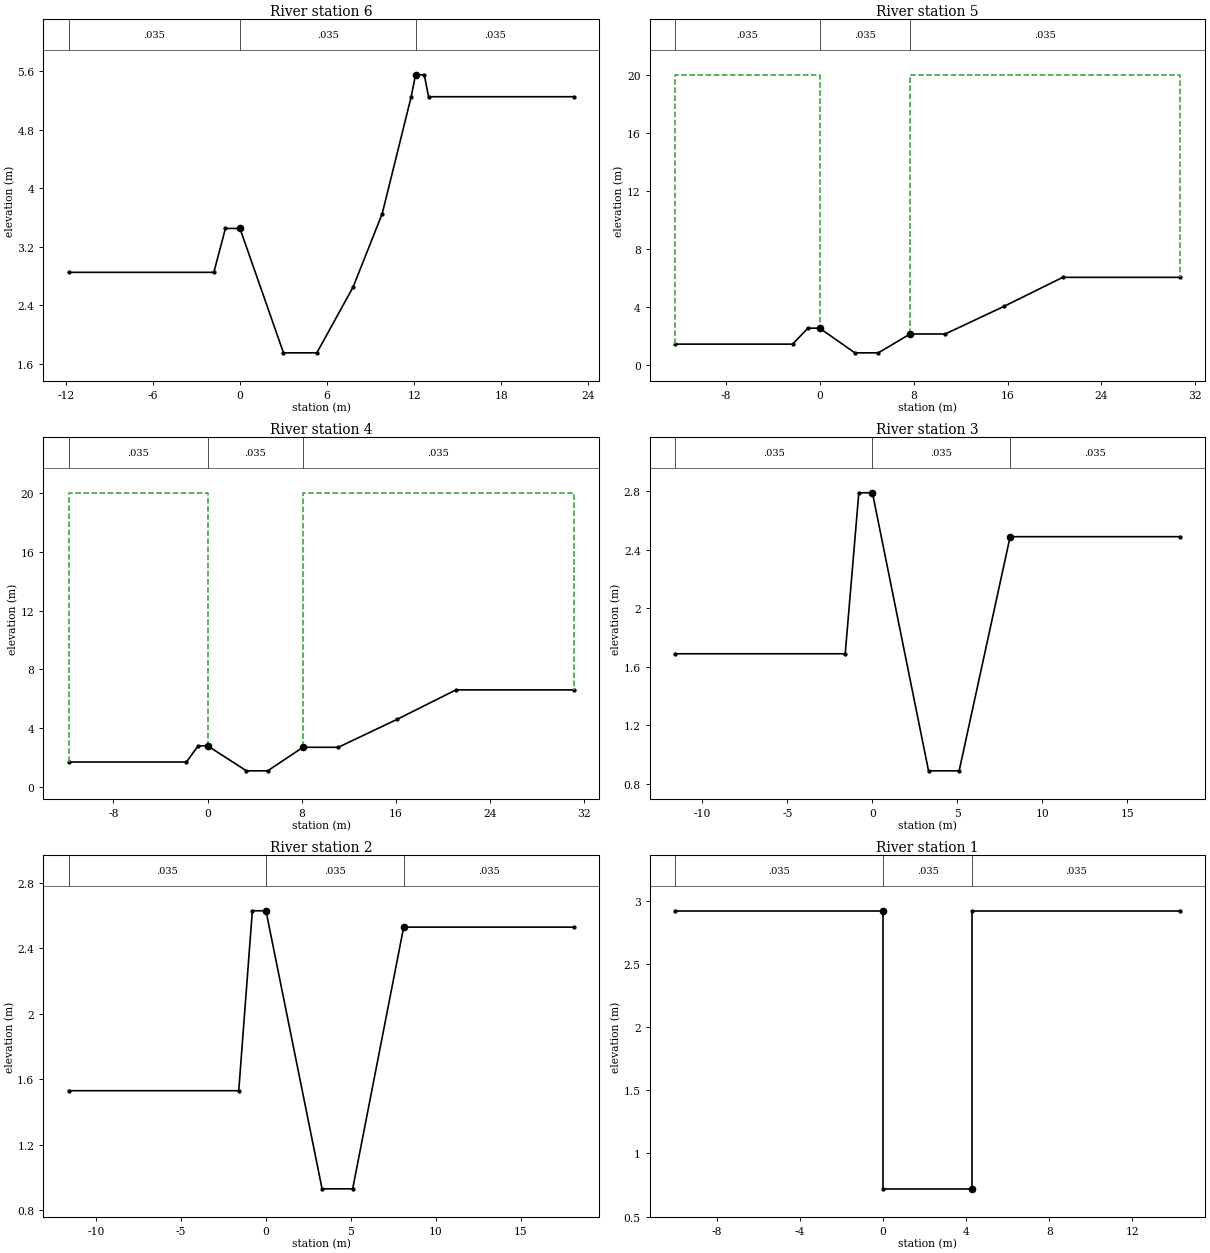
Type RM Length L Ch R = 1 ,6       ,50,50,50
#Sta/Elev= 13
   -11.8    2.85    -1.8    2.85      -1    3.45       0    3.45       3    1.75
     5.3    1.75     7.8    2.65     9.8    3.65    11.8    5.25    12.1    5.55
    12.7    5.55      13    5.25      23    5.25
#Mann= 3 , 0 , 0
   -11.8    .035       0       0    .035       0    12.1    .035       0
#XS Ineff= 2 , 0
               0      20    12.1              20
Permanent Ineff=
       F       F
#Block Obstruct= 2 , 0
                            12.1
Bank Sta=0,12.1
XS Rating Curve= 0
Exp/Cntr=.3,.1

Type RM Length L Ch R = 1 ,5       ,50,50,50
#Sta/Elev= 11
   -12.3    1.45    -2.3    1.45      -1    2.55       0    2.55       3     .85
       5     .85     7.7    2.15    10.7    2.15    15.7    4.05    20.7    6.05
    30.7    6.05
#Mann= 3 , 0 , 0
   -12.3    .035       0       0    .035       0     7.7    .035       0
#XS Ineff= 2 , 0
               0      20     7.7              20
Permanent Ineff=
       F       F
#Block Obstruct= 2 , 0
                             7.7
Bank Sta=0,7.7
XS Rating Curve= 0
Exp/Cntr=.3,.1

Type RM Length L Ch R = 1 ,4       ,50,50,50
#Sta/Elev= 11
   -11.8    1.71    -1.8    1.71     -.8    2.81       0    2.81     3.3    1.11
     5.1    1.11     8.1    2.71    11.1    2.71    16.1    4.61    21.1    6.61
    31.1    6.61
#Mann= 3 , 0 , 0
   -11.8    .035       0       0    .035       0     8.1    .035       0
#XS Ineff= 2 , 0
               0      20     8.1              20
Permanent Ineff=
       F       F
#Block Obstruct= 2 , 0
                             8.1
Bank Sta=0,8.1
XS Rating Curve= 0
Exp/Cntr=.3,.1

Type RM Length L Ch R = 1 ,3       ,50,50,50
#Sta/Elev= 8
   -11.6    1.69    -1.6    1.69     -.8    2.79       0    2.79     3.3     .89
     5.1     .89     8.1    2.49    18.1    2.49
#Mann= 3 , 0 , 0
   -11.6    .035       0       0    .035       0     8.1    .035       0
#XS Ineff= 2 , 0
               0      20     8.1              20
Permanent Ineff=
       F       F
#Block Obstruct= 2 , 0
                             8.1
Bank Sta=0,8.1
XS Rating Curve= 0
Exp/Cntr=.3,.1

Type RM Length L Ch R = 1 ,2       ,50,50,50
#Sta/Elev= 8
   -11.6    1.53    -1.6    1.53     -.8    2.63       0    2.63     3.3     .93
     5.1     .93     8.1    2.53    18.1    2.53
#Mann= 3 , 0 , 0
   -11.6    .035       0       0    .035       0     8.1    .035       0
#XS Ineff= 2 , 0
               0      20     8.1              20
Permanent Ineff=
       F       F
#Block Obstruct= 2 , 0
                             8.1
Bank Sta=0,8.1
XS Rating Curve= 0
Exp/Cntr=.3,.1

Type RM Length L Ch R = 1 ,1       ,2,2,2
#Sta/Elev= 6
     -10    2.92       0    2.92       0     .72     4.3     .72     4.3    2.92
    14.3    2.92
#Mann= 3 , 0 , 0
     -10    .035       0       0    .035       0     4.3    .035       0
#XS Ineff= 2 , 0
               0      20     4.3              20
Permanent Ineff=
       F       F
#Block Obstruct= 2 , 0
                             4.3
Bank Sta=0,4.3
XS Rating Curve= 0
Exp/Cntr=.3,.1

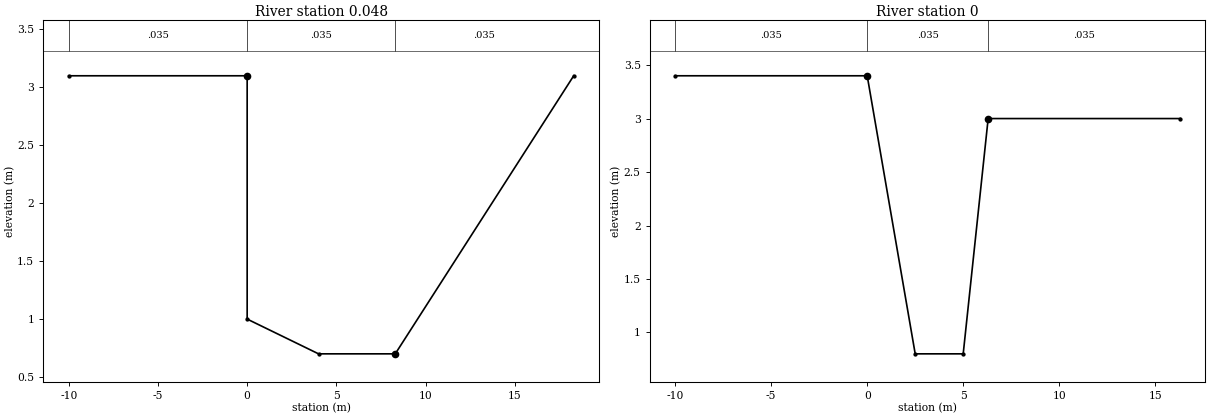
Type RM Length L Ch R = 1 ,0.048   ,48,48,48
#Sta/Elev= 6
     -10     3.1       0     3.1       0       1       4      .7     8.3      .7
    18.3     3.1
#Mann= 3 , 0 , 0
     -10    .035       0       0    .035       0     8.3    .035       0
#XS Ineff= 2 , 0
               0      20     8.3              20
Permanent Ineff=
       F       F
#Block Obstruct= 2 , 0
                             8.3
Bank Sta=0,8.3
XS Rating Curve= 0
Exp/Cntr=.3,.1

Type RM Length L Ch R = 1 ,0       ,0,0,0
#Sta/Elev= 6
     -10     3.4       0     3.4     2.5      .8       5      .8     6.3       3
    16.3       3
#Mann= 3 , 0 , 0
     -10    .035       0       0    .035       0     6.3    .035       0
#XS Ineff= 2 , 0
               0      20     6.3              20
Permanent Ineff=
       F       F
#Block Obstruct= 2 , 0
                             6.3
Bank Sta=0,6.3
XS Rating Curve= 0
Exp/Cntr=.3,.1

Chan Stop Cuts=-1