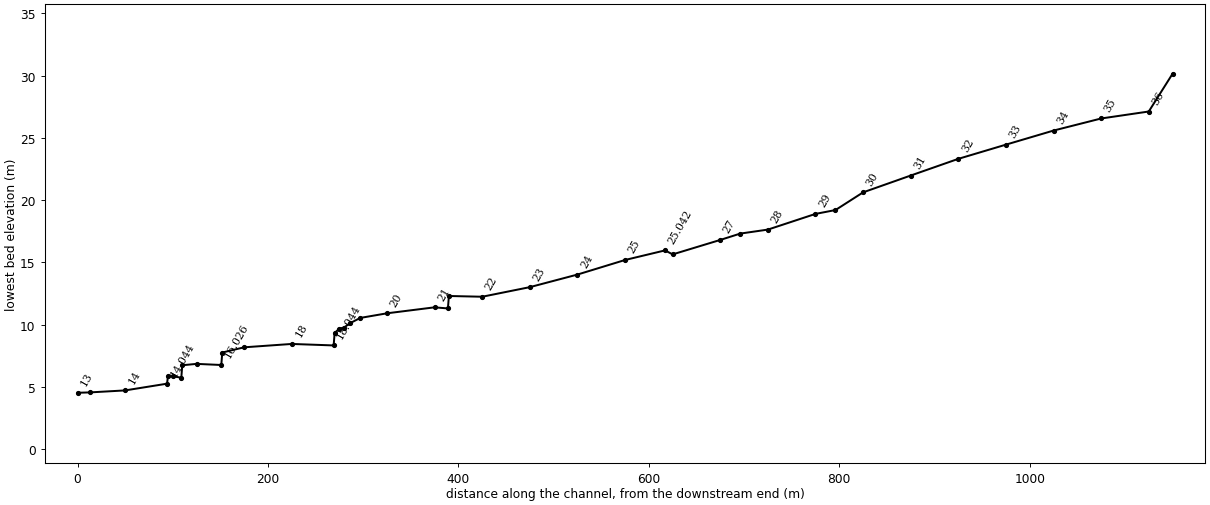
--- PMC.prj (project) ---

Proj Title=PANMUN
Current Plan=p01
Default Exp/Contr=.3,.1
SI Units
Geom File=g01
Flow File=f01
Plan File=p01
Y Axis Title=Elevation
X Axis Title(PF)=Main Channel Distance
X Axis Title(XS)=Station
BEGIN DESCRIPTION:
           BACK WATER COMPUTATION
      APPLICATION OF HEC-2 BY Samju Construction Engineering
      panmoon-ch: 10,20,30,50,80 yr
END DESCRIPTION:
DSS Export Rating Curves= 0
DSS Export Rating Curve Sorted= 0
DSS Export Volume Flow Curves= 0
DXF OffsetX= 0
DXF OffsetY= 0
DXF ScaleX= 1
DXF ScaleY= 10

--- PMC.p01 (plan) ---

Plan Title=Imported Plan 01
Version=Version 3.0.1  Mar 2001
Short Identifier=Imported Pla
Geom File=g01
Flow File=f01
Subcritical Flow
K Sum by GR= 0
Std Step Tol= 0.003
Critical Tol= 0.003
Num of Std Step Trials= 20
Max Error Tol= 0.1
Flow Tol Ratio= 0.001
Split Flow NTrial= 30
Split Flow Tol= 0.02
Split Flow Ratio= 0.02
Log Output Level= 0
Friction Slope Method= 1
Unsteady Friction Slope Method= 2
Parabolic Critical Depth
Global Vel Dist= 0 , 0 , 0
Global Log Level= 0
CheckData=True
Encroach Param=-1 ,0,0, 0
Computation Interval=1HOUR
Output Interval=1HOUR
Run HTab= 0
Run UNet= 0
Run PostProcess= 0
UNET Theta= 1
UNET ZTol= 0.02
UNET ZSATol= 0.1
UNET MxIter= 20
UNET MaxInSteps= 20
UNET DtIC= 0
UNET DtMin= 0
UNET MaxCRTS= 20
UNET WFStab= 2
UNET SFStab= 1
UNET WFX= 1
UNET SFX= 1
UNET Convert EG Bridges=-1
UNET Use Existing IB Tables=-1
Instantaneous Interval=1HOUR
Write IC File= 0
Write Velocity= 0
Write Detailed= 0

--- PMC.f01 (steady flow) ---

Flow Title=Imported Flow 01
Version=Version 3.0.1  Mar 2001
Number of Profiles= 5
Profile Names=10YR,20RY,30YR,50YR,80YR
River Rch & RM=RIVER-1,Reach-1         ,36.025
   13.37   14.73   15.52   16.53   17.45
River Rch & RM=RIVER-1,Reach-1         ,17
   19.04   20.98   22.12   23.55   24.87
River Rch & RM=PANMUN,PANMUN          ,36.025
   13.37   14.73   15.52   16.53   17.45
River Rch & RM=PANMUN,PANMUN          ,17
   19.04   20.98   22.12   23.55   24.87
Boundary for River Rch & Prof#=PANMUN,PANMUN          , 1
Up Type= 0
Dn Type= 3
Dn Slope=.016
Boundary for River Rch & Prof#=PANMUN,PANMUN          , 2
Up Type= 0
Dn Type= 3
Dn Slope=.016
Boundary for River Rch & Prof#=PANMUN,PANMUN          , 3
Up Type= 0
Dn Type= 3
Dn Slope=.016
Boundary for River Rch & Prof#=PANMUN,PANMUN          , 4
Up Type= 0
Dn Type= 3
Dn Slope=.016
Boundary for River Rch & Prof#=PANMUN,PANMUN          , 5
Up Type= 0
Dn Type= 3
Dn Slope=.016
DSS Import GetInterval= 0
DSS Import GetPeak= 0
DSS Import FillOption= 0

--- PMC.g01 (geometry) ---

Geom Title=Imported Geom 01
Version=Version 3.0.1  Mar 2001

River Reach=PANMUN          ,PANMUN
Reach XY= 2
              .5             .95              .5             .05

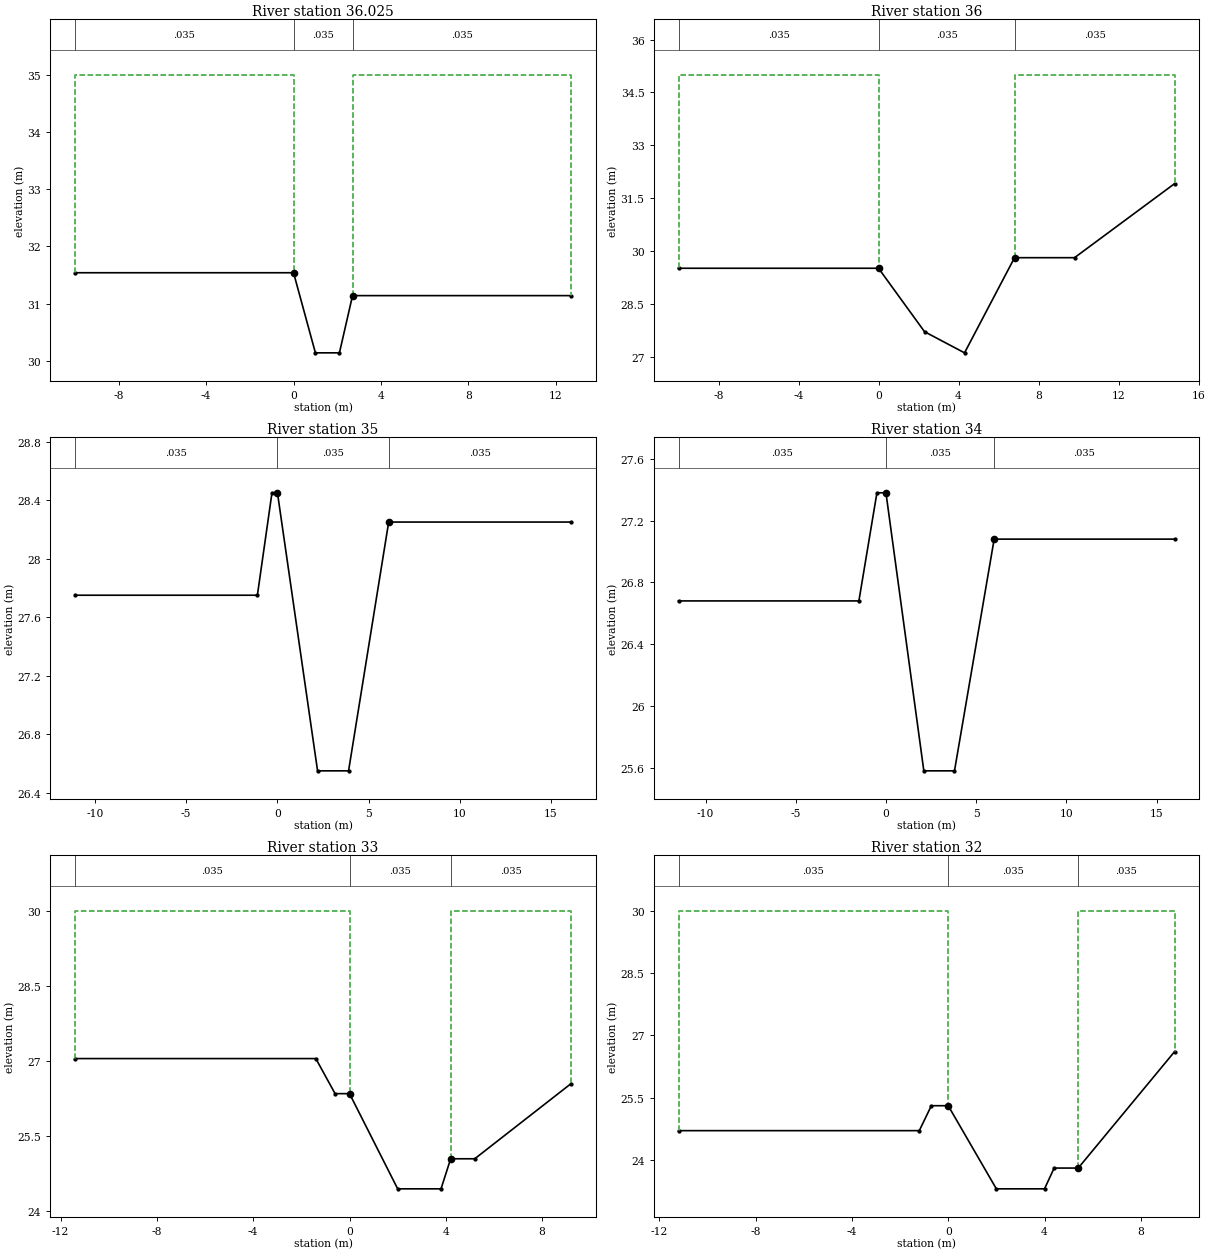
Type RM Length L Ch R = 1 ,36.025  ,25,25,25
#Sta/Elev= 6
     -10   31.54       0   31.54       1   30.14     2.1   30.14     2.7   31.14
    12.7   31.14
#Mann= 3 , 0 , 0
     -10    .035       0       0    .035       0     2.7    .035       0
#XS Ineff= 2 , 0
               0      35     2.7              35
Permanent Ineff=
       F       F
#Block Obstruct= 2 , 0
                             2.7
Bank Sta=0,2.7
XS Rating Curve= 0
Exp/Cntr=.3,.1

Type RM Length L Ch R = 1 ,36      ,50,50,50
#Sta/Elev= 7
     -10   29.51       0   29.51     2.3   27.71     4.3   27.11     6.8   29.81
     9.8   29.81    14.8   31.91
#Mann= 3 , 0 , 0
     -10    .035       0       0    .035       0     6.8    .035       0
#XS Ineff= 2 , 0
               0      35     6.8              35
Permanent Ineff=
       F       F
#Block Obstruct= 2 , 0
                             6.8
Bank Sta=0,6.8
XS Rating Curve= 0
Exp/Cntr=.3,.1

Type RM Length L Ch R = 1 ,35      ,50,50,50
#Sta/Elev= 8
   -11.1   27.75    -1.1   27.75     -.3   28.45       0   28.45     2.2   26.55
     3.9   26.55     6.1   28.25    16.1   28.25
#Mann= 3 , 0 , 0
   -11.1    .035       0       0    .035       0     6.1    .035       0
#XS Ineff= 2 , 0
               0      35     6.1              35
Permanent Ineff=
       F       F
#Block Obstruct= 2 , 0
                             6.1
Bank Sta=0,6.1
XS Rating Curve= 0
Exp/Cntr=.3,.1

Type RM Length L Ch R = 1 ,34      ,50,50,50
#Sta/Elev= 8
   -11.5   26.68    -1.5   26.68     -.5   27.38       0   27.38     2.1   25.58
     3.8   25.58       6   27.08      16   27.08
#Mann= 3 , 0 , 0
   -11.5    .035       0       0    .035       0       6    .035       0
#XS Ineff= 2 , 0
               0      35       6              35
Permanent Ineff=
       F       F
#Block Obstruct= 2 , 0
                               6
Bank Sta=0,6
XS Rating Curve= 0
Exp/Cntr=.3,.1

Type RM Length L Ch R = 1 ,33      ,50,50,50
#Sta/Elev= 9
   -11.4   27.05    -1.4   27.05     -.6   26.35       0   26.35       2   24.45
     3.8   24.45     4.2   25.05     5.2   25.05     9.2   26.55
#Mann= 3 , 0 , 0
   -11.4    .035       0       0    .035       0     4.2    .035       0
#XS Ineff= 2 , 0
               0      30     4.2              30
Permanent Ineff=
       F       F
#Block Obstruct= 2 , 0
                             4.2
Bank Sta=0,4.2
XS Rating Curve= 0
Exp/Cntr=.3,.1

Type RM Length L Ch R = 1 ,32      ,50,50,50
#Sta/Elev= 9
   -11.2   24.71    -1.2   24.71     -.7   25.31       0   25.31       2   23.31
       4   23.31     4.4   23.81     5.4   23.81     9.4   26.61
#Mann= 3 , 0 , 0
   -11.2    .035       0       0    .035       0     5.4    .035       0
#XS Ineff= 2 , 0
               0      30     5.4              30
Permanent Ineff=
       F       F
#Block Obstruct= 2 , 0
                             5.4
Bank Sta=0,5.4
XS Rating Curve= 0
Exp/Cntr=.3,.1

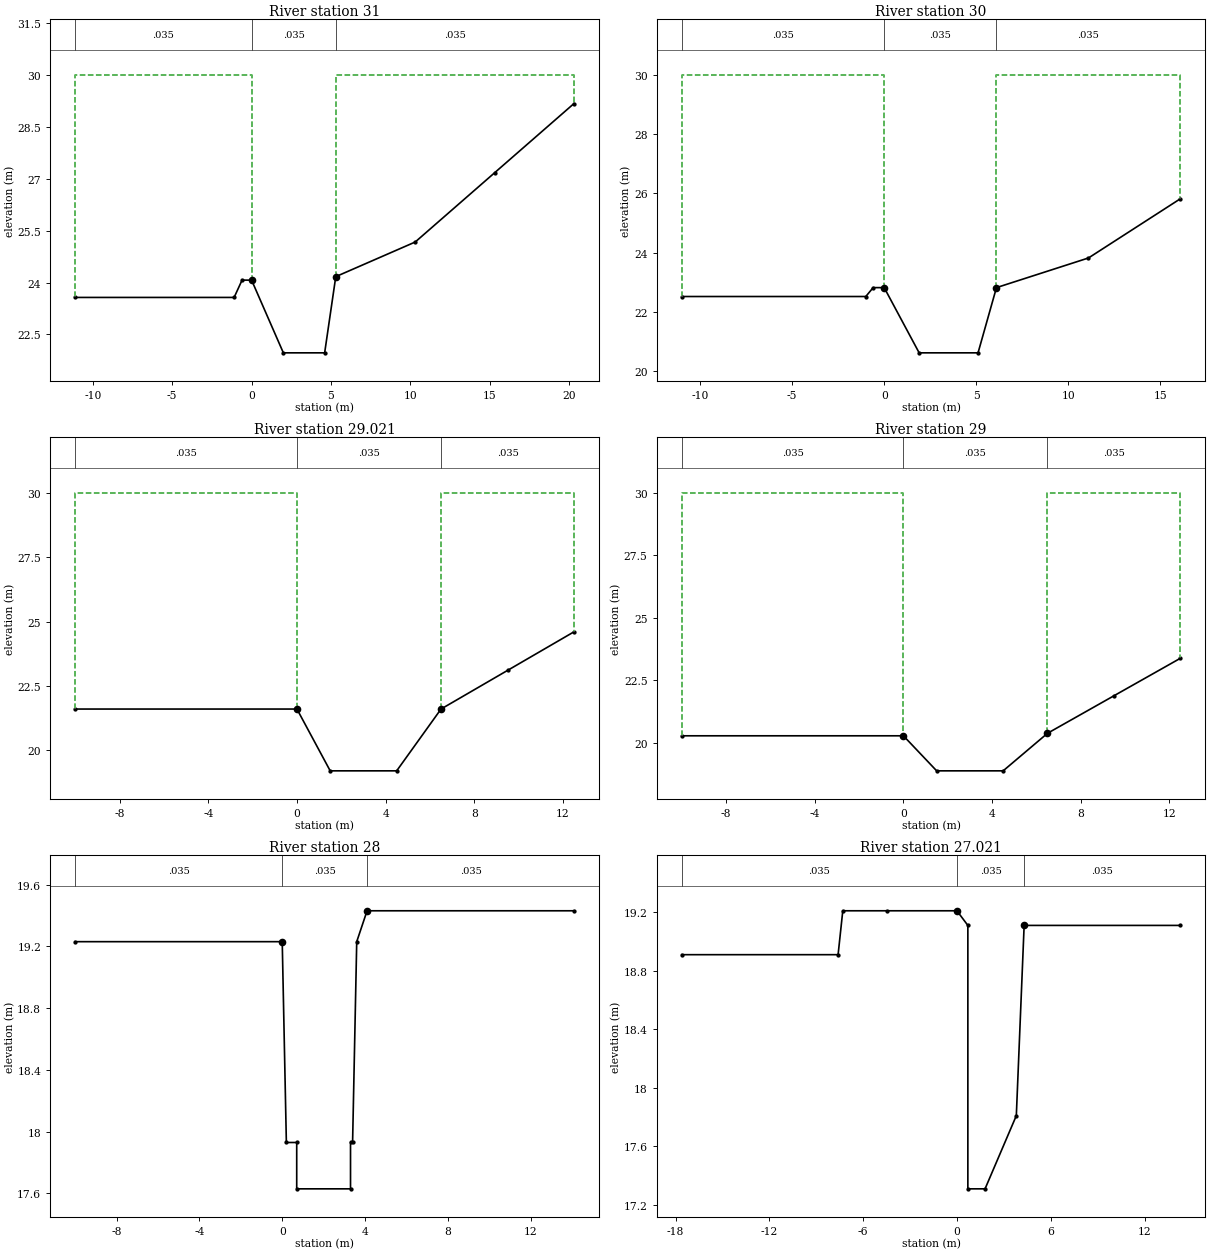
Type RM Length L Ch R = 1 ,31      ,50,50,50
#Sta/Elev= 10
   -11.1   23.57    -1.1   23.57     -.6   24.07       0   24.07       2   21.97
     4.6   21.97     5.3   24.17    10.3   25.17    15.3   27.17    20.3   29.17
#Mann= 3 , 0 , 0
   -11.1    .035       0       0    .035       0     5.3    .035       0
#XS Ineff= 2 , 0
               0      30     5.3              30
Permanent Ineff=
       F       F
#Block Obstruct= 2 , 0
                             5.3
Bank Sta=0,5.3
XS Rating Curve= 0
Exp/Cntr=.3,.1

Type RM Length L Ch R = 1 ,30      ,29,29,29
#Sta/Elev= 9
     -11   22.52      -1   22.52     -.6   22.82       0   22.82     1.9   20.62
     5.1   20.62     6.1   22.82    11.1   23.82    16.1   25.82
#Mann= 3 , 0 , 0
     -11    .035       0       0    .035       0     6.1    .035       0
#XS Ineff= 2 , 0
               0      30     6.1              30
Permanent Ineff=
       F       F
#Block Obstruct= 2 , 0
                             6.1
Bank Sta=0,6.1
XS Rating Curve= 0
Exp/Cntr=.3,.1

Type RM Length L Ch R = 1 ,29.021  ,21,21,21
#Sta/Elev= 7
     -10    21.6       0    21.6     1.5    19.2     4.5    19.2     6.5    21.6
     9.5    23.1    12.5    24.6
#Mann= 3 , 0 , 0
     -10    .035       0       0    .035       0     6.5    .035       0
#XS Ineff= 2 , 0
               0      30     6.5              30
Permanent Ineff=
       F       F
#Block Obstruct= 2 , 0
                             6.5
Bank Sta=0,6.5
XS Rating Curve= 0
Exp/Cntr=.3,.1

Type RM Length L Ch R = 1 ,29      ,50,50,50
#Sta/Elev= 7
     -10   20.29       0   20.29     1.5   18.89     4.5   18.89     6.5   20.39
     9.5   21.89    12.5   23.39
#Mann= 3 , 0 , 0
     -10    .035       0       0    .035       0     6.5    .035       0
#XS Ineff= 2 , 0
               0      30     6.5              30
Permanent Ineff=
       F       F
#Block Obstruct= 2 , 0
                             6.5
Bank Sta=0,6.5
XS Rating Curve= 0
Exp/Cntr=.3,.1

Type RM Length L Ch R = 1 ,28      ,29,29,29
#Sta/Elev= 11
     -10   19.23       0   19.23      .2   17.93      .7   17.93      .7   17.63
     3.3   17.63     3.3   17.93     3.4   17.93     3.6   19.23     4.1   19.43
    14.1   19.43
#Mann= 3 , 0 , 0
     -10    .035       0       0    .035       0     4.1    .035       0
#XS Ineff= 2 , 0
               0      30     4.1              30
Permanent Ineff=
       F       F
#Block Obstruct= 2 , 0
                             4.1
Bank Sta=0,4.1
XS Rating Curve= 0
Exp/Cntr=.3,.1

Type RM Length L Ch R = 1 ,27.021  ,21,21,21
#Sta/Elev= 11
   -17.6   18.91    -7.6   18.91    -7.3   19.21    -4.5   19.21       0   19.21
      .7   19.11      .7   17.31     1.8   17.31     3.8   17.81     4.3   19.11
    14.3   19.11
#Mann= 3 , 0 , 0
   -17.6    .035       0       0    .035       0     4.3    .035       0
#XS Ineff= 2 , 0
               0      30     4.3              30
Permanent Ineff=
       F       F
#Block Obstruct= 2 , 0
                             4.3
Bank Sta=0,4.3
XS Rating Curve= 0
Exp/Cntr=.3,.1

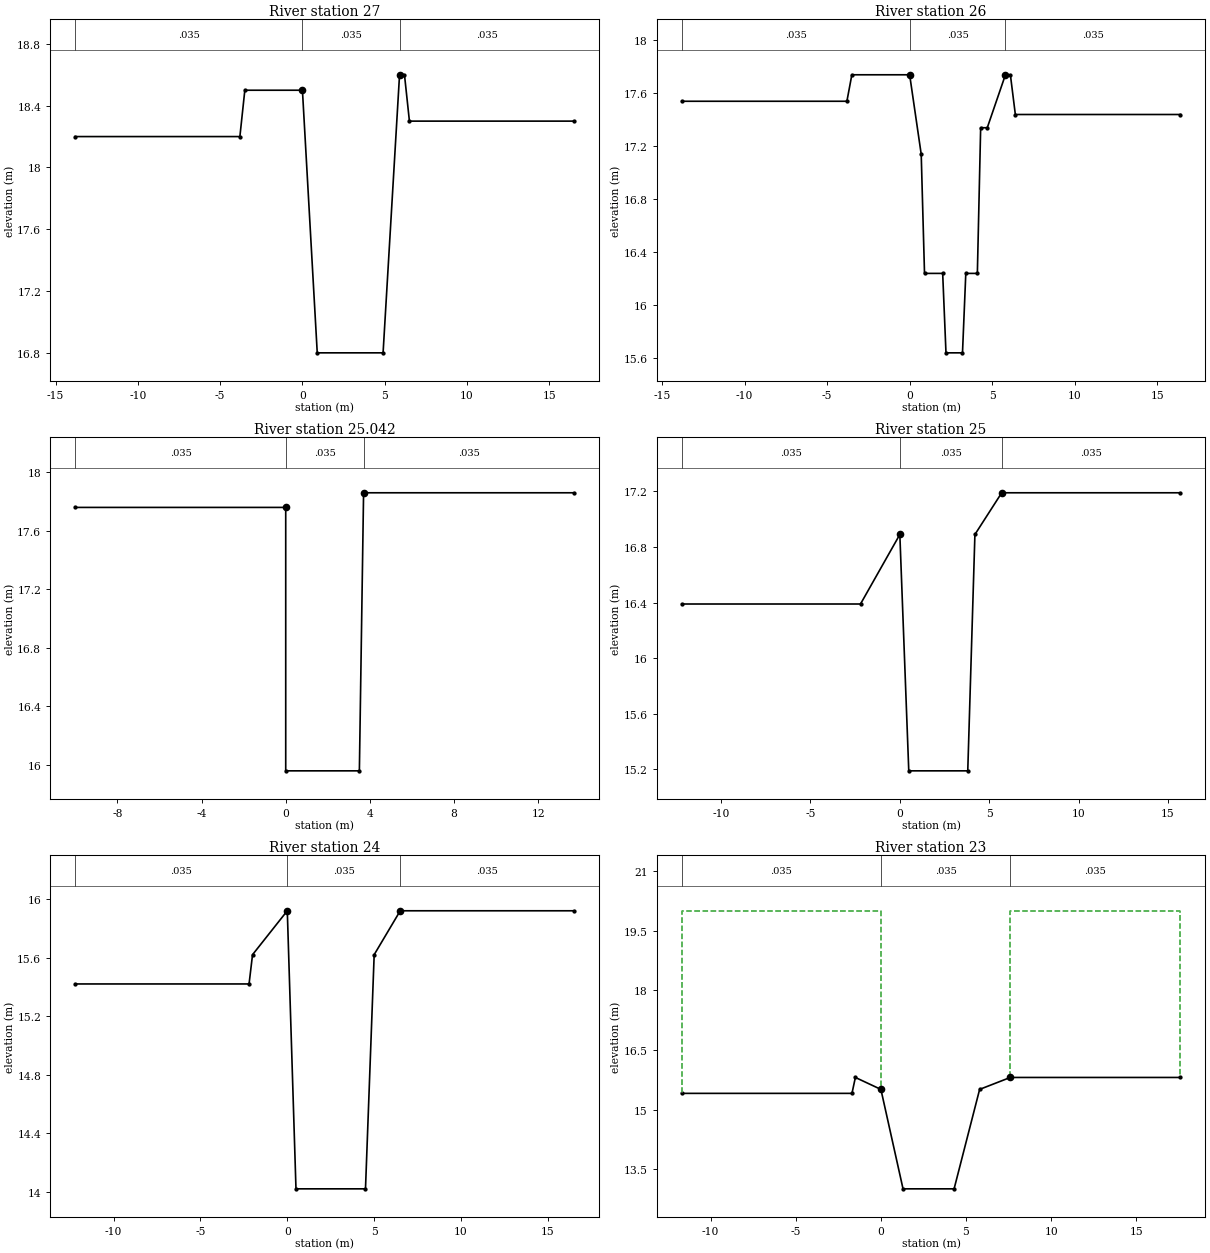
Type RM Length L Ch R = 1 ,27      ,50,50,50
#Sta/Elev= 10
   -13.8    18.2    -3.8    18.2    -3.5    18.5       0    18.5      .9    16.8
     4.9    16.8     5.9    18.6     6.2    18.6     6.5    18.3    16.5    18.3
#Mann= 3 , 0 , 0
   -13.8    .035       0       0    .035       0     5.9    .035       0
#XS Ineff= 2 , 0
               0      30     5.9              30
Permanent Ineff=
       F       F
#Block Obstruct= 2 , 0
                             5.9
Bank Sta=0,5.9
XS Rating Curve= 0
Exp/Cntr=.3,.1

Type RM Length L Ch R = 1 ,26      ,8,8,8
#Sta/Elev= 17
   -13.8   17.54    -3.8   17.54    -3.5   17.74       0   17.74      .7   17.14
      .9   16.24       2   16.24     2.2   15.64     3.2   15.64     3.4   16.24
     4.1   16.24     4.3   17.34     4.7   17.34     5.8   17.74     6.1   17.74
     6.4   17.44    16.4   17.44
#Mann= 3 , 0 , 0
   -13.8    .035       0       0    .035       0     5.8    .035       0
#XS Ineff= 2 , 0
               0      30     5.8              30
Permanent Ineff=
       F       F
#Block Obstruct= 2 , 0
                             5.8
Bank Sta=0,5.8
XS Rating Curve= 0
Exp/Cntr=.3,.1

Type RM Length L Ch R = 1 ,25.042  ,42,42,42
#Sta/Elev= 6
     -10   17.76       0   17.76       0   15.96     3.5   15.96     3.7   17.86
    13.7   17.86
#Mann= 3 , 0 , 0
     -10    .035       0       0    .035       0     3.7    .035       0
#XS Ineff= 2 , 0
               0      30     3.7              30
Permanent Ineff=
       F       F
#Block Obstruct= 2 , 0
                             3.7
Bank Sta=0,3.7
XS Rating Curve= 0
Exp/Cntr=.3,.1

Type RM Length L Ch R = 1 ,25      ,50,50,50
#Sta/Elev= 8
   -12.2   16.39    -2.2   16.39       0   16.89      .5   15.19     3.8   15.19
     4.2   16.89     5.7   17.19    15.7   17.19
#Mann= 3 , 0 , 0
   -12.2    .035       0       0    .035       0     5.7    .035       0
#XS Ineff= 2 , 0
               0      30     5.7              30
Permanent Ineff=
       F       F
#Block Obstruct= 2 , 0
                             5.7
Bank Sta=0,5.7
XS Rating Curve= 0
Exp/Cntr=.3,.1

Type RM Length L Ch R = 1 ,24      ,50,50,50
#Sta/Elev= 9
   -12.2   15.42    -2.2   15.42      -2   15.62       0   15.92      .5   14.02
     4.5   14.02       5   15.62     6.5   15.92    16.5   15.92
#Mann= 3 , 0 , 0
   -12.2    .035       0       0    .035       0     6.5    .035       0
#XS Ineff= 2 , 0
               0      25     6.5              25
Permanent Ineff=
       F       F
#Block Obstruct= 2 , 0
                             6.5
Bank Sta=0,6.5
XS Rating Curve= 0
Exp/Cntr=.3,.1

Type RM Length L Ch R = 1 ,23      ,50,50,50
#Sta/Elev= 9
   -11.7   15.41    -1.7   15.41    -1.5   15.81       0   15.51     1.3   13.01
     4.3   13.01     5.8   15.51     7.6   15.81    17.6   15.81
#Mann= 3 , 0 , 0
   -11.7    .035       0       0    .035       0     7.6    .035       0
#XS Ineff= 2 , 0
               0      20     7.6              20
Permanent Ineff=
       F       F
#Block Obstruct= 2 , 0
                             7.6
Bank Sta=0,7.6
XS Rating Curve= 0
Exp/Cntr=.3,.1

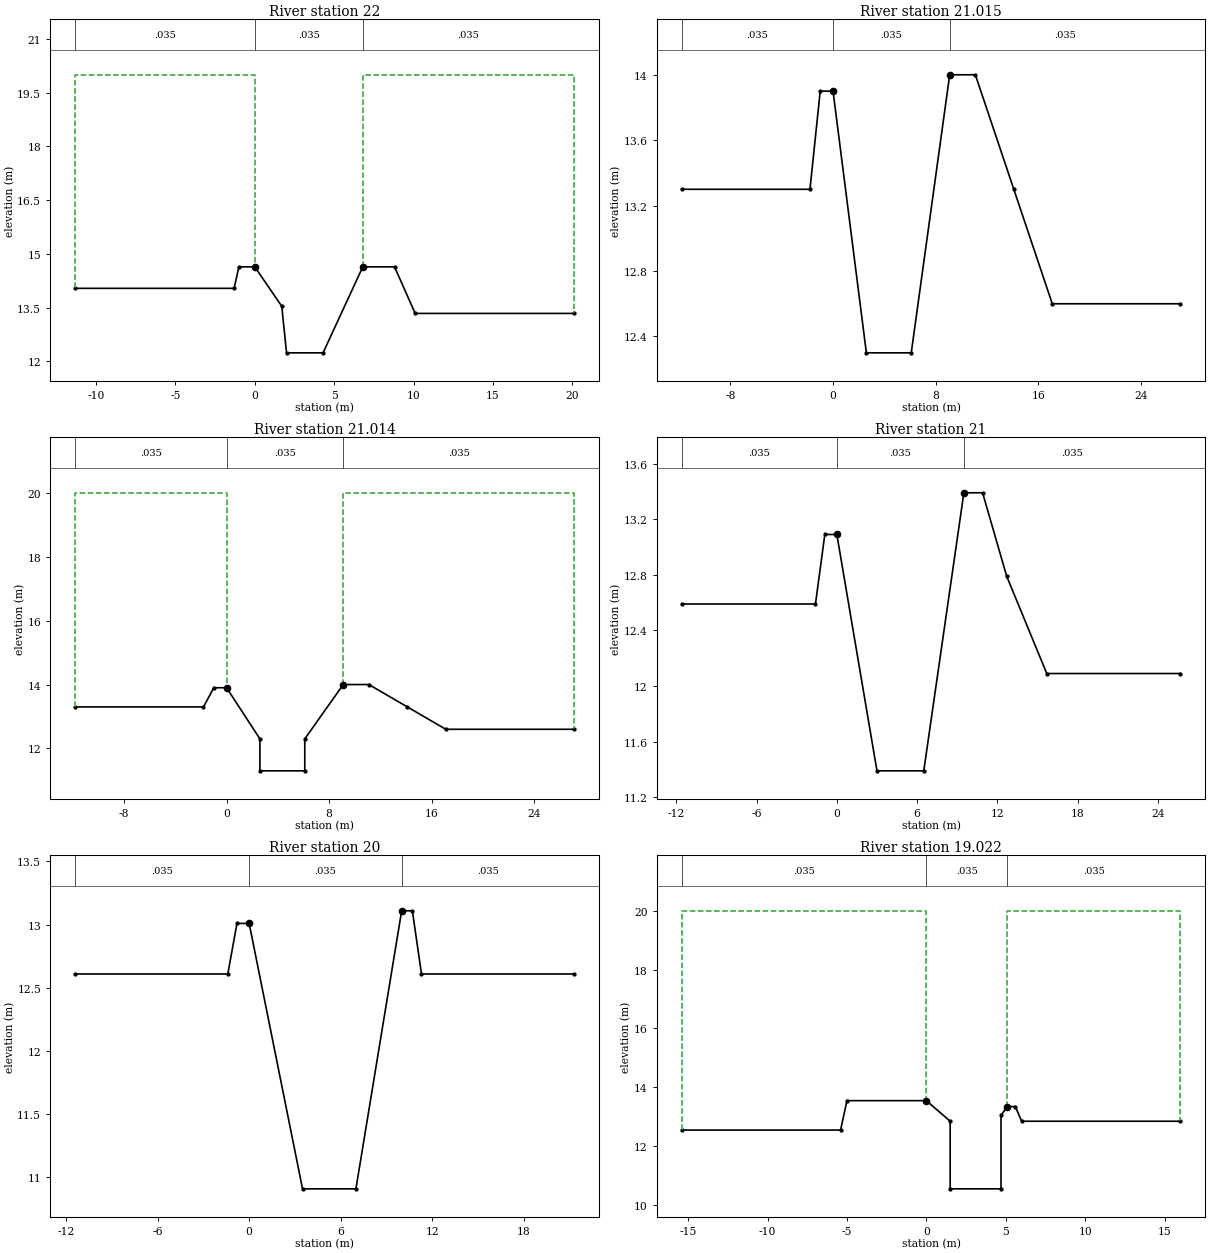
Type RM Length L Ch R = 1 ,22      ,35,35,35
#Sta/Elev= 11
   -11.3   14.04    -1.3   14.04      -1   14.64       0   14.64     1.7   13.54
       2   12.24     4.3   12.24     6.8   14.64     8.8   14.64    10.1   13.34
    20.1   13.34
#Mann= 3 , 0 , 0
   -11.3    .035       0       0    .035       0     6.8    .035       0
#XS Ineff= 2 , 0
               0      20     6.8              20
Permanent Ineff=
       F       F
#Block Obstruct= 2 , 0
                             6.8
Bank Sta=0,6.8
XS Rating Curve= 0
Exp/Cntr=.3,.1

Type RM Length L Ch R = 1 ,21.015  ,1,1,1
#Sta/Elev= 11
   -11.8    13.3    -1.8    13.3      -1    13.9       0    13.9     2.6    12.3
     6.1    12.3     9.1      14    11.1      14    14.1    13.3    17.1    12.6
    27.1    12.6
#Mann= 3 , 0 , 0
   -11.8    .035       0       0    .035       0     9.1    .035       0
#XS Ineff= 2 , 0
               0      20     9.1              20
Permanent Ineff=
       F       F
#Block Obstruct= 2 , 0
                             9.1
Bank Sta=0,9.1
XS Rating Curve= 0
Exp/Cntr=.3,.1

Type RM Length L Ch R = 1 ,21.014  ,14,14,14
#Sta/Elev= 13
   -11.8    13.3    -1.8    13.3      -1    13.9       0    13.9     2.6    12.3
     2.6    11.3     6.1    11.3     6.1    12.3     9.1      14    11.1      14
    14.1    13.3    17.1    12.6    27.1    12.6
#Mann= 3 , 0 , 0
   -11.8    .035       0       0    .035       0     9.1    .035       0
#XS Ineff= 2 , 0
               0      20     9.1              20
Permanent Ineff=
       F       F
#Block Obstruct= 2 , 0
                             9.1
Bank Sta=0,9.1
XS Rating Curve= 0
Exp/Cntr=.3,.1

Type RM Length L Ch R = 1 ,21      ,50,50,50
#Sta/Elev= 11
   -11.6   12.59    -1.6   12.59     -.9   13.09       0   13.09       3   11.39
     6.5   11.39     9.5   13.39    10.9   13.39    12.7   12.79    15.7   12.09
    25.7   12.09
#Mann= 3 , 0 , 0
   -11.6    .035       0       0    .035       0     9.5    .035       0
#XS Ineff= 2 , 0
               0      20     9.5              20
Permanent Ineff=
       F       F
#Block Obstruct= 2 , 0
                             9.5
Bank Sta=0,9.5
XS Rating Curve= 0
Exp/Cntr=.3,.1

Type RM Length L Ch R = 1 ,20      ,28,28,28
#Sta/Elev= 10
   -11.4   12.61    -1.4   12.61     -.8   13.01       0   13.01     3.5   10.91
       7   10.91      10   13.11    10.7   13.11    11.3   12.61    21.3   12.61
#Mann= 3 , 0 , 0
   -11.4    .035       0       0    .035       0      10    .035       0
#XS Ineff= 2 , 0
               0      20      10              20
Permanent Ineff=
       F       F
#Block Obstruct= 2 , 0
                              10
Bank Sta=0,10
XS Rating Curve= 0
Exp/Cntr=.3,.1

Type RM Length L Ch R = 1 ,19.022  ,11,11,11
#Sta/Elev= 12
   -15.4   12.54    -5.4   12.54      -5   13.54       0   13.54     1.5   12.84
     1.5   10.54     4.7   10.54     4.7   13.04     5.1   13.34     5.6   13.34
       6   12.84      16   12.84
#Mann= 3 , 0 , 0
   -15.4    .035       0       0    .035       0     5.1    .035       0
#XS Ineff= 2 , 0
               0      20     5.1              20
Permanent Ineff=
       F       F
#Block Obstruct= 2 , 0
                             5.1
Bank Sta=0,5.1
XS Rating Curve= 0
Exp/Cntr=.3,.1

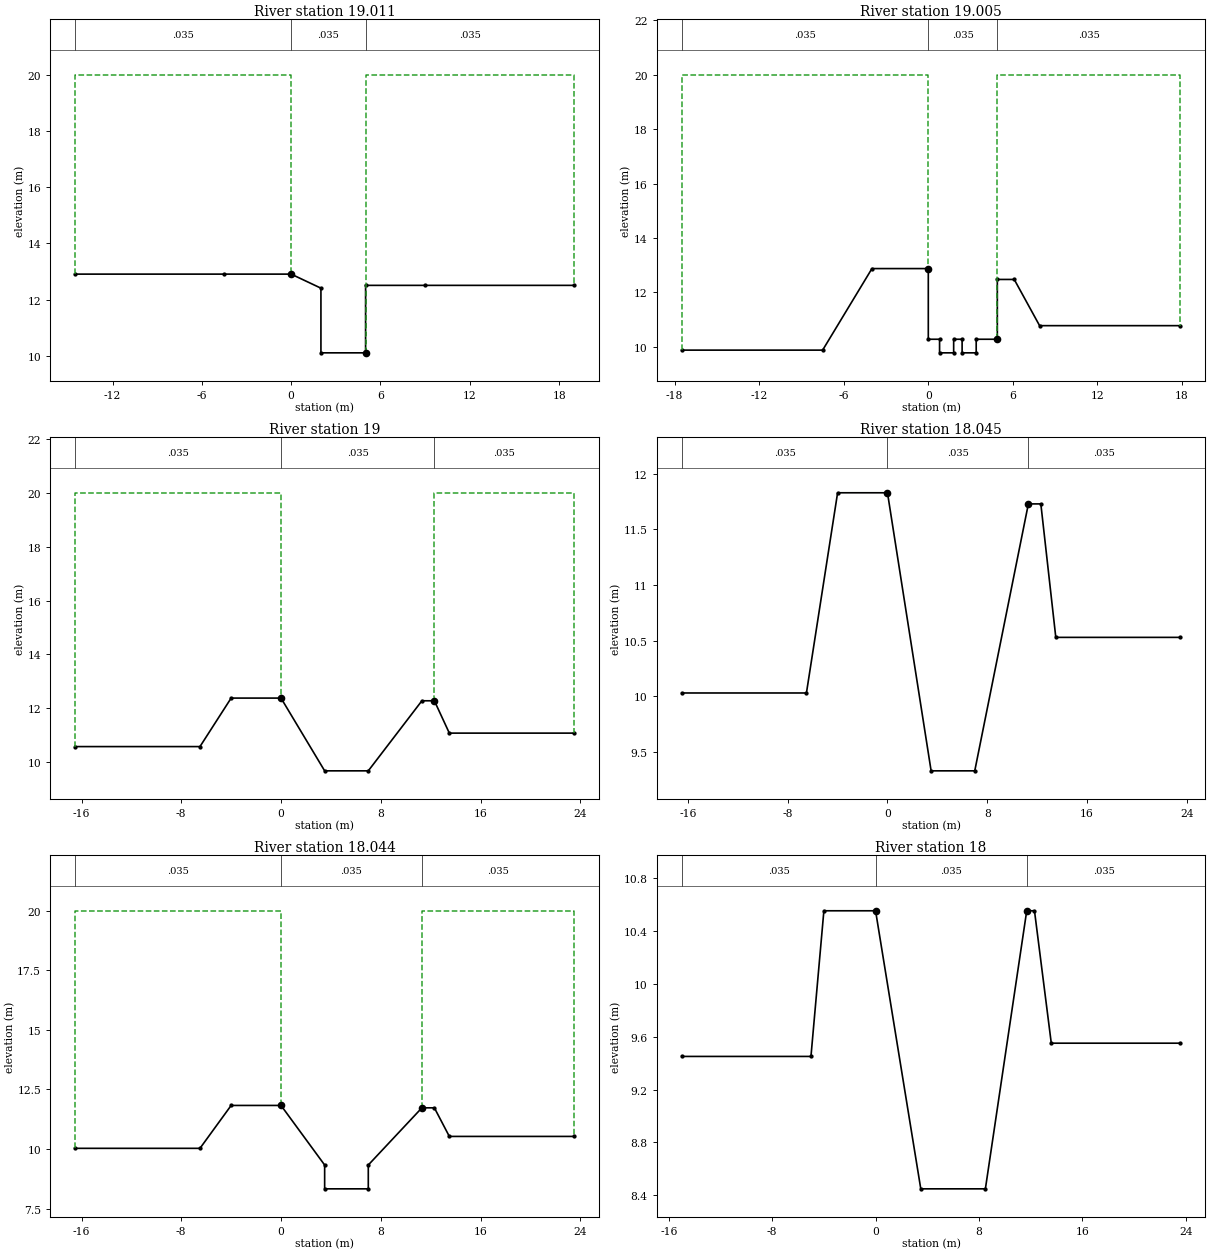
Type RM Length L Ch R = 1 ,19.011  ,6,6,6
#Sta/Elev= 9
   -14.5   12.91    -4.5   12.91       0   12.91       2   12.41       2   10.11
       5   10.11       5   12.51       9   12.51      19   12.51
#Mann= 3 , 0 , 0
   -14.5    .035       0       0    .035       0       5    .035       0
#XS Ineff= 2 , 0
               0      20       5              20
Permanent Ineff=
       F       F
#Block Obstruct= 2 , 0
                               5
Bank Sta=0,5
XS Rating Curve= 0
Exp/Cntr=.3,.1

Type RM Length L Ch R = 1 ,19.005  ,5,5,5
#Sta/Elev= 18
   -17.5    9.87    -7.5    9.87      -4   12.87       0   12.87       0   10.27
      .8   10.27      .8    9.77     1.8    9.77     1.8   10.27     2.4   10.27
     2.4    9.77     3.4    9.77     3.4   10.27     4.9   10.27     4.9   12.47
     6.1   12.47     7.9   10.77    17.9   10.77
#Mann= 3 , 0 , 0
   -17.5    .035       0       0    .035       0     4.9    .035       0
#XS Ineff= 2 , 0
               0      20     4.9              20
Permanent Ineff=
       F       F
#Block Obstruct= 2 , 0
                             4.9
Bank Sta=0,4.9
XS Rating Curve= 0
Exp/Cntr=.3,.1

Type RM Length L Ch R = 1 ,19      ,5,5,5
#Sta/Elev= 10
   -16.5   10.58    -6.5   10.58      -4   12.38       0   12.38     3.5    9.68
       7    9.68    11.3   12.28    12.3   12.28    13.5   11.08    23.5   11.08
#Mann= 3 , 0 , 0
   -16.5    .035       0       0    .035       0    12.3    .035       0
#XS Ineff= 2 , 0
               0      20    12.3              20
Permanent Ineff=
       F       F
#Block Obstruct= 2 , 0
                            12.3
Bank Sta=0,12.3
XS Rating Curve= 0
Exp/Cntr=.3,.1

Type RM Length L Ch R = 1 ,18.045  ,1,1,1
#Sta/Elev= 10
   -16.5   10.03    -6.5   10.03      -4   11.83       0   11.83     3.5    9.33
       7    9.33    11.3   11.73    12.3   11.73    13.5   10.53    23.5   10.53
#Mann= 3 , 0 , 0
   -16.5    .035       0       0    .035       0    11.3    .035       0
#XS Ineff= 2 , 0
               0      20    11.3              20
Permanent Ineff=
       F       F
#Block Obstruct= 2 , 0
                            11.3
Bank Sta=0,11.3
XS Rating Curve= 0
Exp/Cntr=.3,.1

Type RM Length L Ch R = 1 ,18.044  ,44,44,44
#Sta/Elev= 12
   -16.5   10.03    -6.5   10.03      -4   11.83       0   11.83     3.5    9.33
     3.5    8.33       7    8.33       7    9.33    11.3   11.73    12.3   11.73
    13.5   10.53    23.5   10.53
#Mann= 3 , 0 , 0
   -16.5    .035       0       0    .035       0    11.3    .035       0
#XS Ineff= 2 , 0
               0      20    11.3              20
Permanent Ineff=
       F       F
#Block Obstruct= 2 , 0
                            11.3
Bank Sta=0,11.3
XS Rating Curve= 0
Exp/Cntr=.3,.1

Type RM Length L Ch R = 1 ,18      ,50,50,50
#Sta/Elev= 10
     -15    9.45      -5    9.45      -4   10.55       0   10.55     3.5    8.45
     8.5    8.45    11.7   10.55    12.3   10.55    13.6    9.55    23.6    9.55
#Mann= 3 , 0 , 0
     -15    .035       0       0    .035       0    11.7    .035       0
#XS Ineff= 2 , 0
               0      20    11.7              20
Permanent Ineff=
       F       F
#Block Obstruct= 2 , 0
                            11.7
Bank Sta=0,11.7
XS Rating Curve= 0
Exp/Cntr=.3,.1

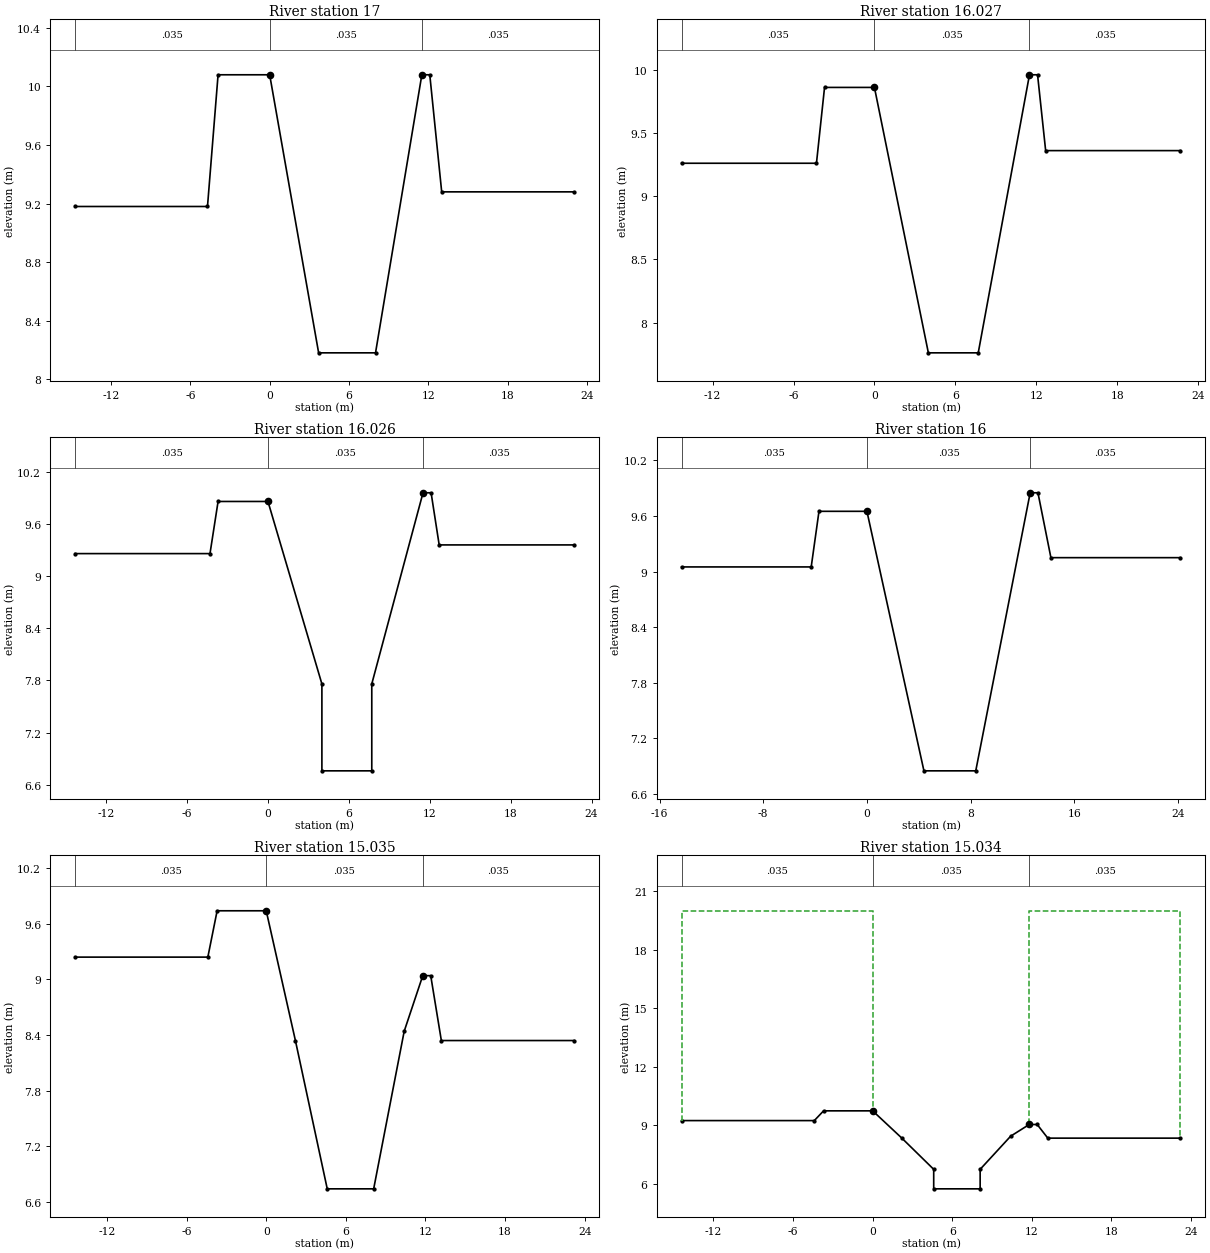
Type RM Length L Ch R = 1 ,17      ,23,23,23
#Sta/Elev= 10
   -14.7    9.18    -4.7    9.18    -3.9   10.08       0   10.08     3.7    8.18
       8    8.18    11.5   10.08    12.1   10.08      13    9.28      23    9.28
#Mann= 3 , 0 , 0
   -14.7    .035       0       0    .035       0    11.5    .035       0
#XS Ineff= 2 , 0
               0      20    11.5              20
Permanent Ineff=
       F       F
#Block Obstruct= 2 , 0
                            11.5
Bank Sta=0,11.5
XS Rating Curve= 0
Exp/Cntr=.3,.1

Type RM Length L Ch R = 1 ,16.027  ,1,1,1
#Sta/Elev= 10
   -14.3    9.26    -4.3    9.26    -3.7    9.86       0    9.86       4    7.76
     7.7    7.76    11.5    9.96    12.1    9.96    12.7    9.36    22.7    9.36
#Mann= 3 , 0 , 0
   -14.3    .035       0       0    .035       0    11.5    .035       0
#XS Ineff= 2 , 0
               0      20    11.5              20
Permanent Ineff=
       F       F
#Block Obstruct= 2 , 0
                            11.5
Bank Sta=0,11.5
XS Rating Curve= 0
Exp/Cntr=.3,.1

Type RM Length L Ch R = 1 ,16.026  ,26,26,26
#Sta/Elev= 12
   -14.3    9.26    -4.3    9.26    -3.7    9.86       0    9.86       4    7.76
       4    6.76     7.7    6.76     7.7    7.76    11.5    9.96    12.1    9.96
    12.7    9.36    22.7    9.36
#Mann= 3 , 0 , 0
   -14.3    .035       0       0    .035       0    11.5    .035       0
#XS Ineff= 2 , 0
               0      20    11.5              20
Permanent Ineff=
       F       F
#Block Obstruct= 2 , 0
                            11.5
Bank Sta=0,11.5
XS Rating Curve= 0
Exp/Cntr=.3,.1

Type RM Length L Ch R = 1 ,16      ,15,15,15
#Sta/Elev= 10
   -14.3    9.05    -4.3    9.05    -3.7    9.65       0    9.65     4.4    6.85
     8.4    6.85    12.6    9.85    13.2    9.85    14.2    9.15    24.2    9.15
#Mann= 3 , 0 , 0
   -14.3    .035       0       0    .035       0    12.6    .035       0
#XS Ineff= 2 , 0
               0      20    12.6              20
Permanent Ineff=
       F       F
#Block Obstruct= 2 , 0
                            12.6
Bank Sta=0,12.6
XS Rating Curve= 0
Exp/Cntr=.3,.1

Type RM Length L Ch R = 1 ,15.035  ,1,1,1
#Sta/Elev= 12
   -14.4    9.24    -4.4    9.24    -3.7    9.74       0    9.74     2.2    8.34
     4.6    6.74     8.1    6.74    10.4    8.44    11.8    9.04    12.4    9.04
    13.2    8.34    23.2    8.34
#Mann= 3 , 0 , 0
   -14.4    .035       0       0    .035       0    11.8    .035       0
#XS Ineff= 2 , 0
               0      20    11.8              20
Permanent Ineff=
       F       F
#Block Obstruct= 2 , 0
                            11.8
Bank Sta=0,11.8
XS Rating Curve= 0
Exp/Cntr=.3,.1

Type RM Length L Ch R = 1 ,15.034  ,9,9,9
#Sta/Elev= 14
   -14.4    9.24    -4.4    9.24    -3.7    9.74       0    9.74     2.2    8.34
     4.6    6.74     4.6    5.74     8.1    5.74     8.1    6.74    10.4    8.44
    11.8    9.04    12.4    9.04    13.2    8.34    23.2    8.34
#Mann= 3 , 0 , 0
   -14.4    .035       0       0    .035       0    11.8    .035       0
#XS Ineff= 2 , 0
               0      20    11.8              20
Permanent Ineff=
       F       F
#Block Obstruct= 2 , 0
                            11.8
Bank Sta=0,11.8
XS Rating Curve= 0
Exp/Cntr=.3,.1

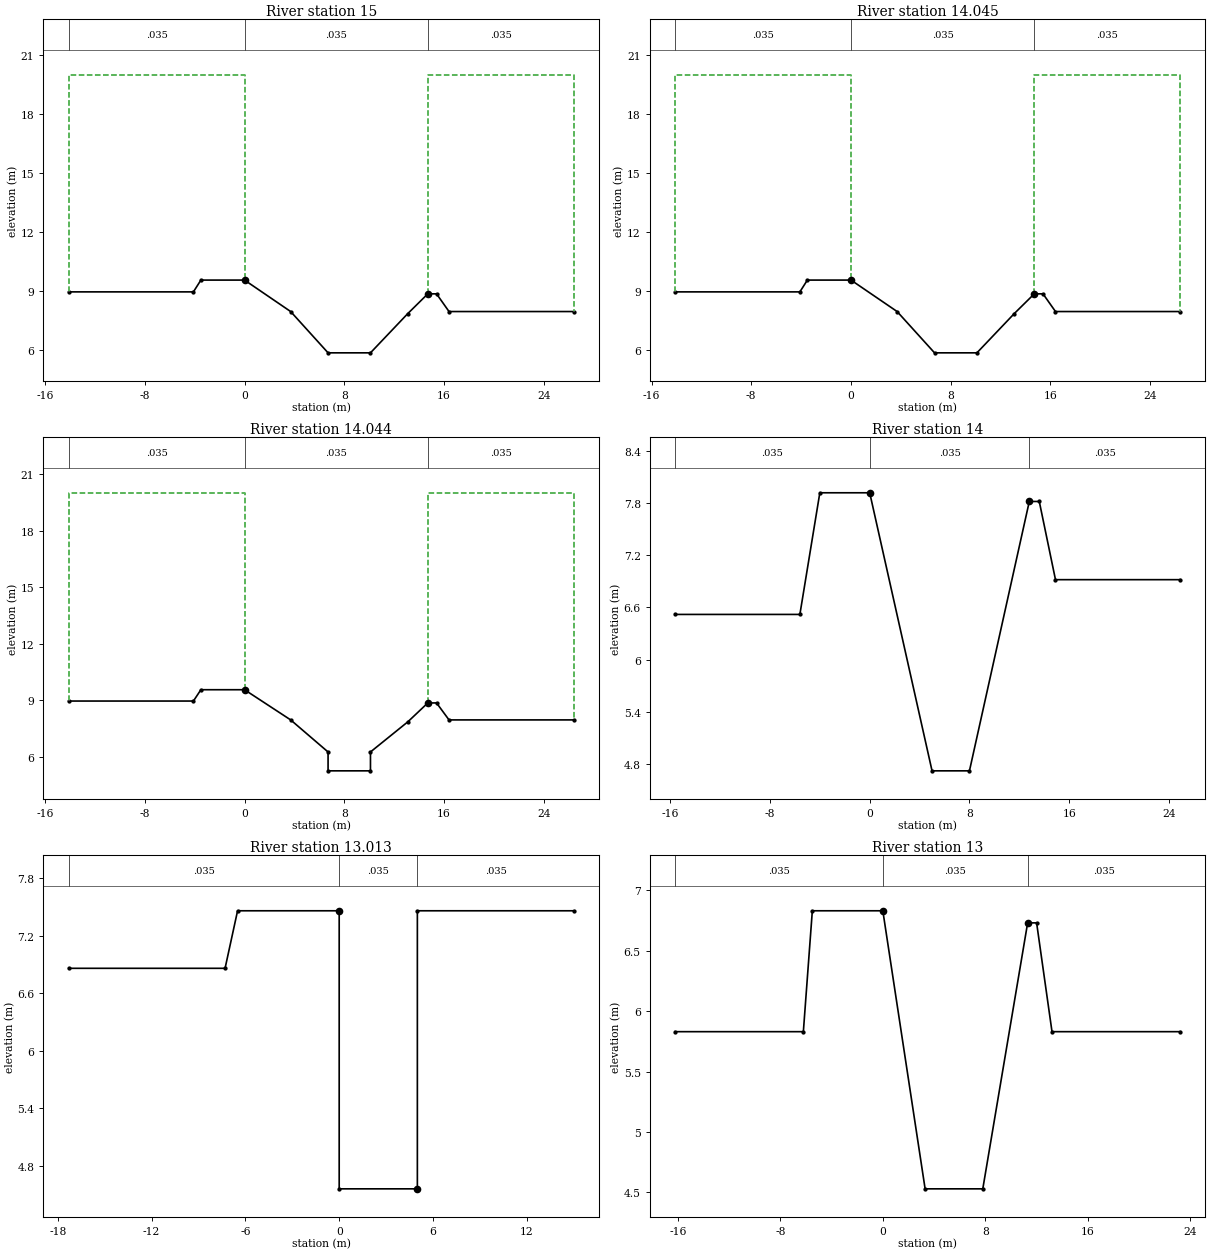
Type RM Length L Ch R = 1 ,15      ,5,5,5
#Sta/Elev= 12
   -14.1    8.96    -4.1    8.96    -3.5    9.56       0    9.56     3.7    7.96
     6.7    5.86    10.1    5.86    13.1    7.86    14.7    8.86    15.4    8.86
    16.4    7.96    26.4    7.96
#Mann= 3 , 0 , 0
   -14.1    .035       0       0    .035       0    14.7    .035       0
#XS Ineff= 2 , 0
               0      20    14.7              20
Permanent Ineff=
       F       F
#Block Obstruct= 2 , 0
                            14.7
Bank Sta=0,14.7
XS Rating Curve= 0
Exp/Cntr=.3,.1

Type RM Length L Ch R = 1 ,14.045  ,1,1,1
#Sta/Elev= 12
   -14.1    8.96    -4.1    8.96    -3.5    9.56       0    9.56     3.7    7.96
     6.7    5.86    10.1    5.86    13.1    7.86    14.7    8.86    15.4    8.86
    16.4    7.96    26.4    7.96
#Mann= 3 , 0 , 0
   -14.1    .035       0       0    .035       0    14.7    .035       0
#XS Ineff= 2 , 0
               0      20    14.7              20
Permanent Ineff=
       F       F
#Block Obstruct= 2 , 0
                            14.7
Bank Sta=0,14.7
XS Rating Curve= 0
Exp/Cntr=.3,.1

Type RM Length L Ch R = 1 ,14.044  ,44,44,44
#Sta/Elev= 14
   -14.1    8.96    -4.1    8.96    -3.5    9.56       0    9.56     3.7    7.96
     6.7    6.26     6.7    5.26    10.1    5.26    10.1    6.26    13.1    7.86
    14.7    8.86    15.4    8.86    16.4    7.96    26.4    7.96
#Mann= 3 , 0 , 0
   -14.1    .035       0       0    .035       0    14.7    .035       0
#XS Ineff= 2 , 0
               0      20    14.7              20
Permanent Ineff=
       F       F
#Block Obstruct= 2 , 0
                            14.7
Bank Sta=0,14.7
XS Rating Curve= 0
Exp/Cntr=.3,.1

Type RM Length L Ch R = 1 ,14      ,37,37,37
#Sta/Elev= 10
   -15.6    6.52    -5.6    6.52      -4    7.92       0    7.92       5    4.72
       8    4.72    12.8    7.82    13.6    7.82    14.9    6.92    24.9    6.92
#Mann= 3 , 0 , 0
   -15.6    .035       0       0    .035       0    12.8    .035       0
#XS Ineff= 2 , 0
               0      20    12.8              20
Permanent Ineff=
       F       F
#Block Obstruct= 2 , 0
                            12.8
Bank Sta=0,12.8
XS Rating Curve= 0
Exp/Cntr=.3,.1

Type RM Length L Ch R = 1 ,13.013  ,13,13,13
#Sta/Elev= 8
   -17.3    6.86    -7.3    6.86    -6.5    7.46       0    7.46       0    4.56
       5    4.56       5    7.46      15    7.46
#Mann= 3 , 0 , 0
   -17.3    .035       0       0    .035       0       5    .035       0
#XS Ineff= 2 , 0
               0      20       5              20
Permanent Ineff=
       F       F
#Block Obstruct= 2 , 0
                               5
Bank Sta=0,5
XS Rating Curve= 0
Exp/Cntr=.3,.1

Type RM Length L Ch R = 1 ,13      ,50,50,50
#Sta/Elev= 10
   -16.2    5.83    -6.2    5.83    -5.5    6.83       0    6.83     3.3    4.53
     7.8    4.53    11.3    6.73      12    6.73    13.2    5.83    23.2    5.83
#Mann= 3 , 0 , 0
   -16.2    .035       0       0    .035       0    11.3    .035       0
#XS Ineff= 2 , 0
               0      20    11.3              20
Permanent Ineff=
       F       F
#Block Obstruct= 2 , 0
                            11.3
Bank Sta=0,11.3
XS Rating Curve= 0
Exp/Cntr=.3,.1