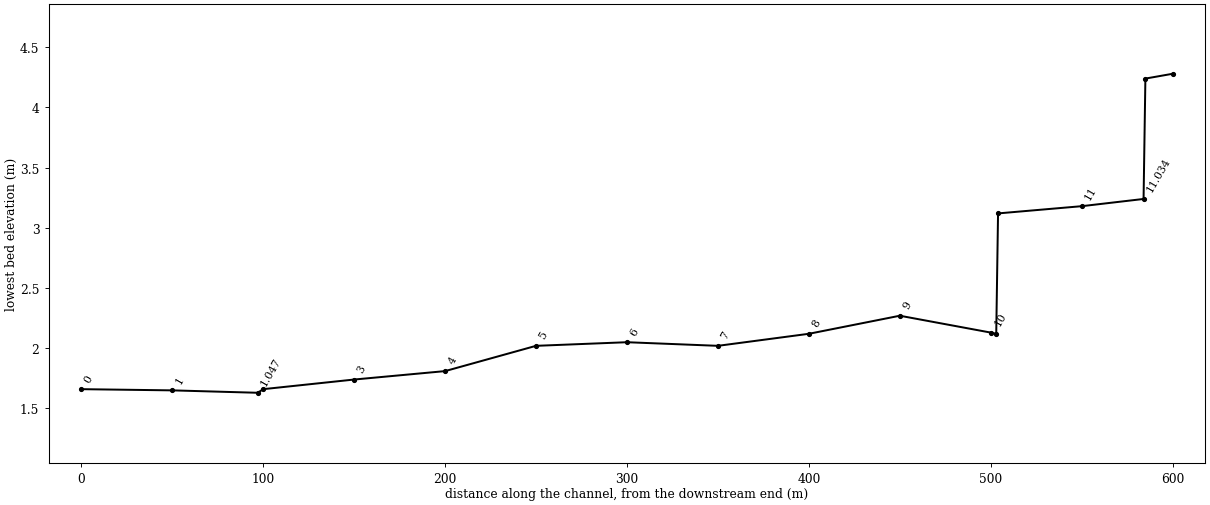
HEC-RAS study PMC.prj: PANMUN

--- PMC.g01 (geometry) --- (continued)

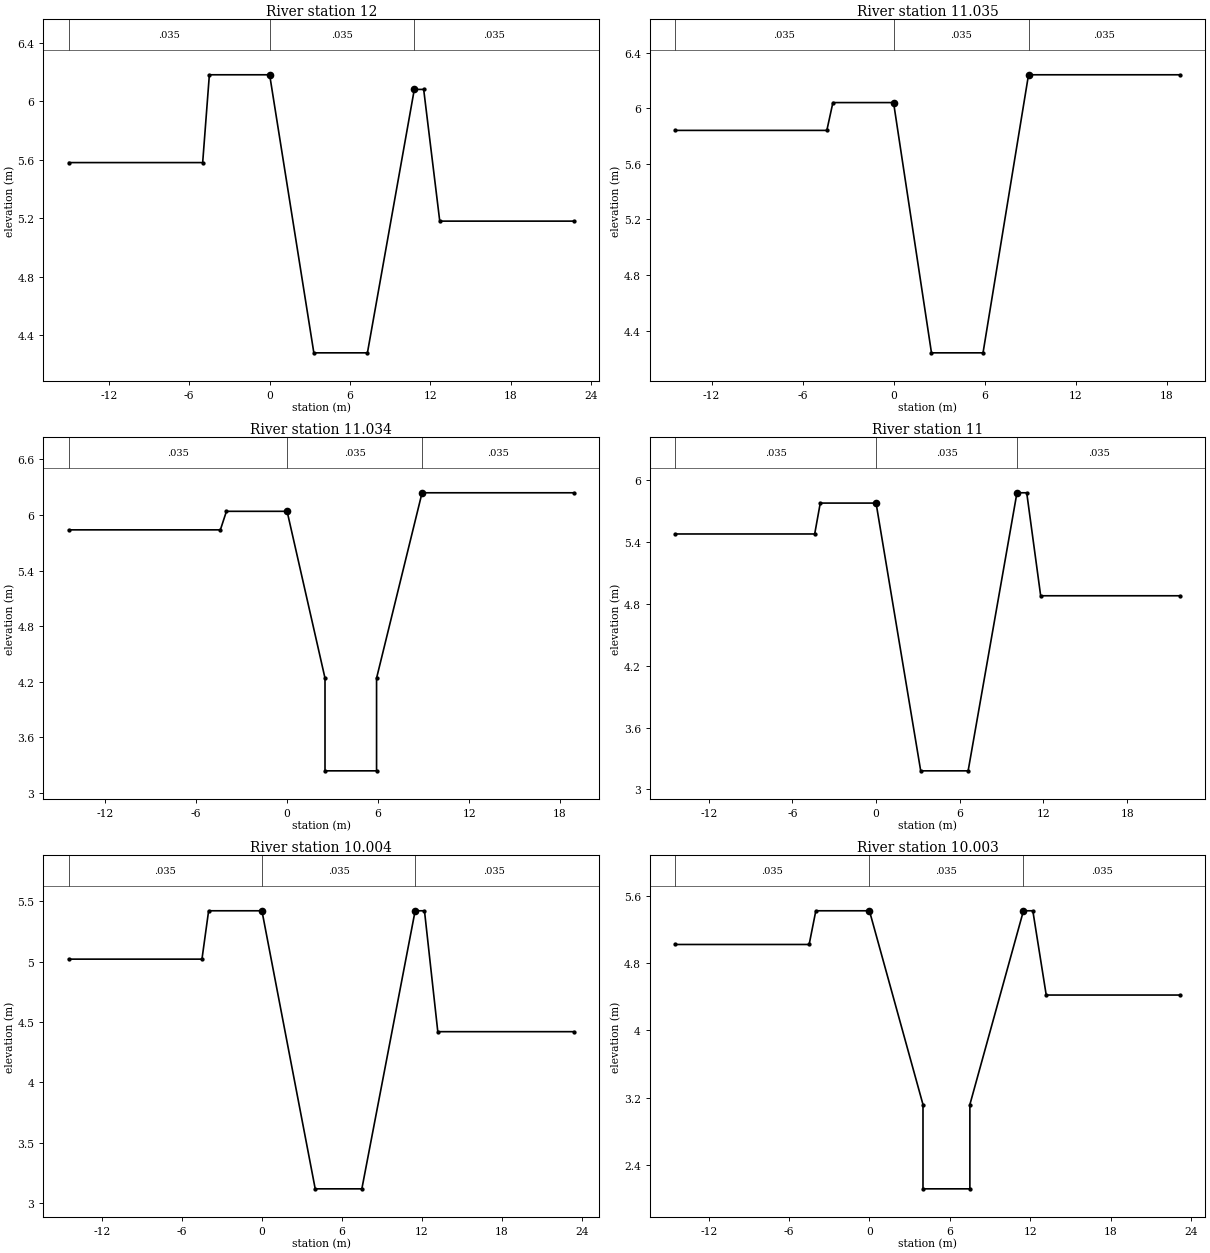
Type RM Length L Ch R = 1 ,12      ,15,15,15
#Sta/Elev= 10
     -15    5.58      -5    5.58    -4.5    6.18       0    6.18     3.3    4.28
     7.3    4.28    10.8    6.08    11.5    6.08    12.7    5.18    22.7    5.18
#Mann= 3 , 0 , 0
     -15    .035       0       0    .035       0    10.8    .035       0
#XS Ineff= 2 , 0
               0      20    10.8              20
Permanent Ineff=
       F       F
#Block Obstruct= 2 , 0
                            10.8
Bank Sta=0,10.8
XS Rating Curve= 0
Exp/Cntr=.3,.1

Type RM Length L Ch R = 1 ,11.035  ,1,1,1
#Sta/Elev= 8
   -14.4    5.84    -4.4    5.84      -4    6.04       0    6.04     2.5    4.24
     5.9    4.24     8.9    6.24    18.9    6.24
#Mann= 3 , 0 , 0
   -14.4    .035       0       0    .035       0     8.9    .035       0
#XS Ineff= 2 , 0
               0      20     8.9              20
Permanent Ineff=
       F       F
#Block Obstruct= 2 , 0
                             8.9
Bank Sta=0,8.9
XS Rating Curve= 0
Exp/Cntr=.3,.1

Type RM Length L Ch R = 1 ,11.034  ,34,34,34
#Sta/Elev= 10
   -14.4    5.84    -4.4    5.84      -4    6.04       0    6.04     2.5    4.24
     2.5    3.24     5.9    3.24     5.9    4.24     8.9    6.24    18.9    6.24
#Mann= 3 , 0 , 0
   -14.4    .035       0       0    .035       0     8.9    .035       0
#XS Ineff= 2 , 0
               0      20     8.9              20
Permanent Ineff=
       F       F
#Block Obstruct= 2 , 0
                             8.9
Bank Sta=0,8.9
XS Rating Curve= 0
Exp/Cntr=.3,.1

Type RM Length L Ch R = 1 ,11      ,46,46,46
#Sta/Elev= 10
   -14.4    5.48    -4.4    5.48      -4    5.78       0    5.78     3.2    3.18
     6.6    3.18    10.1    5.88    10.8    5.88    11.8    4.88    21.8    4.88
#Mann= 3 , 0 , 0
   -14.4    .035       0       0    .035       0    10.1    .035       0
#XS Ineff= 2 , 0
               0      20    10.1              20
Permanent Ineff=
       F       F
#Block Obstruct= 2 , 0
                            10.1
Bank Sta=0,10.1
XS Rating Curve= 0
Exp/Cntr=.3,.1

Type RM Length L Ch R = 1 ,10.004  ,1,1,1
#Sta/Elev= 10
   -14.5    5.02    -4.5    5.02      -4    5.42       0    5.42       4    3.12
     7.5    3.12    11.5    5.42    12.2    5.42    13.2    4.42    23.4    4.42
#Mann= 3 , 0 , 0
   -14.5    .035       0       0    .035       0    11.5    .035       0
#XS Ineff= 2 , 0
               0      20    11.5              20
Permanent Ineff=
       F       F
#Block Obstruct= 2 , 0
                            11.5
Bank Sta=0,11.5
XS Rating Curve= 0
Exp/Cntr=.3,.1

Type RM Length L Ch R = 1 ,10.003  ,3,3,3
#Sta/Elev= 12
   -14.5    5.02    -4.5    5.02      -4    5.42       0    5.42       4    3.12
       4    2.12     7.5    2.12     7.5    3.12    11.5    5.42    12.2    5.42
    13.2    4.42    23.2    4.42
#Mann= 3 , 0 , 0
   -14.5    .035       0       0    .035       0    11.5    .035       0
#XS Ineff= 2 , 0
               0      20    11.5              20
Permanent Ineff=
       F       F
#Block Obstruct= 2 , 0
                            11.5
Bank Sta=0,11.5
XS Rating Curve= 0
Exp/Cntr=.3,.1

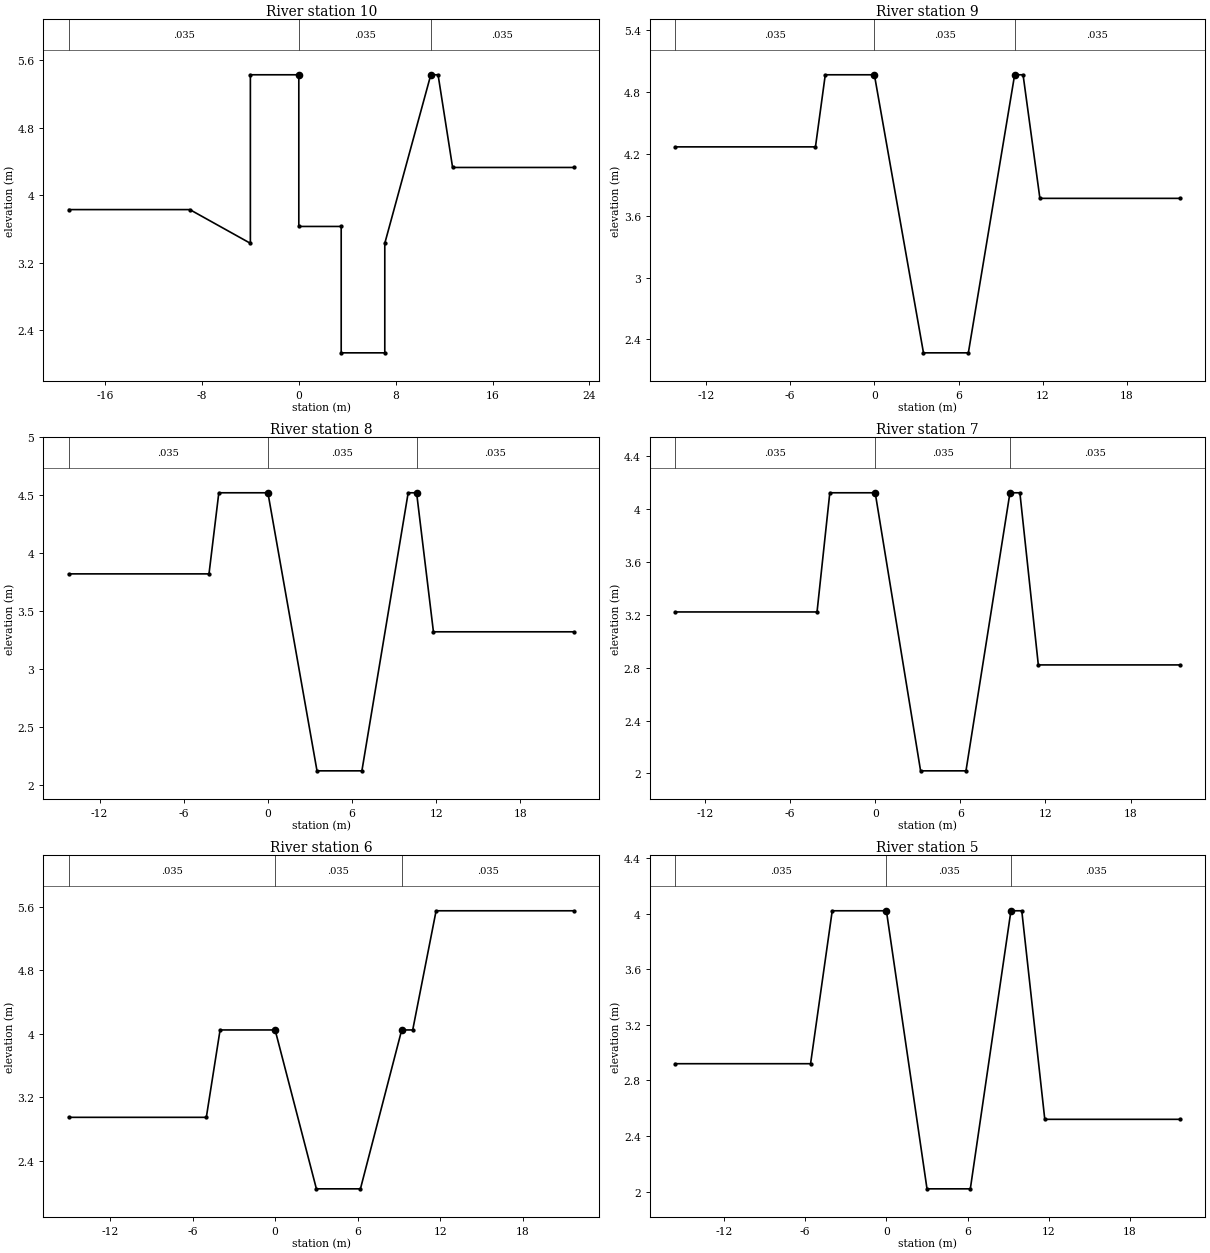
Type RM Length L Ch R = 1 ,10      ,50,50,50
#Sta/Elev= 14
     -19    3.83      -9    3.83      -4    3.43      -4    5.43       0    5.43
       0    3.63     3.5    3.63     3.5    2.13     7.1    2.13     7.1    3.43
    10.9    5.43    11.5    5.43    12.7    4.33    22.7    4.33
#Mann= 3 , 0 , 0
     -19    .035       0       0    .035       0    10.9    .035       0
#XS Ineff= 2 , 0
               0      20    10.9              20
Permanent Ineff=
       F       F
#Block Obstruct= 2 , 0
                            10.9
Bank Sta=0,10.9
XS Rating Curve= 0
Exp/Cntr=.3,.1

Type RM Length L Ch R = 1 ,9       ,50,50,50
#Sta/Elev= 10
   -14.2    4.27    -4.2    4.27    -3.5    4.97       0    4.97     3.5    2.27
     6.7    2.27      10    4.97    10.6    4.97    11.8    3.77    21.8    3.77
#Mann= 3 , 0 , 0
   -14.2    .035       0       0    .035       0      10    .035       0
#XS Ineff= 2 , 0
               0      20      10              20
Permanent Ineff=
       F       F
#Block Obstruct= 2 , 0
                              10
Bank Sta=0,10
XS Rating Curve= 0
Exp/Cntr=.3,.1

Type RM Length L Ch R = 1 ,8       ,50,50,50
#Sta/Elev= 10
   -14.2    3.82    -4.2    3.82    -3.5    4.52       0    4.52     3.5    2.12
     6.7    2.12      10    4.52    10.6    4.52    11.8    3.32    21.8    3.32
#Mann= 3 , 0 , 0
   -14.2    .035       0       0    .035       0    10.6    .035       0
#XS Ineff= 2 , 0
               0      20    10.6              20
Permanent Ineff=
       F       F
#Block Obstruct= 2 , 0
                            10.6
Bank Sta=0,10.6
XS Rating Curve= 0
Exp/Cntr=.3,.1

Type RM Length L Ch R = 1 ,7       ,50,50,50
#Sta/Elev= 10
   -14.1    3.22    -4.1    3.22    -3.2    4.12       0    4.12     3.2    2.02
     6.4    2.02     9.5    4.12    10.2    4.12    11.5    2.82    21.5    2.82
#Mann= 3 , 0 , 0
   -14.1    .035       0       0    .035       0     9.5    .035       0
#XS Ineff= 2 , 0
               0      20     9.5              20
Permanent Ineff=
       F       F
#Block Obstruct= 2 , 0
                             9.5
Bank Sta=0,9.5
XS Rating Curve= 0
Exp/Cntr=.3,.1

Type RM Length L Ch R = 1 ,6       ,50,50,50
#Sta/Elev= 10
     -15    2.95      -5    2.95      -4    4.05       0    4.05       3    2.05
     6.2    2.05     9.2    4.05      10    4.05    11.7    5.55    21.7    5.55
#Mann= 3 , 0 , 0
     -15    .035       0       0    .035       0     9.2    .035       0
#XS Ineff= 2 , 0
               0      20     9.2              20
Permanent Ineff=
       F       F
#Block Obstruct= 2 , 0
                             9.2
Bank Sta=0,9.2
XS Rating Curve= 0
Exp/Cntr=.3,.1

Type RM Length L Ch R = 1 ,5       ,50,50,50
#Sta/Elev= 10
   -15.6    2.92    -5.6    2.92      -4    4.02       0    4.02       3    2.02
     6.2    2.02     9.2    4.02      10    4.02    11.7    2.52    21.7    2.52
#Mann= 3 , 0 , 0
   -15.6    .035       0       0    .035       0     9.2    .035       0
#XS Ineff= 2 , 0
               0      20     9.2              20
Permanent Ineff=
       F       F
#Block Obstruct= 2 , 0
                             9.2
Bank Sta=0,9.2
XS Rating Curve= 0
Exp/Cntr=.3,.1

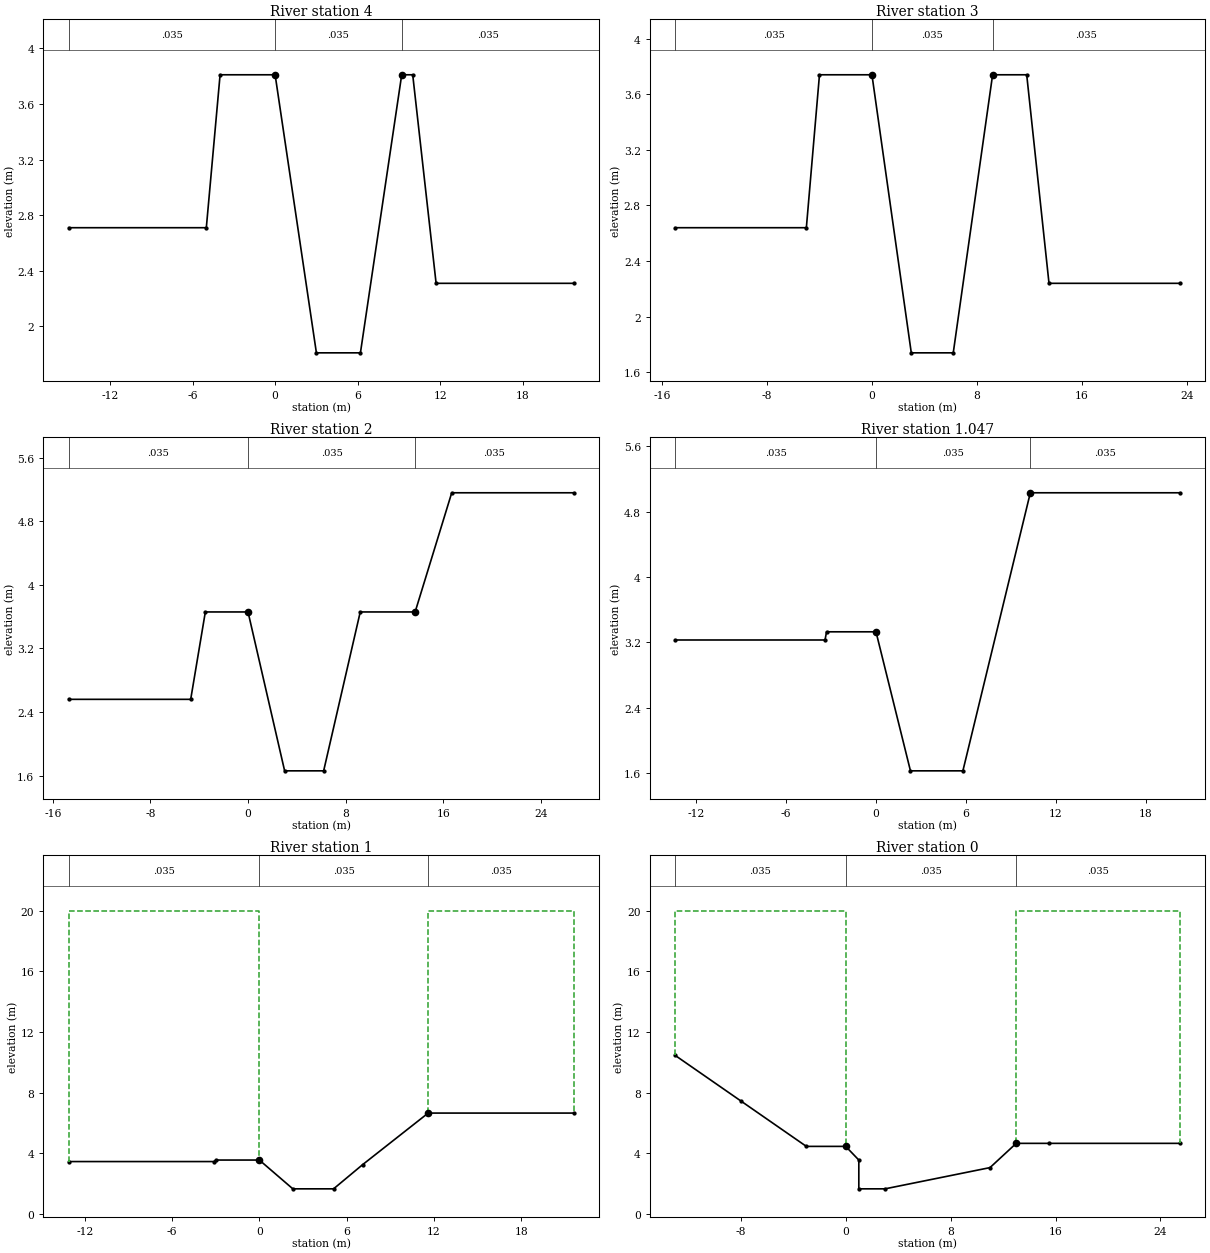
Type RM Length L Ch R = 1 ,4       ,50,50,50
#Sta/Elev= 10
     -15    2.71      -5    2.71      -4    3.81       0    3.81       3    1.81
     6.2    1.81     9.2    3.81      10    3.81    11.7    2.31    21.7    2.31
#Mann= 3 , 0 , 0
     -15    .035       0       0    .035       0     9.2    .035       0
#XS Ineff= 2 , 0
               0      20     9.2              20
Permanent Ineff=
       F       F
#Block Obstruct= 2 , 0
                             9.2
Bank Sta=0,9.2
XS Rating Curve= 0
Exp/Cntr=.3,.1

Type RM Length L Ch R = 1 ,3       ,50,50,50
#Sta/Elev= 10
     -15    2.64      -5    2.64      -4    3.74       0    3.74       3    1.74
     6.2    1.74     9.2    3.74    11.8    3.74    13.5    2.24    23.5    2.24
#Mann= 3 , 0 , 0
     -15    .035       0       0    .035       0     9.2    .035       0
#XS Ineff= 2 , 0
               0      20     9.2              20
Permanent Ineff=
       F       F
#Block Obstruct= 2 , 0
                             9.2
Bank Sta=0,9.2
XS Rating Curve= 0
Exp/Cntr=.3,.1

Type RM Length L Ch R = 1 ,2       ,3,3,3
#Sta/Elev= 10
   -14.7    2.56    -4.7    2.56    -3.5    3.66       0    3.66       3    1.66
     6.2    1.66     9.2    3.66    13.7    3.66    16.7    5.16    26.7    5.16
#Mann= 3 , 0 , 0
   -14.7    .035       0       0    .035       0    13.7    .035       0
#XS Ineff= 2 , 0
               0      20    13.7              20
Permanent Ineff=
       F       F
#Block Obstruct= 2 , 0
                            13.7
Bank Sta=0,13.7
XS Rating Curve= 0
Exp/Cntr=.3,.1

Type RM Length L Ch R = 1 ,1.047   ,47,47,47
#Sta/Elev= 8
   -13.4    3.23    -3.4    3.23    -3.3    3.33       0    3.33     2.3    1.63
     5.8    1.63    10.3    5.03    20.3    5.03
#Mann= 3 , 0 , 0
   -13.4    .035       0       0    .035       0    10.3    .035       0
#XS Ineff= 2 , 0
               0      20    10.3              20
Permanent Ineff=
       F       F
#Block Obstruct= 2 , 0
                            10.3
Bank Sta=0,10.3
XS Rating Curve= 0
Exp/Cntr=.3,.1

Type RM Length L Ch R = 1 ,1       ,50,50,50
#Sta/Elev= 9
   -13.1    3.45    -3.1    3.45      -3    3.55       0    3.55     2.3    1.65
     5.1    1.65     7.1    3.25    11.6    6.65    21.6    6.65
#Mann= 3 , 0 , 0
   -13.1    .035       0       0    .035       0    11.6    .035       0
#XS Ineff= 2 , 0
               0      20    11.6              20
Permanent Ineff=
       F       F
#Block Obstruct= 2 , 0
                            11.6
Bank Sta=0,11.6
XS Rating Curve= 0
Exp/Cntr=.3,.1

Type RM Length L Ch R = 1 ,0       ,0,0,0
#Sta/Elev= 11
     -13   10.46      -8    7.46      -3    4.46       0    4.46       1    3.56
       1    1.66       3    1.66      11    3.06      13    4.66    15.5    4.66
    25.5    4.66
#Mann= 3 , 0 , 0
     -13    .035       0       0    .035       0      13    .035       0
#XS Ineff= 2 , 0
               0      20      13              20
Permanent Ineff=
       F       F
#Block Obstruct= 2 , 0
                              13
Bank Sta=0,13
XS Rating Curve= 0
Exp/Cntr=.3,.1

Chan Stop Cuts=-1