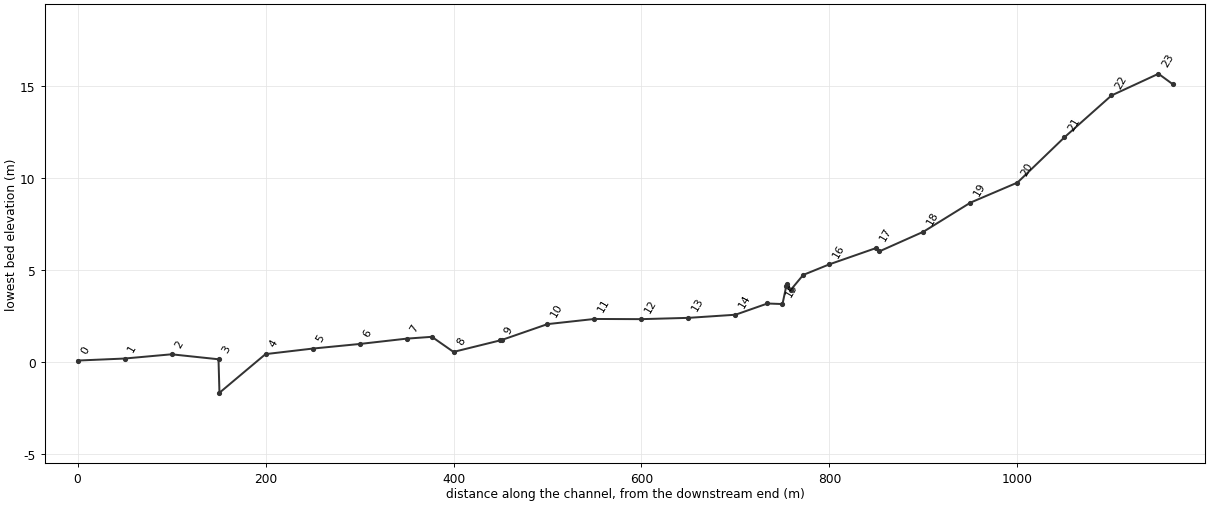
--- skc.prj (project) ---

Proj Title=sipkae
Current Plan=p01
Default Exp/Contr=.3,.1
SI Units
Geom File=g01
Flow File=f01
Plan File=p01
Y Axis Title=Elevation
X Axis Title(PF)=Main Channel Distance
X Axis Title(XS)=Station
BEGIN DESCRIPTION:
           BACK WATER COMPUTATION
      APPLICATION OF HEC-2 BY Samju Construction Engineering
      sipgae-ch: 10,20,30,100,150³âºóµµ °³¼öÀü
END DESCRIPTION:
DSS Export Rating Curves= 0
DSS Export Rating Curve Sorted= 0
DSS Export Volume Flow Curves= 0
DXF OffsetX= 0
DXF OffsetY= 0
DXF ScaleX= 1
DXF ScaleY= 10

--- skc.p01 (plan) ---

Plan Title=Imported Plan 01
Version=Version 3.0.1  Mar 2001
Short Identifier=Imported Pla
Geom File=g01
Flow File=f01
Subcritical Flow
K Sum by GR= 0
Std Step Tol= 0.003
Critical Tol= 0.003
Num of Std Step Trials= 20
Max Error Tol= 0.1
Flow Tol Ratio= 0.001
Split Flow NTrial= 30
Split Flow Tol= 0.02
Split Flow Ratio= 0.02
Log Output Level= 0
Friction Slope Method= 1
Unsteady Friction Slope Method= 2
Parabolic Critical Depth
Global Vel Dist= 0 , 0 , 0
Global Log Level= 0
CheckData=True
Encroach Param=-1 ,0,0, 0
Computation Interval=1HOUR
Output Interval=1HOUR
Run HTab= 0
Run UNet= 0
Run PostProcess= 0
UNET Theta= 1
UNET ZTol= 0.02
UNET ZSATol= 0.1
UNET MxIter= 20
UNET MaxInSteps= 20
UNET DtIC= 0
UNET DtMin= 0
UNET MaxCRTS= 20
UNET WFStab= 2
UNET SFStab= 1
UNET WFX= 1
UNET SFX= 1
UNET Convert EG Bridges=-1
UNET Use Existing IB Tables=-1
Instantaneous Interval=1HOUR
Write IC File= 0
Write Velocity= 0
Write Detailed= 0

--- skc.f01 (steady flow) ---

Flow Title=Imported Flow 01
Version=Version 3.0.1  Mar 2001
Number of Profiles= 5
Profile Names=10yr,20yr,30yr,50yr,80yr
River Rch & RM=RIVER-1,Reach-1         ,23.015
   13.81   15.22   16.04   17.08   18.03
River Rch & RM=SIPKAE,SIPKAE          ,23.015
   13.81   15.22   16.04   17.08   18.03
Boundary for River Rch & Prof#=SIPKAE,SIPKAE          , 1
Up Type= 0
Dn Type= 3
Dn Slope=.014
Boundary for River Rch & Prof#=SIPKAE,SIPKAE          , 2
Up Type= 0
Dn Type= 3
Dn Slope=.014
Boundary for River Rch & Prof#=SIPKAE,SIPKAE          , 3
Up Type= 0
Dn Type= 3
Dn Slope=.014
Boundary for River Rch & Prof#=SIPKAE,SIPKAE          , 4
Up Type= 0
Dn Type= 3
Dn Slope=.014
Boundary for River Rch & Prof#=SIPKAE,SIPKAE          , 5
Up Type= 0
Dn Type= 3
Dn Slope=.014
DSS Import GetInterval= 0
DSS Import GetPeak= 0
DSS Import FillOption= 0

--- skc.g01 (geometry) ---

Geom Title=Imported Geom 01
Version=Version 3.0.1  Mar 2001

River Reach=SIPKAE          ,SIPKAE
Reach XY= 2
              .5             .95              .5             .05

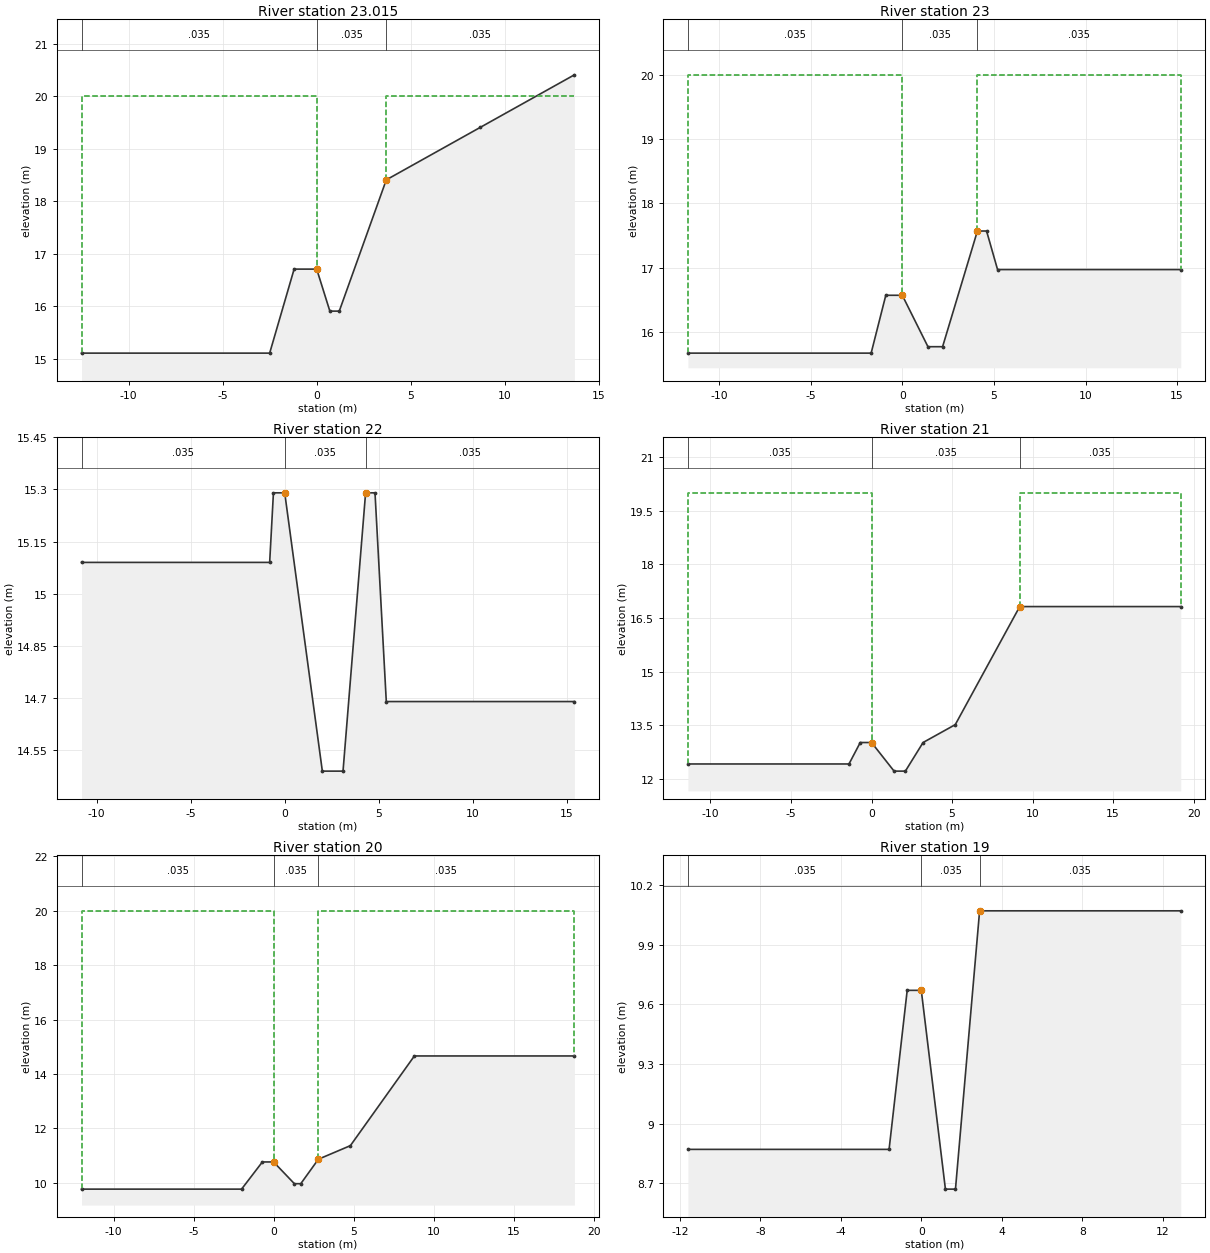
Type RM Length L Ch R = 1 ,23.015  ,15,15,15
#Sta/Elev= 9
   -12.5   15.11    -2.5   15.11    -1.2   16.71       0   16.71      .7   15.91
     1.2   15.91     3.7   18.41     8.7   19.41    13.7   20.41
#Mann= 3 , 0 , 0
   -12.5    .035       0       0    .035       0     3.7    .035       0
#XS Ineff= 2 , 0
               0      20     3.7              20
Permanent Ineff=
       F       F
#Block Obstruct= 2 , 0
                             3.7
Bank Sta=0,3.7
XS Rating Curve= 0
Exp/Cntr=.3,.1

Type RM Length L Ch R = 1 ,23      ,50,50,50
#Sta/Elev= 10
   -11.7   15.67    -1.7   15.67     -.9   16.57       0   16.57     1.4   15.77
     2.2   15.77     4.1   17.57     4.6   17.57     5.2   16.97    15.2   16.97
#Mann= 3 , 0 , 0
   -11.7    .035       0       0    .035       0     4.1    .035       0
#XS Ineff= 2 , 0
               0      20     4.1              20
Permanent Ineff=
       F       F
#Block Obstruct= 2 , 0
                             4.1
Bank Sta=0,4.1
XS Rating Curve= 0
Exp/Cntr=.3,.1

Type RM Length L Ch R = 1 ,22      ,50,50,50
#Sta/Elev= 10
   -10.8   15.09     -.8   15.09     -.6   15.29       0   15.29       2   14.49
     3.1   14.49     4.3   15.29     4.8   15.29     5.4   14.69    15.4   14.69
#Mann= 3 , 0 , 0
   -10.8    .035       0       0    .035       0     4.3    .035       0
#XS Ineff= 2 , 0
               0      20     4.3              20
Permanent Ineff=
       F       F
#Block Obstruct= 2 , 0
                             4.3
Bank Sta=0,4.3
XS Rating Curve= 0
Exp/Cntr=.3,.1

Type RM Length L Ch R = 1 ,21      ,50,50,50
#Sta/Elev= 10
   -11.4   12.42    -1.4   12.42     -.7   13.02       0   13.02     1.4   12.22
     2.1   12.22     3.2   13.02     5.2   13.52     9.2   16.82    19.2   16.82
#Mann= 3 , 0 , 0
   -11.4    .035       0       0    .035       0     9.2    .035       0
#XS Ineff= 2 , 0
               0      20     9.2              20
Permanent Ineff=
       F       F
#Block Obstruct= 2 , 0
                             9.2
Bank Sta=0,9.2
XS Rating Curve= 0
Exp/Cntr=.3,.1

Type RM Length L Ch R = 1 ,20      ,50,50,50
#Sta/Elev= 10
     -12    9.76      -2    9.76     -.7   10.76       0   10.76     1.3    9.96
     1.7    9.96     2.8   10.86     4.8   11.36     8.8   14.66    18.8   14.66
#Mann= 3 , 0 , 0
     -12    .035       0       0    .035       0     2.8    .035       0
#XS Ineff= 2 , 0
               0      20     2.8              20
Permanent Ineff=
       F       F
#Block Obstruct= 2 , 0
                             2.8
Bank Sta=0,2.8
XS Rating Curve= 0
Exp/Cntr=.3,.1

Type RM Length L Ch R = 1 ,19      ,50,50,50
#Sta/Elev= 8
   -11.6    8.87    -1.6    8.87     -.7    9.67       0    9.67     1.2    8.67
     1.7    8.67     2.9   10.07    12.9   10.07
#Mann= 3 , 0 , 0
   -11.6    .035       0       0    .035       0     2.9    .035       0
#XS Ineff= 2 , 0
               0      20     2.9              20
Permanent Ineff=
       F       F
#Block Obstruct= 2 , 0
                             2.9
Bank Sta=0,2.9
XS Rating Curve= 0
Exp/Cntr=.3,.1

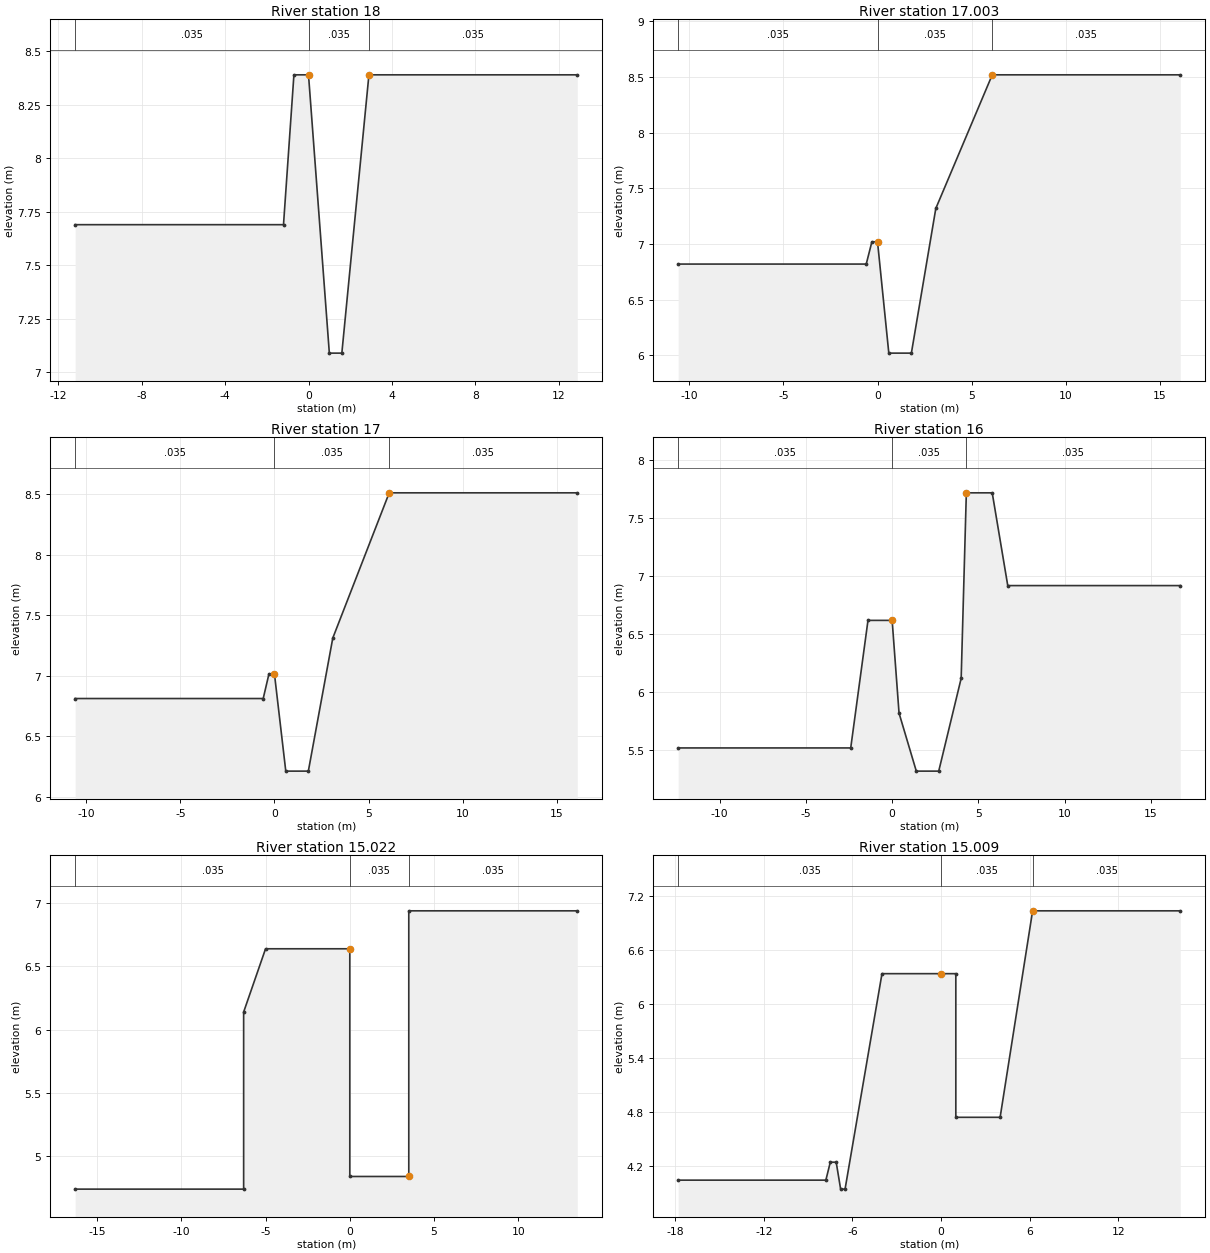
Type RM Length L Ch R = 1 ,18      ,47,47,47
#Sta/Elev= 8
   -11.2    7.69    -1.2    7.69     -.7    8.39       0    8.39       1    7.09
     1.6    7.09     2.9    8.39    12.9    8.39
#Mann= 3 , 0 , 0
   -11.2    .035       0       0    .035       0     2.9    .035       0
#XS Ineff= 2 , 0
               0      20     2.9              20
Permanent Ineff=
       F       F
#Block Obstruct= 2 , 0
                             2.9
Bank Sta=0,2.9
XS Rating Curve= 0
Exp/Cntr=.3,.1

Type RM Length L Ch R = 1 ,17.003  ,3,3,3
#Sta/Elev= 9
   -10.6    6.82     -.6    6.82     -.3    7.02       0    7.02      .6    6.02
     1.8    6.02     3.1    7.32     6.1    8.52    16.1    8.52
#Mann= 3 , 0 , 0
   -10.6    .035       0       0    .035       0     6.1    .035       0
#XS Ineff= 2 , 0
               0      20     6.1              20
Permanent Ineff=
       F       F
#Block Obstruct= 2 , 0
                             6.1
Bank Sta=0,6.1
XS Rating Curve= 0
Exp/Cntr=.3,.1

Type RM Length L Ch R = 1 ,17      ,50,50,50
#Sta/Elev= 9
   -10.6    6.81     -.6    6.81     -.3    7.01       0    7.01      .6    6.21
     1.8    6.21     3.1    7.31     6.1    8.51    16.1    8.51
#Mann= 3 , 0 , 0
   -10.6    .035       0       0    .035       0     6.1    .035       0
#XS Ineff= 2 , 0
               0      20     6.1              20
Permanent Ineff=
       F       F
#Block Obstruct= 2 , 0
                             6.1
Bank Sta=0,6.1
XS Rating Curve= 0
Exp/Cntr=.3,.1

Type RM Length L Ch R = 1 ,16      ,28,28,28
#Sta/Elev= 12
   -12.4    5.52    -2.4    5.52    -1.4    6.62       0    6.62      .4    5.82
     1.4    5.32     2.7    5.32       4    6.12     4.3    7.72     5.8    7.72
     6.7    6.92    16.7    6.92
#Mann= 3 , 0 , 0
   -12.4    .035       0       0    .035       0     4.3    .035       0
#XS Ineff= 2 , 0
               0      20     4.3              20
Permanent Ineff=
       F       F
#Block Obstruct= 2 , 0
                             4.3
Bank Sta=0,4.3
XS Rating Curve= 0
Exp/Cntr=.3,.1

Type RM Length L Ch R = 1 ,15.022  ,13,13,13
#Sta/Elev= 9
   -16.3    4.74    -6.3    4.74    -6.3    6.14      -5    6.64       0    6.64
       0    4.84     3.5    4.84     3.5    6.94    13.5    6.94
#Mann= 3 , 0 , 0
   -16.3    .035       0       0    .035       0     3.5    .035       0
#XS Ineff= 2 , 0
               0      20     3.5              20
Permanent Ineff=
       F       F
#Block Obstruct= 2 , 0
                             3.5
Bank Sta=0,3.5
XS Rating Curve= 0
Exp/Cntr=.3,.1

Type RM Length L Ch R = 1 ,15.009  ,4,4,4
#Sta/Elev= 13
   -17.8    4.04    -7.8    4.04    -7.5    4.24    -7.1    4.24    -6.8    3.94
    -6.5    3.94      -4    6.34       0    6.34       1    6.34       1    4.74
       4    4.74     6.2    7.04    16.2    7.04
#Mann= 3 , 0 , 0
   -17.8    .035       0       0    .035       0     6.2    .035       0
#XS Ineff= 2 , 0
               0      20     6.2              20
Permanent Ineff=
       F       F
#Block Obstruct= 2 , 0
                             6.2
Bank Sta=0,6.2
XS Rating Curve= 0
Exp/Cntr=.3,.1

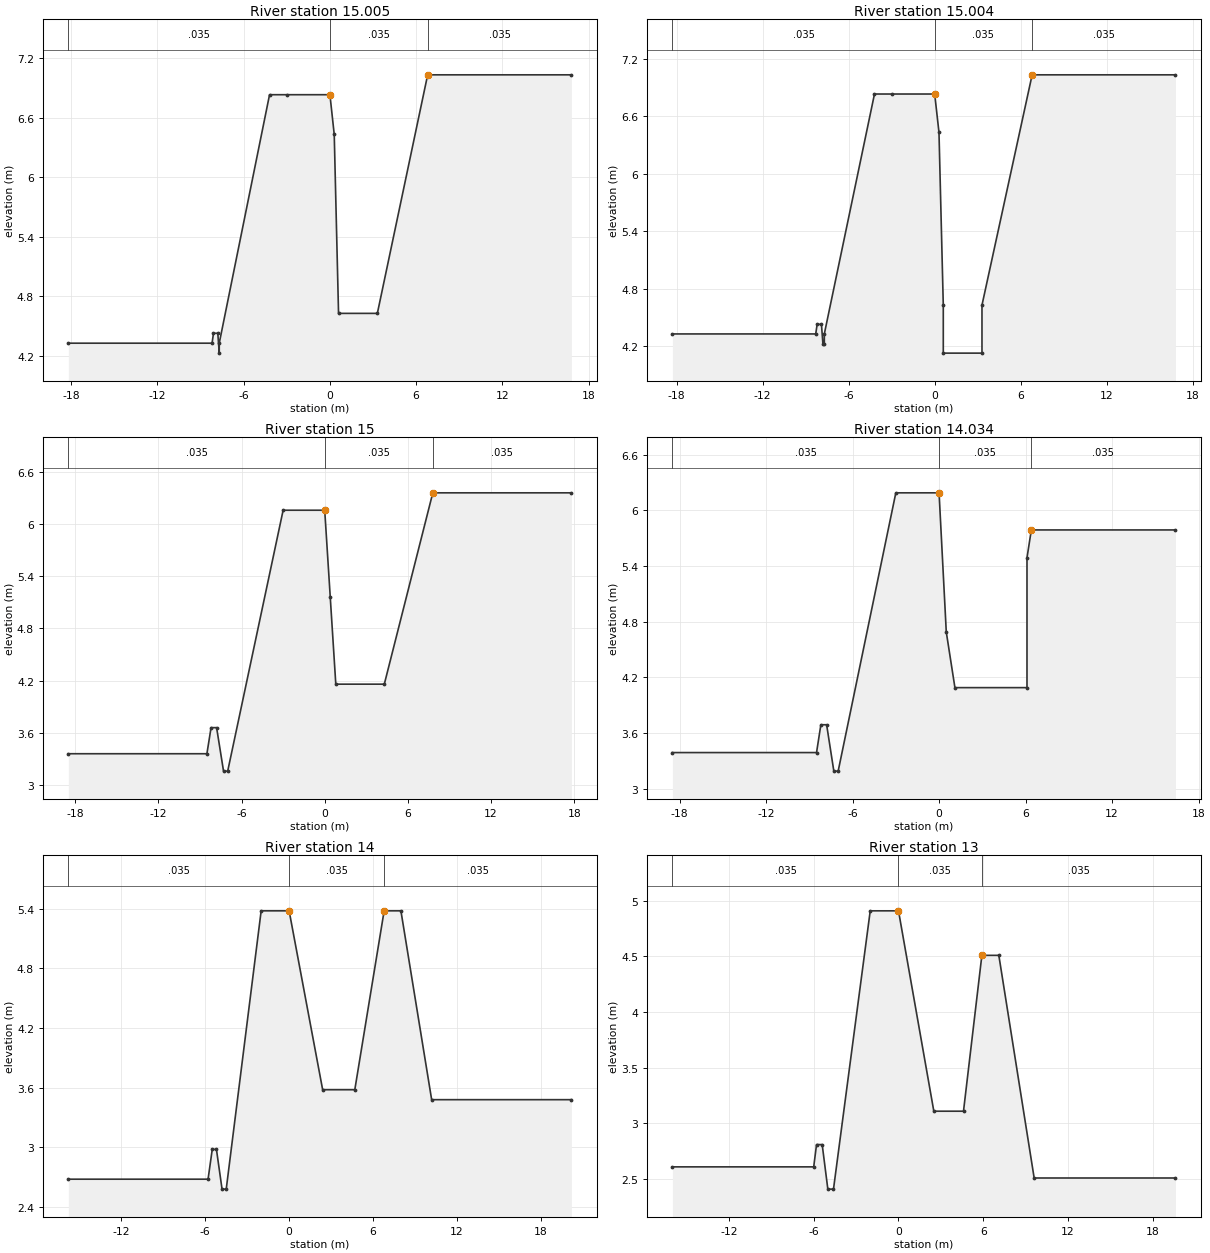
Type RM Length L Ch R = 1 ,15.005  ,1,1,1
#Sta/Elev= 14
   -18.2    4.33    -8.2    4.33    -8.1    4.43    -7.8    4.43    -7.7    4.23
    -7.7    4.33    -4.2    6.83      -3    6.83       0    6.83      .3    6.43
      .6    4.63     3.3    4.63     6.8    7.03    16.8    7.03
#Mann= 3 , 0 , 0
   -18.2    .035       0       0    .035       0     6.8    .035       0
#XS Ineff= 2 , 0
               0      20     6.8              20
Permanent Ineff=
       F       F
#Block Obstruct= 2 , 0
                             6.8
Bank Sta=0,6.8
XS Rating Curve= 0
Exp/Cntr=.3,.1

Type RM Length L Ch R = 1 ,15.004  ,4,4,4
#Sta/Elev= 17
   -18.3    4.33    -8.3    4.33    -8.2    4.43    -7.9    4.43    -7.8    4.23
    -7.7    4.23    -7.7    4.33    -4.2    6.83      -3    6.83       0    6.83
      .3    6.43      .6    4.63      .6    4.13     3.3    4.13     3.3    4.63
     6.8    7.03    16.8    7.03
#Mann= 3 , 0 , 0
   -18.3    .035       0       0    .035       0     6.8    .035       0
#XS Ineff= 2 , 0
               0      20     6.8              20
Permanent Ineff=
       F       F
#Block Obstruct= 2 , 0
                             6.8
Bank Sta=0,6.8
XS Rating Curve= 0
Exp/Cntr=.3,.1

Type RM Length L Ch R = 1 ,15      ,16,16,16
#Sta/Elev= 13
   -18.5    3.36    -8.5    3.36    -8.2    3.66    -7.8    3.66    -7.3    3.16
      -7    3.16      -3    6.16       0    6.16      .4    5.16      .8    4.16
     4.3    4.16     7.8    6.36    17.8    6.36
#Mann= 3 , 0 , 0
   -18.5    .035       0       0    .035       0     7.8    .035       0
#XS Ineff= 2 , 0
               0      20     7.8              20
Permanent Ineff=
       F       F
#Block Obstruct= 2 , 0
                             7.8
Bank Sta=0,7.8
XS Rating Curve= 0
Exp/Cntr=.3,.1

Type RM Length L Ch R = 1 ,14.034  ,34,34,34
#Sta/Elev= 14
   -18.5    3.39    -8.5    3.39    -8.2    3.69    -7.8    3.69    -7.3    3.19
      -7    3.19      -3    6.19       0    6.19      .5    4.69     1.1    4.09
     6.1    4.09     6.1    5.49     6.4    5.79    16.4    5.79
#Mann= 3 , 0 , 0
   -18.5    .035       0       0    .035       0     6.4    .035       0
#XS Ineff= 2 , 0
               0      20     6.4              20
Permanent Ineff=
       F       F
#Block Obstruct= 2 , 0
                             6.4
Bank Sta=0,6.4
XS Rating Curve= 0
Exp/Cntr=.3,.1

Type RM Length L Ch R = 1 ,14      ,50,50,50
#Sta/Elev= 14
   -15.8    2.68    -5.8    2.68    -5.5    2.98    -5.2    2.98    -4.8    2.58
    -4.5    2.58      -2    5.38       0    5.38     2.4    3.58     4.7    3.58
     6.8    5.38       8    5.38    10.2    3.48    20.2    3.48
#Mann= 3 , 0 , 0
   -15.8    .035       0       0    .035       0     6.8    .035       0
#XS Ineff= 2 , 0
               0      20     6.8              20
Permanent Ineff=
       F       F
#Block Obstruct= 2 , 0
                             6.8
Bank Sta=0,6.8
XS Rating Curve= 0
Exp/Cntr=.3,.1

Type RM Length L Ch R = 1 ,13      ,50,50,50
#Sta/Elev= 14
     -16    2.61      -6    2.61    -5.8    2.81    -5.4    2.81      -5    2.41
    -4.6    2.41      -2    4.91       0    4.91     2.5    3.11     4.6    3.11
     5.9    4.51     7.1    4.51     9.6    2.51    19.6    2.51
#Mann= 3 , 0 , 0
     -16    .035       0       0    .035       0     5.9    .035       0
#XS Ineff= 2 , 0
               0      20     5.9              20
Permanent Ineff=
       F       F
#Block Obstruct= 2 , 0
                             5.9
Bank Sta=0,5.9
XS Rating Curve= 0
Exp/Cntr=.3,.1

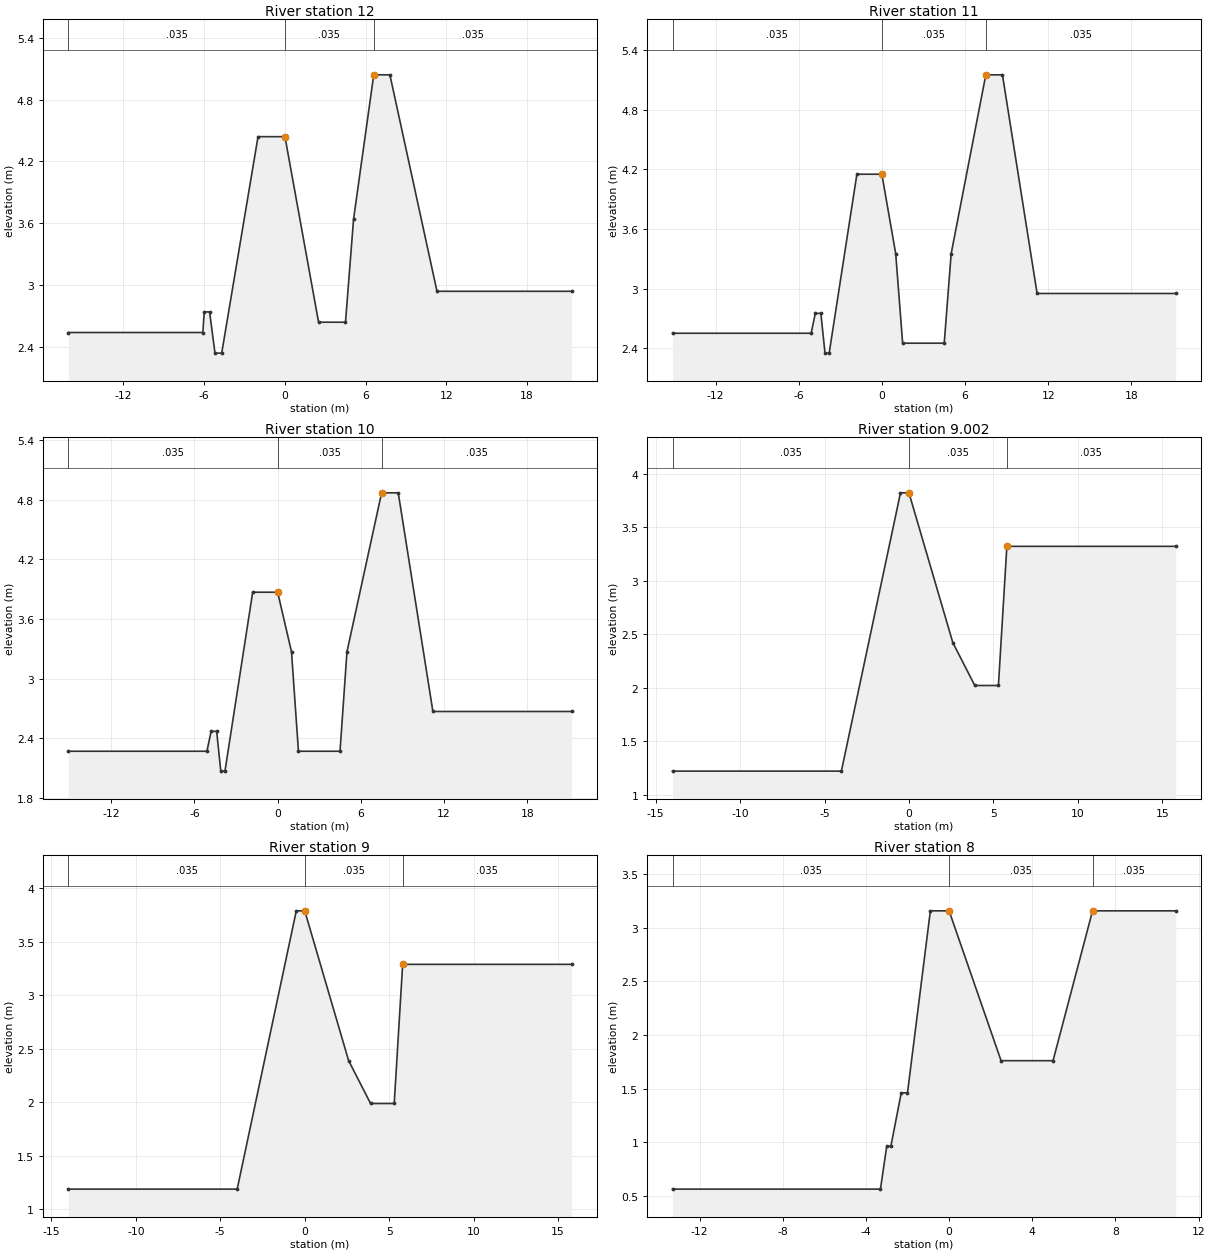
Type RM Length L Ch R = 1 ,12      ,50,50,50
#Sta/Elev= 15
   -16.1    2.54    -6.1    2.54      -6    2.74    -5.6    2.74    -5.2    2.34
    -4.7    2.34      -2    4.44       0    4.44     2.5    2.64     4.5    2.64
     5.1    3.64     6.6    5.04     7.8    5.04    11.3    2.94    21.3    2.94
#Mann= 3 , 0 , 0
   -16.1    .035       0       0    .035       0     6.6    .035       0
#XS Ineff= 2 , 0
               0      20     6.6              20
Permanent Ineff=
       F       F
#Block Obstruct= 2 , 0
                             6.6
Bank Sta=0,6.6
XS Rating Curve= 0
Exp/Cntr=.3,.1

Type RM Length L Ch R = 1 ,11      ,50,50,50
#Sta/Elev= 16
   -15.1    2.55    -5.1    2.55    -4.8    2.75    -4.4    2.75    -4.1    2.35
    -3.8    2.35    -1.8    4.15       0    4.15       1    3.35     1.5    2.45
     4.5    2.45       5    3.35     7.5    5.15     8.7    5.15    11.2    2.95
    21.2    2.95
#Mann= 3 , 0 , 0
   -15.1    .035       0       0    .035       0     7.5    .035       0
#XS Ineff= 2 , 0
               0      20     7.5              20
Permanent Ineff=
       F       F
#Block Obstruct= 2 , 0
                             7.5
Bank Sta=0,7.5
XS Rating Curve= 0
Exp/Cntr=.3,.1

Type RM Length L Ch R = 1 ,10      ,48,48,48
#Sta/Elev= 16
   -15.1    2.27    -5.1    2.27    -4.8    2.47    -4.4    2.47    -4.1    2.07
    -3.8    2.07    -1.8    3.87       0    3.87       1    3.27     1.5    2.27
     4.5    2.27       5    3.27     7.5    4.87     8.7    4.87    11.2    2.67
    21.2    2.67
#Mann= 3 , 0 , 0
   -15.1    .035       0       0    .035       0     7.5    .035       0
#XS Ineff= 2 , 0
               0      20     7.5              20
Permanent Ineff=
       F       F
#Block Obstruct= 2 , 0
                             7.5
Bank Sta=0,7.5
XS Rating Curve= 0
Exp/Cntr=.3,.1

Type RM Length L Ch R = 1 ,9.002   ,2,2,2
#Sta/Elev= 9
     -14    1.22      -4    1.22     -.5    3.82       0    3.82     2.6    2.42
     3.9    2.02     5.3    2.02     5.8    3.32    15.8    3.32
#Mann= 3 , 0 , 0
     -14    .035       0       0    .035       0     5.8    .035       0
#XS Ineff= 2 , 0
               0      20     5.8              20
Permanent Ineff=
       F       F
#Block Obstruct= 2 , 0
                             5.8
Bank Sta=0,5.8
XS Rating Curve= 0
Exp/Cntr=.3,.1

Type RM Length L Ch R = 1 ,9       ,50,50,50
#Sta/Elev= 9
     -14    1.19      -4    1.19     -.5    3.79       0    3.79     2.6    2.39
     3.9    1.99     5.3    1.99     5.8    3.29    15.8    3.29
#Mann= 3 , 0 , 0
     -14    .035       0       0    .035       0     5.8    .035       0
#XS Ineff= 2 , 0
               0      20     5.8              20
Permanent Ineff=
       F       F
#Block Obstruct= 2 , 0
                             5.8
Bank Sta=0,5.8
XS Rating Curve= 0
Exp/Cntr=.3,.1

Type RM Length L Ch R = 1 ,8       ,23,23,23
#Sta/Elev= 12
   -13.3     .56    -3.3     .56      -3     .96    -2.8     .96    -2.3    1.46
      -2    1.46     -.9    3.16       0    3.16     2.5    1.76       5    1.76
     6.9    3.16    10.9    3.16
#Mann= 3 , 0 , 0
   -13.3    .035       0       0    .035       0     6.9    .035       0
#XS Ineff= 2 , 0
               0      20     6.9              20
Permanent Ineff=
       F       F
#Block Obstruct= 2 , 0
                             6.9
Bank Sta=0,6.9
XS Rating Curve= 0
Exp/Cntr=.3,.1

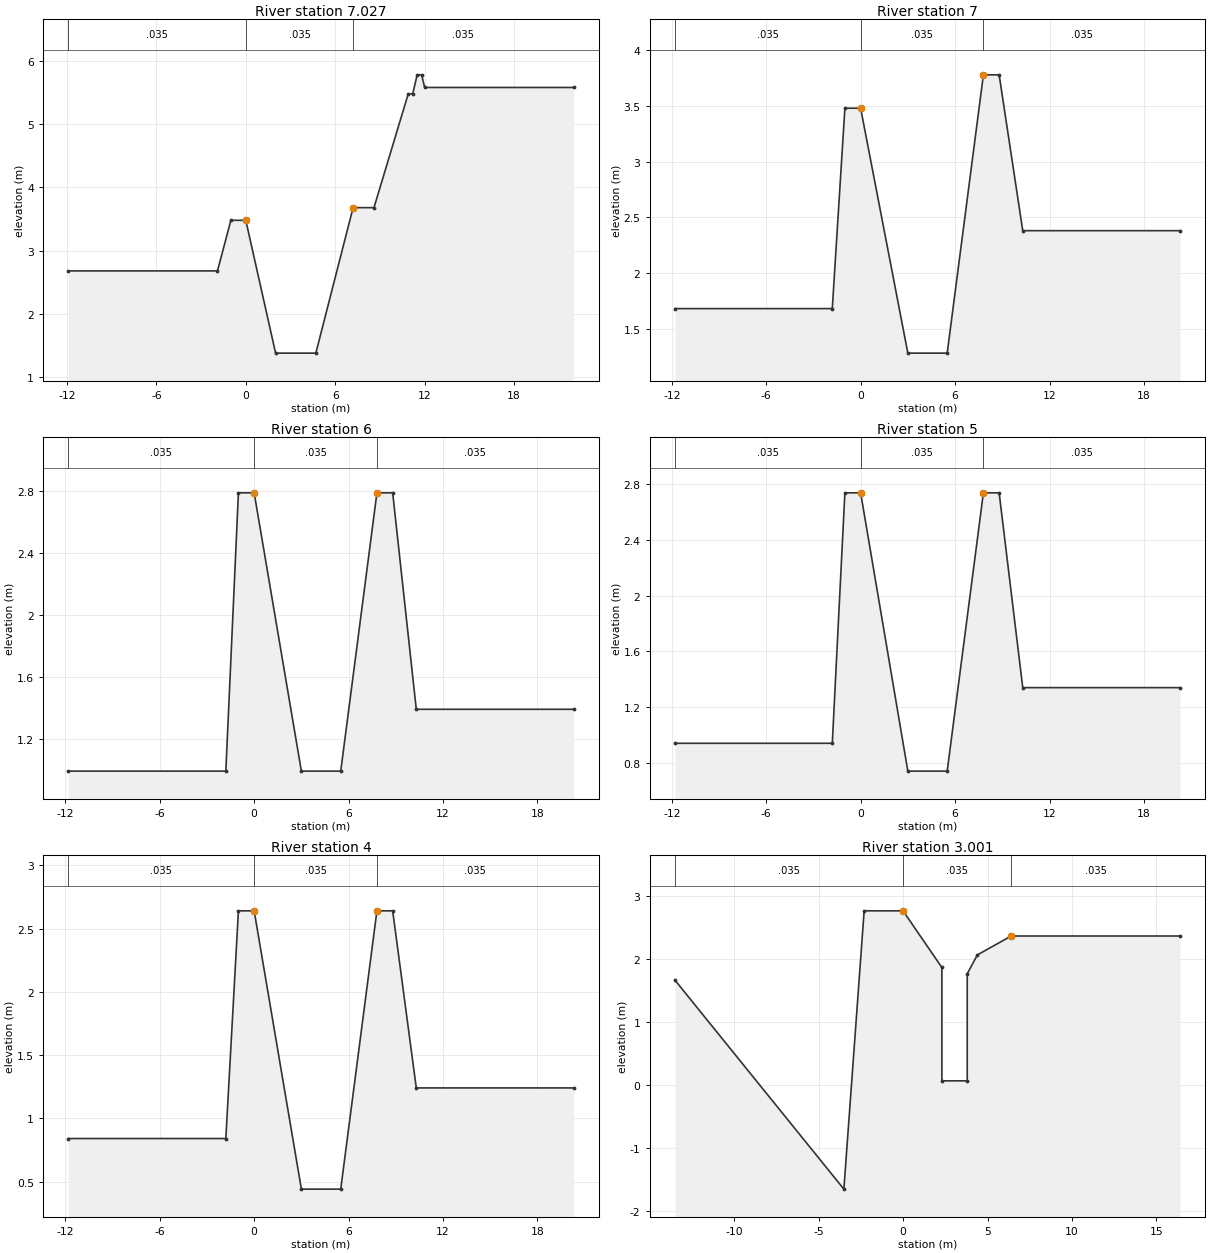
Type RM Length L Ch R = 1 ,7.027   ,27,27,27
#Sta/Elev= 14
   -11.9    2.68    -1.9    2.68      -1    3.48       0    3.48       2    1.38
     4.7    1.38     7.2    3.68     8.6    3.68    10.9    5.48    11.2    5.48
    11.5    5.78    11.8    5.78      12    5.58      22    5.58
#Mann= 3 , 0 , 0
   -11.9    .035       0       0    .035       0     7.2    .035       0
#XS Ineff= 2 , 0
               0      20     7.2              20
Permanent Ineff=
       F       F
#Block Obstruct= 2 , 0
                             7.2
Bank Sta=0,7.2
XS Rating Curve= 0
Exp/Cntr=.3,.1

Type RM Length L Ch R = 1 ,7       ,50,50,50
#Sta/Elev= 10
   -11.8    1.68    -1.8    1.68      -1    3.48       0    3.48       3    1.28
     5.5    1.28     7.8    3.78     8.8    3.78    10.3    2.38    20.3    2.38
#Mann= 3 , 0 , 0
   -11.8    .035       0       0    .035       0     7.8    .035       0
#XS Ineff= 2 , 0
               0      20     7.8              20
Permanent Ineff=
       F       F
#Block Obstruct= 2 , 0
                             7.8
Bank Sta=0,7.8
XS Rating Curve= 0
Exp/Cntr=.3,.1

Type RM Length L Ch R = 1 ,6       ,50,50,50
#Sta/Elev= 10
   -11.8     .99    -1.8     .99      -1    2.79       0    2.79       3     .99
     5.5     .99     7.8    2.79     8.8    2.79    10.3    1.39    20.3    1.39
#Mann= 3 , 0 , 0
   -11.8    .035       0       0    .035       0     7.8    .035       0
#XS Ineff= 2 , 0
               0      20     7.8              20
Permanent Ineff=
       F       F
#Block Obstruct= 2 , 0
                             7.8
Bank Sta=0,7.8
XS Rating Curve= 0
Exp/Cntr=.3,.1

Type RM Length L Ch R = 1 ,5       ,50,50,50
#Sta/Elev= 10
   -11.8     .94    -1.8     .94      -1    2.74       0    2.74       3     .74
     5.5     .74     7.8    2.74     8.8    2.74    10.3    1.34    20.3    1.34
#Mann= 3 , 0 , 0
   -11.8    .035       0       0    .035       0     7.8    .035       0
#XS Ineff= 2 , 0
               0      20     7.8              20
Permanent Ineff=
       F       F
#Block Obstruct= 2 , 0
                             7.8
Bank Sta=0,7.8
XS Rating Curve= 0
Exp/Cntr=.3,.1

Type RM Length L Ch R = 1 ,4       ,49,49,49
#Sta/Elev= 10
   -11.8     .84    -1.8     .84      -1    2.64       0    2.64       3     .44
     5.5     .44     7.8    2.64     8.8    2.64    10.3    1.24    20.3    1.24
#Mann= 3 , 0 , 0
   -11.8    .035       0       0    .035       0     7.8    .035       0
#XS Ineff= 2 , 0
               0      20     7.8              20
Permanent Ineff=
       F       F
#Block Obstruct= 2 , 0
                             7.8
Bank Sta=0,7.8
XS Rating Curve= 0
Exp/Cntr=.3,.1

Type RM Length L Ch R = 1 ,3.001   ,1,1,1
#Sta/Elev= 11
   -13.5    1.66    -3.5   -1.66    -2.3    2.76       0    2.76     2.3    1.86
     2.3     .06     3.8     .06     3.8    1.76     4.4    2.06     6.4    2.36
    16.4    2.36
#Mann= 3 , 0 , 0
   -13.5    .035       0       0    .035       0     6.4    .035       0
#XS Ineff= 2 , 0
               0      20     6.4              20
Permanent Ineff=
       F       F
#Block Obstruct= 2 , 0
                             7.4
Bank Sta=0,6.4
XS Rating Curve= 0
Exp/Cntr=.3,.1

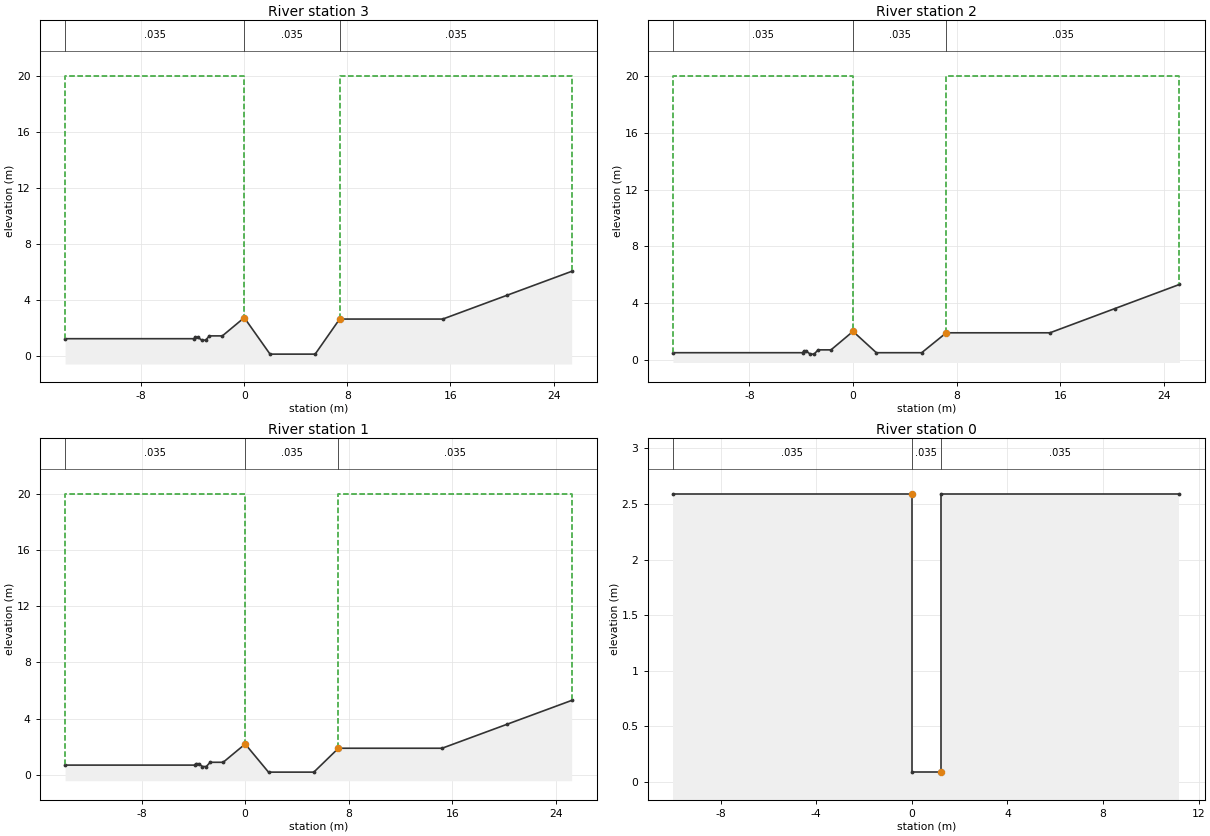
Type RM Length L Ch R = 1 ,3       ,50,50,50
#Sta/Elev= 15
   -13.9    1.26    -3.9    1.26    -3.8    1.36    -3.6    1.36    -3.3    1.16
      -3    1.16    -2.7    1.46    -1.7    1.46       0    2.76       2     .16
     5.5     .16     7.4    2.66    15.4    2.66    20.4    4.36    25.4    6.06
#Mann= 3 , 0 , 0
   -13.9    .035       0       0    .035       0     7.4    .035       0
#XS Ineff= 2 , 0
               0      20     7.4              20
Permanent Ineff=
       F       F
#Block Obstruct= 2 , 0
                             7.4
Bank Sta=0,7.4
XS Rating Curve= 0
Exp/Cntr=.3,.1

Type RM Length L Ch R = 1 ,2       ,50,50,50
#Sta/Elev= 15
   -13.9     .53    -3.9     .53    -3.8     .63    -3.6     .63    -3.3     .43
      -3     .43    -2.7     .73    -1.7     .73       0    2.03     1.8     .53
     5.3     .53     7.2    1.93    15.2    1.93    20.2    3.63    25.2    5.33
#Mann= 3 , 0 , 0
   -13.9    .035       0       0    .035       0     7.2    .035       0
#XS Ineff= 2 , 0
               0      20     7.2              20
Permanent Ineff=
       F       F
#Block Obstruct= 2 , 0
                             7.2
Bank Sta=0,7.2
XS Rating Curve= 0
Exp/Cntr=.3,.1

Type RM Length L Ch R = 1 ,1       ,50,50,50
#Sta/Elev= 15
   -13.9      .7    -3.9      .7    -3.8      .8    -3.6      .8    -3.3      .6
      -3      .6    -2.7      .9    -1.7      .9       0     2.2     1.8      .2
     5.3      .2     7.2     1.9    15.2     1.9    20.2     3.6    25.2     5.3
#Mann= 3 , 0 , 0
   -13.9    .035       0       0    .035       0     7.2    .035       0
#XS Ineff= 2 , 0
               0      20     7.2              20
Permanent Ineff=
       F       F
#Block Obstruct= 2 , 0
                             7.2
Bank Sta=0,7.2
XS Rating Curve= 0
Exp/Cntr=.3,.1

Type RM Length L Ch R = 1 ,0       ,0,0,0
#Sta/Elev= 6
     -10    2.59       0    2.59       0     .09     1.2     .09     1.2    2.59
    11.2    2.59
#Mann= 3 , 0 , 0
     -10    .035       0       0    .035       0     1.2    .035       0
#XS Ineff= 2 , 0
               0      20     1.2              20
Permanent Ineff=
       F       F
#Block Obstruct= 2 , 0
                             1.2
Bank Sta=0,1.2
XS Rating Curve= 0
Exp/Cntr=.3,.1

Chan Stop Cuts=-1