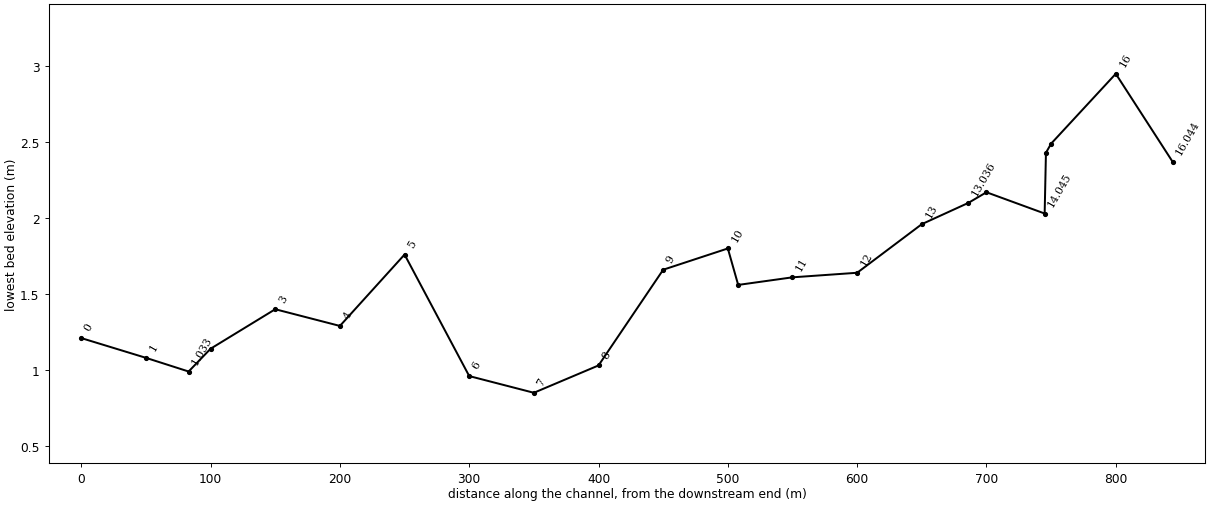
--- omc.prj (project) ---

Proj Title=oman
Current Plan=p01
Default Exp/Contr=.3,.1
SI Units
Geom File=g01
Flow File=f01
Plan File=p01
Y Axis Title=Elevation
X Axis Title(PF)=Main Channel Distance
X Axis Title(XS)=Station
BEGIN DESCRIPTION:
           BACK WATER COMPUTATION
      APPLICATION OF HEC-2 BY Samju Construction Engineering
      oman-ch: 10,20,30,50,80 yr
END DESCRIPTION:
DSS Export Rating Curves= 0
DSS Export Rating Curve Sorted= 0
DSS Export Volume Flow Curves= 0
DXF OffsetX= 0
DXF OffsetY= 0
DXF ScaleX= 1
DXF ScaleY= 10

--- omc.p01 (plan) ---

Plan Title=Imported Plan 01
Version=Version 3.0.1  Mar 2001
Short Identifier=Imported Pla
Geom File=g01
Flow File=f01
Subcritical Flow
K Sum by GR= 0
Std Step Tol= 0.003
Critical Tol= 0.003
Num of Std Step Trials= 20
Max Error Tol= 0.1
Flow Tol Ratio= 0.001
Split Flow NTrial= 30
Split Flow Tol= 0.02
Split Flow Ratio= 0.02
Log Output Level= 0
Friction Slope Method= 1
Unsteady Friction Slope Method= 2
Parabolic Critical Depth
Global Vel Dist= 0 , 0 , 0
Global Log Level= 0
CheckData=True
Encroach Param=-1 ,0,0, 0
Computation Interval=1HOUR
Output Interval=1HOUR
Run HTab= 0
Run UNet= 0
Run PostProcess= 0
UNET Theta= 1
UNET ZTol= 0.02
UNET ZSATol= 0.1
UNET MxIter= 20
UNET MaxInSteps= 20
UNET DtIC= 0
UNET DtMin= 0
UNET MaxCRTS= 20
UNET WFStab= 2
UNET SFStab= 1
UNET WFX= 1
UNET SFX= 1
UNET Convert EG Bridges=-1
UNET Use Existing IB Tables=-1
Instantaneous Interval=1HOUR
Write IC File= 0
Write Velocity= 0
Write Detailed= 0

--- omc.f01 (steady flow) ---

Flow Title=Imported Flow 01
Version=Version 3.0.1  Mar 2001
Number of Profiles= 5
Profile Names=10yr,20yr,30yr,50ry,80yr
River Rch & RM=RIVER-1,Reach-1         ,16.044
   22.13   24.38    25.7   27.37    28.9
River Rch & RM=OMAN,OMAN            ,16.044
   22.13   24.38    25.7   27.37    28.9
Boundary for River Rch & Prof#=OMAN,OMAN            , 1
Up Type= 0
Dn Type= 3
Dn Slope=.001
Boundary for River Rch & Prof#=OMAN,OMAN            , 2
Up Type= 0
Dn Type= 3
Dn Slope=.001
Boundary for River Rch & Prof#=OMAN,OMAN            , 3
Up Type= 0
Dn Type= 3
Dn Slope=.001
Boundary for River Rch & Prof#=OMAN,OMAN            , 4
Up Type= 0
Dn Type= 3
Dn Slope=.001
Boundary for River Rch & Prof#=OMAN,OMAN            , 5
Up Type= 0
Dn Type= 3
Dn Slope=.001
DSS Import GetInterval= 0
DSS Import GetPeak= 0
DSS Import FillOption= 0

--- omc.g01 (geometry) ---

Geom Title=Imported Geom 01
Version=Version 3.0.1  Mar 2001

River Reach=OMAN            ,OMAN
Reach XY= 2
              .5             .95              .5             .05

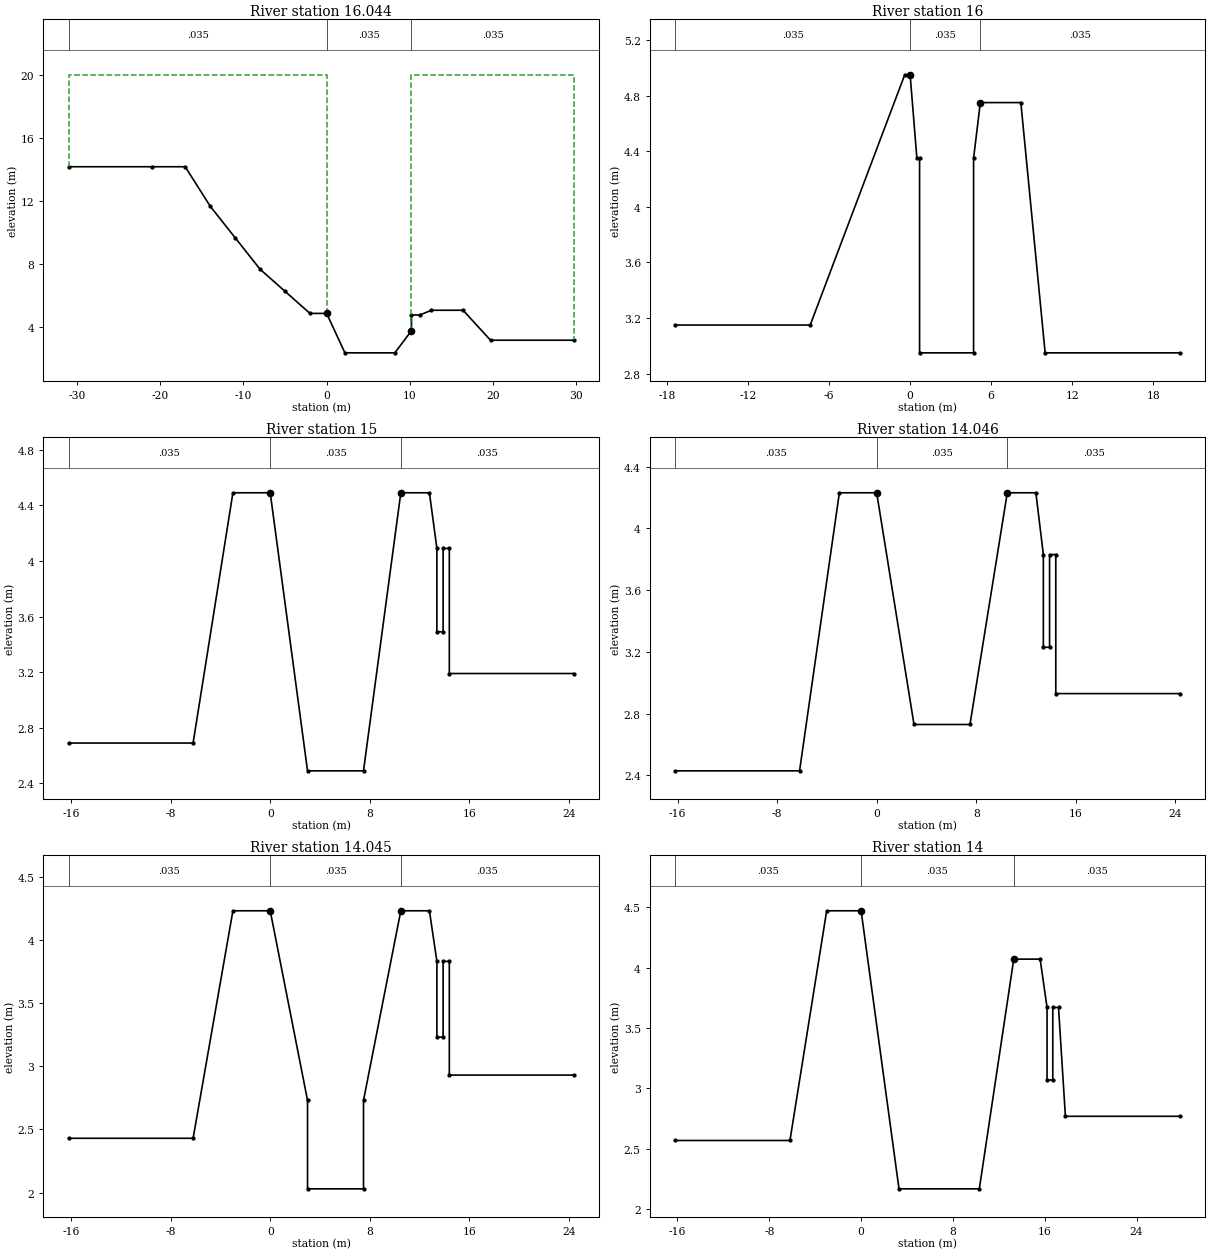
Type RM Length L Ch R = 1 ,16.044  ,44,44,44
#Sta/Elev= 18
     -31   14.17     -21   14.17     -17   14.17     -14   11.67     -11    9.67
      -8    7.67      -5    6.27      -2    4.87       0    4.87     2.2    2.37
     8.2    2.37    10.2    3.77    10.2    4.77    11.2    4.77    12.6    5.07
    16.4    5.07    19.7    3.17    29.7    3.17
#Mann= 3 , 0 , 0
     -31    .035       0       0    .035       0    10.2    .035       0
#XS Ineff= 2 , 0
               0      20    10.2              20
Permanent Ineff=
       F       F
#Block Obstruct= 2 , 0
                            10.2
Bank Sta=0,10.2
XS Rating Curve= 0
Exp/Cntr=.3,.1

Type RM Length L Ch R = 1 ,16      ,50,50,50
#Sta/Elev= 13
   -17.4    3.15    -7.4    3.15     -.4    4.95       0    4.95      .5    4.35
      .7    4.35      .7    2.95     4.7    2.95     4.7    4.35     5.2    4.75
     8.2    4.75      10    2.95      20    2.95
#Mann= 3 , 0 , 0
   -17.4    .035       0       0    .035       0     5.2    .035       0
#XS Ineff= 2 , 0
               0      20     5.2              20
Permanent Ineff=
       F       F
#Block Obstruct= 2 , 0
                             5.2
Bank Sta=0,5.2
XS Rating Curve= 0
Exp/Cntr=.3,.1

Type RM Length L Ch R = 1 ,15      ,4,4,4
#Sta/Elev= 15
   -16.2    2.69    -6.2    2.69      -3    4.49       0    4.49       3    2.49
     7.5    2.49    10.5    4.49    12.8    4.49    13.4    4.09    13.4    3.49
    13.9    3.49    13.9    4.09    14.4    4.09    14.4    3.19    24.4    3.19
#Mann= 3 , 0 , 0
   -16.2    .035       0       0    .035       0    10.5    .035       0
#XS Ineff= 2 , 0
               0      20    10.5              20
Permanent Ineff=
       F       F
#Block Obstruct= 2 , 0
                            10.5
Bank Sta=0,10.5
XS Rating Curve= 0
Exp/Cntr=.3,.1

Type RM Length L Ch R = 1 ,14.046  ,1,1,1
#Sta/Elev= 15
   -16.2    2.43    -6.2    2.43      -3    4.23       0    4.23       3    2.73
     7.5    2.73    10.5    4.23    12.8    4.23    13.4    3.83    13.4    3.23
    13.9    3.23    13.9    3.83    14.4    3.83    14.4    2.93    24.4    2.93
#Mann= 3 , 0 , 0
   -16.2    .035       0       0    .035       0    10.5    .035       0
#XS Ineff= 2 , 0
               0      20    10.5              20
Permanent Ineff=
       F       F
#Block Obstruct= 2 , 0
                            10.5
Bank Sta=0,10.5
XS Rating Curve= 0
Exp/Cntr=.3,.1

Type RM Length L Ch R = 1 ,14.045  ,45,45,45
#Sta/Elev= 17
   -16.2    2.43    -6.2    2.43      -3    4.23       0    4.23       3    2.73
       3    2.03     7.5    2.03     7.5    2.73    10.5    4.23    12.8    4.23
    13.4    3.83    13.4    3.23    13.9    3.23    13.9    3.83    14.4    3.83
    14.4    2.93    24.4    2.93
#Mann= 3 , 0 , 0
   -16.2    .035       0       0    .035       0    10.5    .035       0
#XS Ineff= 2 , 0
               0      20    10.5              20
Permanent Ineff=
       F       F
#Block Obstruct= 2 , 0
                            10.5
Bank Sta=0,10.5
XS Rating Curve= 0
Exp/Cntr=.3,.1

Type RM Length L Ch R = 1 ,14      ,14,14,14
#Sta/Elev= 15
   -16.2    2.57    -6.2    2.57      -3    4.47       0    4.47     3.3    2.17
    10.3    2.17    13.3    4.07    15.6    4.07    16.2    3.67    16.2    3.07
    16.7    3.07    16.7    3.67    17.2    3.67    17.8    2.77    27.8    2.77
#Mann= 3 , 0 , 0
   -16.2    .035       0       0    .035       0    13.3    .035       0
#XS Ineff= 2 , 0
               0      20    13.3              20
Permanent Ineff=
       F       F
#Block Obstruct= 2 , 0
                            13.3
Bank Sta=0,13.3
XS Rating Curve= 0
Exp/Cntr=.3,.1

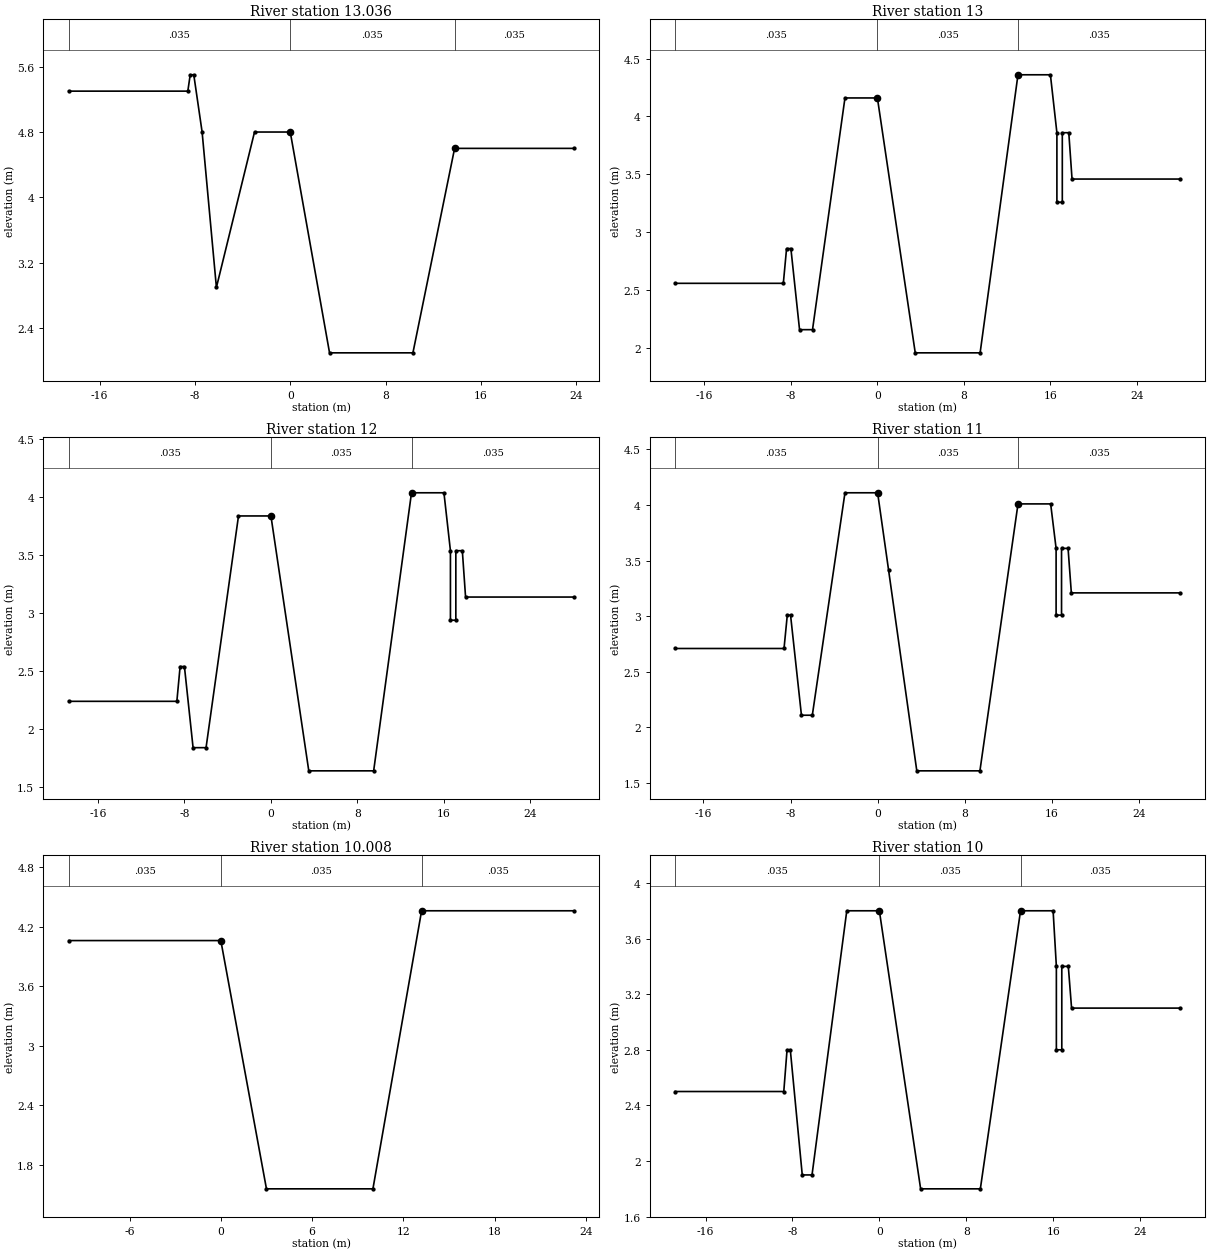
Type RM Length L Ch R = 1 ,13.036  ,36,36,36
#Sta/Elev= 12
   -18.6     5.3    -8.6     5.3    -8.4     5.5    -8.1     5.5    -7.4     4.8
    -6.2     2.9      -3     4.8       0     4.8     3.3     2.1    10.3     2.1
    13.8     4.6    23.8     4.6
#Mann= 3 , 0 , 0
   -18.6    .035       0       0    .035       0    13.8    .035       0
#XS Ineff= 2 , 0
               0      20    13.8              20
Permanent Ineff=
       F       F
#Block Obstruct= 2 , 0
                            13.8
Bank Sta=0,13.8
XS Rating Curve= 0
Exp/Cntr=.3,.1

Type RM Length L Ch R = 1 ,13      ,50,50,50
#Sta/Elev= 19
   -18.7    2.56    -8.7    2.56    -8.4    2.86      -8    2.86    -7.2    2.16
      -6    2.16      -3    4.16       0    4.16     3.5    1.96     9.5    1.96
      13    4.36      16    4.36    16.6    3.86    16.6    3.26    17.1    3.26
    17.1    3.86    17.7    3.86      18    3.46      28    3.46
#Mann= 3 , 0 , 0
   -18.7    .035       0       0    .035       0      13    .035       0
#XS Ineff= 2 , 0
               0      20      13              20
Permanent Ineff=
       F       F
#Block Obstruct= 2 , 0
                              13
Bank Sta=0,13
XS Rating Curve= 0
Exp/Cntr=.3,.1

Type RM Length L Ch R = 1 ,12      ,50,50,50
#Sta/Elev= 19
   -18.7    2.24    -8.7    2.24    -8.4    2.54      -8    2.54    -7.2    1.84
      -6    1.84      -3    3.84       0    3.84     3.5    1.64     9.5    1.64
      13    4.04      16    4.04    16.6    3.54    16.6    2.94    17.1    2.94
    17.1    3.54    17.7    3.54      18    3.14      28    3.14
#Mann= 3 , 0 , 0
   -18.7    .035       0       0    .035       0      13    .035       0
#XS Ineff= 2 , 0
               0      20      13              20
Permanent Ineff=
       F       F
#Block Obstruct= 2 , 0
                              13
Bank Sta=0,13
XS Rating Curve= 0
Exp/Cntr=.3,.1

Type RM Length L Ch R = 1 ,11      ,42,42,42
#Sta/Elev= 20
   -18.6    2.71    -8.6    2.71    -8.3    3.01      -8    3.01      -7    2.11
      -6    2.11      -3    4.11       0    4.11       1    3.42     3.6    1.61
     9.4    1.61    12.9    4.01    15.9    4.01    16.4    3.61    16.4    3.01
    16.9    3.01    16.9    3.61    17.5    3.61    17.8    3.21    27.8    3.21
#Mann= 3 , 0 , 0
   -18.6    .035       0       0    .035       0    12.9    .035       0
#XS Ineff= 2 , 0
               0      20    12.9              20
Permanent Ineff=
       F       F
#Block Obstruct= 2 , 0
                            12.9
Bank Sta=0,12.9
XS Rating Curve= 0
Exp/Cntr=.3,.1

Type RM Length L Ch R = 1 ,10.008  ,8,8,8
#Sta/Elev= 6
     -10    4.06       0    4.06       3    1.56      10    1.56    13.2    4.36
    23.2    4.36
#Mann= 3 , 0 , 0
     -10    .035       0       0    .035       0    13.2    .035       0
#XS Ineff= 2 , 0
               0      20    13.2              20
Permanent Ineff=
       F       F
#Block Obstruct= 2 , 0
                            13.2
Bank Sta=0,13.2
XS Rating Curve= 0
Exp/Cntr=.3,.1

Type RM Length L Ch R = 1 ,10      ,50,50,50
#Sta/Elev= 19
   -18.8     2.5    -8.8     2.5    -8.5     2.8    -8.2     2.8    -7.1     1.9
    -6.2     1.9      -3     3.8       0     3.8     3.8     1.8     9.3     1.8
      13     3.8      16     3.8    16.3     3.4    16.3     2.8    16.8     2.8
    16.8     3.4    17.4     3.4    17.7     3.1    27.7     3.1
#Mann= 3 , 0 , 0
   -18.8    .035       0       0    .035       0      13    .035       0
#XS Ineff= 2 , 0
               0      20      13              20
Permanent Ineff=
       F       F
#Block Obstruct= 2 , 0
                              13
Bank Sta=0,13
XS Rating Curve= 0
Exp/Cntr=.3,.1

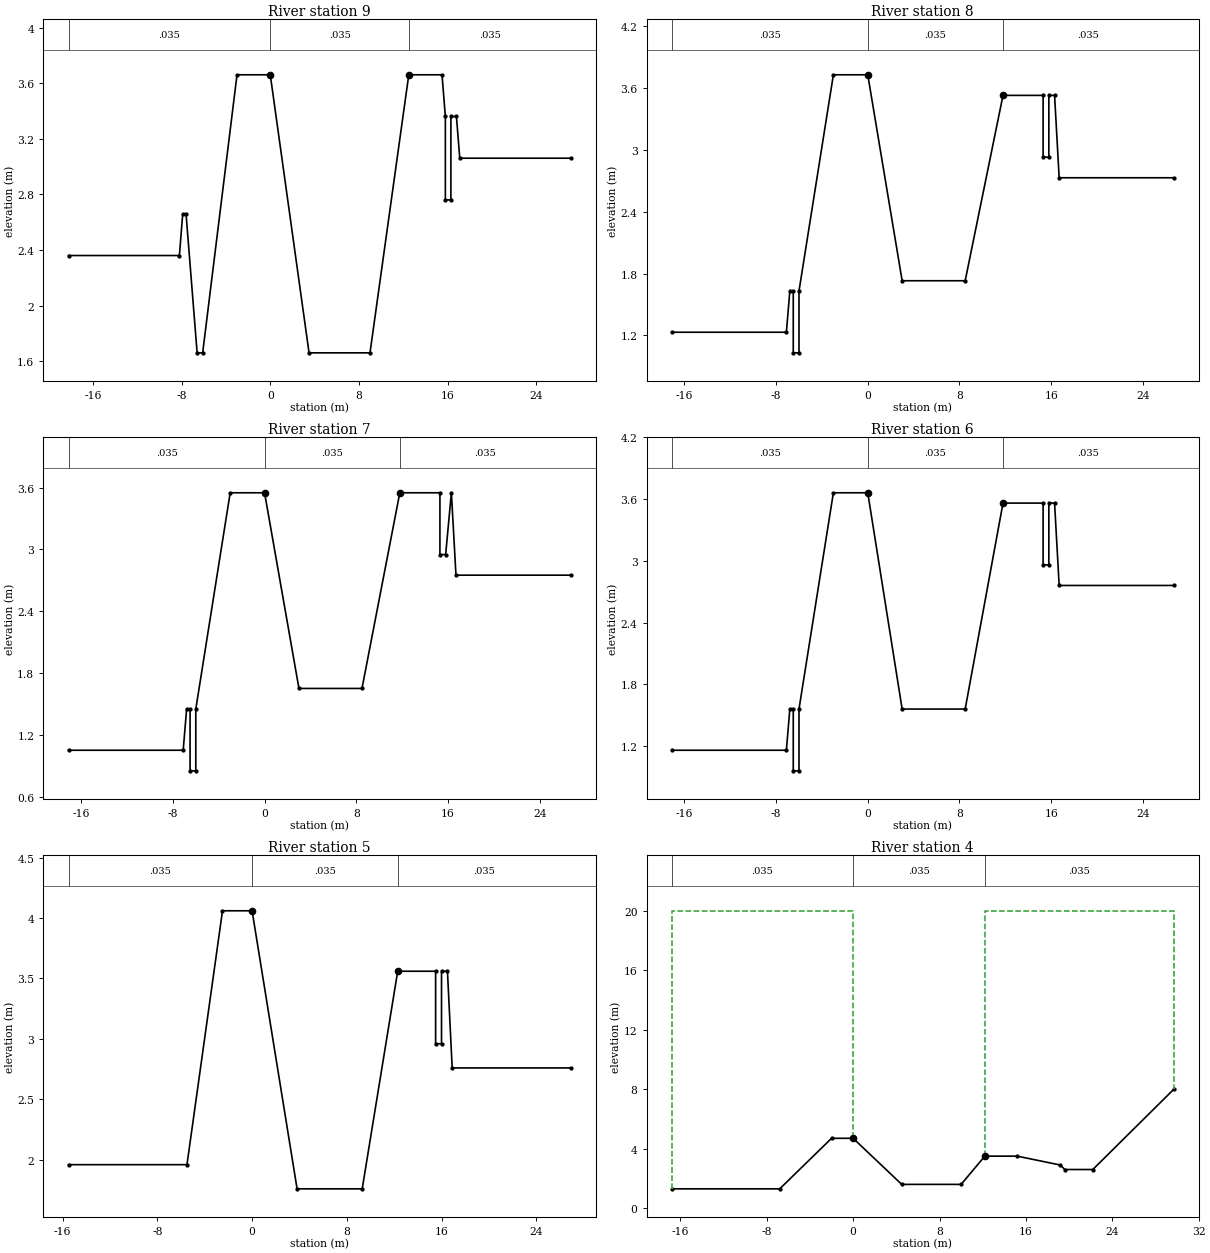
Type RM Length L Ch R = 1 ,9       ,50,50,50
#Sta/Elev= 19
   -18.2    2.36    -8.2    2.36    -7.9    2.66    -7.6    2.66    -6.6    1.66
    -6.1    1.66      -3    3.66       0    3.66     3.5    1.66       9    1.66
    12.5    3.66    15.5    3.66    15.8    3.36    15.8    2.76    16.3    2.76
    16.3    3.36    16.8    3.36    17.1    3.06    27.1    3.06
#Mann= 3 , 0 , 0
   -18.2    .035       0       0    .035       0    12.5    .035       0
#XS Ineff= 2 , 0
               0      20    12.5              20
Permanent Ineff=
       F       F
#Block Obstruct= 2 , 0
                            12.5
Bank Sta=0,12.5
XS Rating Curve= 0
Exp/Cntr=.3,.1

Type RM Length L Ch R = 1 ,8       ,50,50,50
#Sta/Elev= 19
   -17.1    1.23    -7.1    1.23    -6.8    1.63    -6.5    1.63    -6.5    1.03
      -6    1.03      -6    1.63      -3    3.73       0    3.73       3    1.73
     8.5    1.73    11.8    3.53    15.3    3.53    15.3    2.93    15.8    2.93
    15.8    3.53    16.3    3.53    16.7    2.73    26.7    2.73
#Mann= 3 , 0 , 0
   -17.1    .035       0       0    .035       0    11.8    .035       0
#XS Ineff= 2 , 0
               0      20    11.8              20
Permanent Ineff=
       F       F
#Block Obstruct= 2 , 0
                            11.8
Bank Sta=0,11.8
XS Rating Curve= 0
Exp/Cntr=.3,.1

Type RM Length L Ch R = 1 ,7       ,50,50,50
#Sta/Elev= 18
   -17.1    1.05    -7.1    1.05    -6.8    1.45    -6.5    1.45    -6.5     .85
      -6     .85      -6    1.45      -3    3.55       0    3.55       3    1.65
     8.5    1.65    11.8    3.55    15.3    3.55    15.3    2.95    15.8    2.95
    16.3    3.55    16.7    2.75    26.7    2.75
#Mann= 3 , 0 , 0
   -17.1    .035       0       0    .035       0    11.8    .035       0
#XS Ineff= 2 , 0
               0      20    11.8              20
Permanent Ineff=
       F       F
#Block Obstruct= 2 , 0
                            11.8
Bank Sta=0,11.8
XS Rating Curve= 0
Exp/Cntr=.3,.1

Type RM Length L Ch R = 1 ,6       ,50,50,50
#Sta/Elev= 19
   -17.1    1.16    -7.1    1.16    -6.8    1.56    -6.5    1.56    -6.5     .96
      -6     .96      -6    1.56      -3    3.66       0    3.66       3    1.56
     8.5    1.56    11.8    3.56    15.3    3.56    15.3    2.96    15.8    2.96
    15.8    3.56    16.3    3.56    16.7    2.76    26.7    2.76
#Mann= 3 , 0 , 0
   -17.1    .035       0       0    .035       0    11.8    .035       0
#XS Ineff= 2 , 0
               0      20    11.8              20
Permanent Ineff=
       F       F
#Block Obstruct= 2 , 0
                            11.8
Bank Sta=0,11.8
XS Rating Curve= 0
Exp/Cntr=.3,.1

Type RM Length L Ch R = 1 ,5       ,50,50,50
#Sta/Elev= 14
   -15.5    1.96    -5.5    1.96    -2.5    4.06       0    4.06     3.8    1.76
     9.3    1.76    12.3    3.56    15.5    3.56    15.5    2.96      16    2.96
      16    3.56    16.5    3.56    16.9    2.76    26.9    2.76
#Mann= 3 , 0 , 0
   -15.5    .035       0       0    .035       0    12.3    .035       0
#XS Ineff= 2 , 0
               0      20    12.3              20
Permanent Ineff=
       F       F
#Block Obstruct= 2 , 0
                            12.3
Bank Sta=0,12.3
XS Rating Curve= 0
Exp/Cntr=.3,.1

Type RM Length L Ch R = 1 ,4       ,50,50,50
#Sta/Elev= 12
   -16.8    1.29    -6.8    1.29      -2    4.69       0    4.69     4.5    1.59
      10    1.59    12.2    3.49    15.2    3.49    19.2    2.89    19.6    2.59
    22.2    2.59    29.7    7.99
#Mann= 3 , 0 , 0
   -16.8    .035       0       0    .035       0    12.2    .035       0
#XS Ineff= 2 , 0
               0      20    12.2              20
Permanent Ineff=
       F       F
#Block Obstruct= 2 , 0
                            12.2
Bank Sta=0,12.2
XS Rating Curve= 0
Exp/Cntr=.3,.1

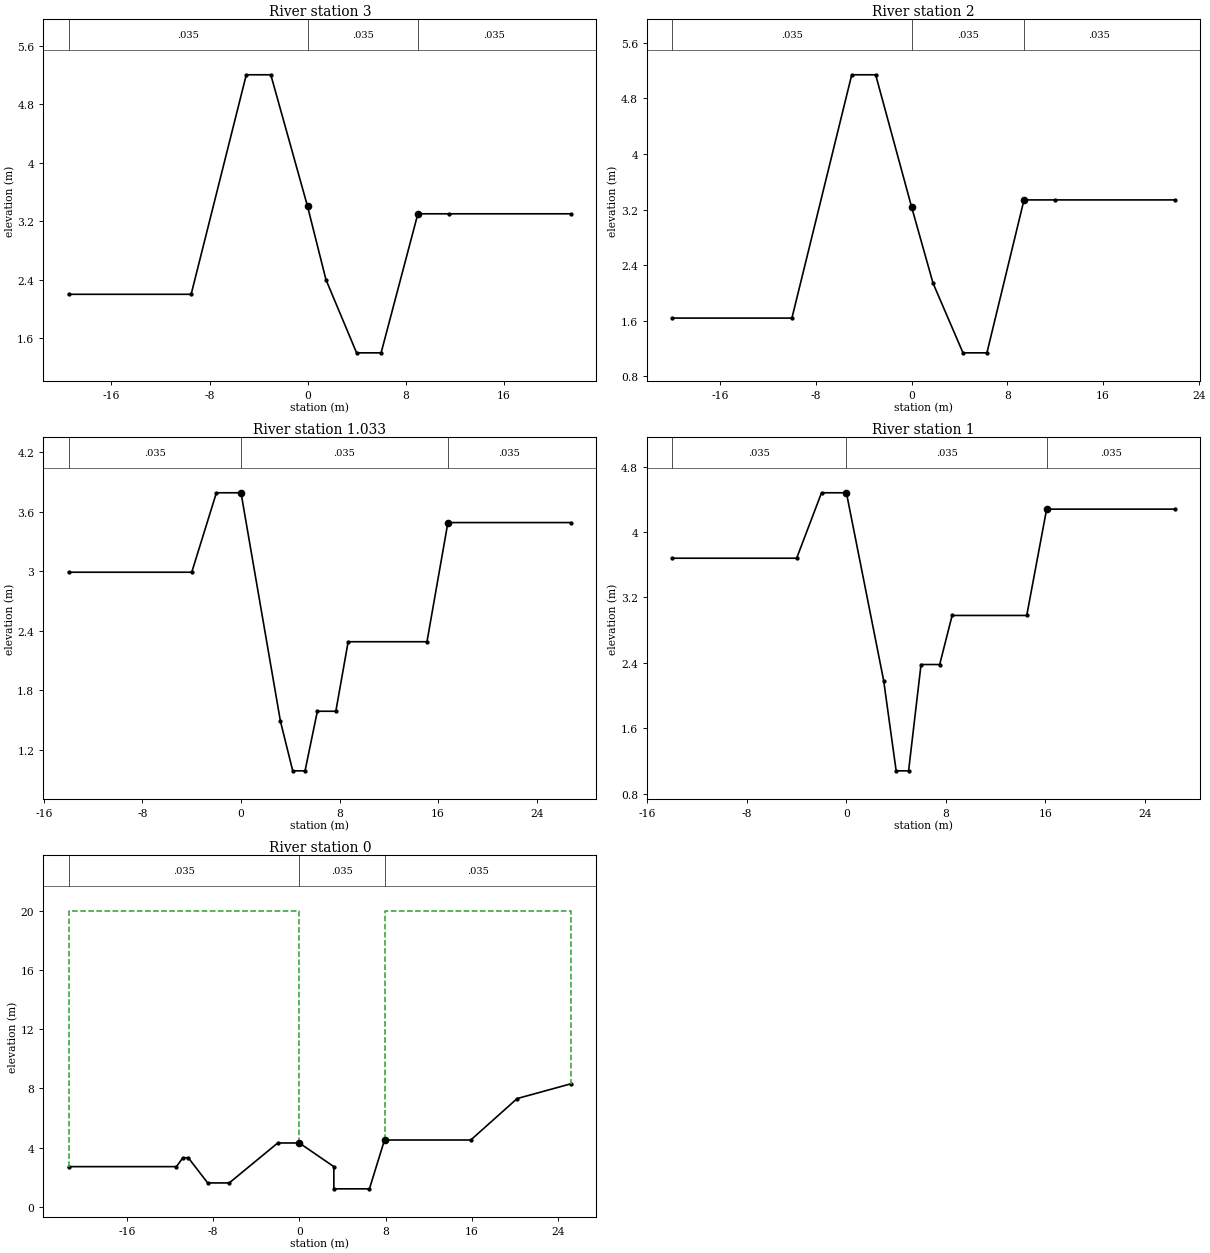
Type RM Length L Ch R = 1 ,3       ,50,50,50
#Sta/Elev= 11
   -19.5     2.2    -9.5     2.2      -5     5.2      -3     5.2       0     3.4
     1.5     2.4       4     1.4       6     1.4       9     3.3    11.5     3.3
    21.5     3.3
#Mann= 3 , 0 , 0
   -19.5    .035       0       0    .035       0       9    .035       0
#XS Ineff= 2 , 0
               0      20       9              20
Permanent Ineff=
       F       F
#Block Obstruct= 2 , 0
                               9
Bank Sta=0,9
XS Rating Curve= 0
Exp/Cntr=.3,.1

Type RM Length L Ch R = 1 ,2       ,17,17,17
#Sta/Elev= 11
     -20    1.64     -10    1.64      -5    5.14      -3    5.14       0    3.24
     1.8    2.14     4.3    1.14     6.3    1.14     9.4    3.34      12    3.34
      22    3.34
#Mann= 3 , 0 , 0
     -20    .035       0       0    .035       0     9.4    .035       0
#XS Ineff= 2 , 0
               0      20     9.4              20
Permanent Ineff=
       F       F
#Block Obstruct= 2 , 0
                             9.4
Bank Sta=0,9.4
XS Rating Curve= 0
Exp/Cntr=.3,.1

Type RM Length L Ch R = 1 ,1.033   ,33,33,33
#Sta/Elev= 13
     -14    2.99      -4    2.99      -2    3.79       0    3.79     3.2    1.49
     4.2     .99     5.2     .99     6.2    1.59     7.7    1.59     8.7    2.29
    15.1    2.29    16.8    3.49    26.8    3.49
#Mann= 3 , 0 , 0
     -14    .035       0       0    .035       0    16.8    .035       0
#XS Ineff= 2 , 0
               0      20    16.8              20
Permanent Ineff=
       F       F
#Block Obstruct= 2 , 0
                            16.8
Bank Sta=0,16.8
XS Rating Curve= 0
Exp/Cntr=.3,.1

Type RM Length L Ch R = 1 ,1       ,50,50,50
#Sta/Elev= 13
     -14    3.68      -4    3.68      -2    4.48       0    4.48       3    2.18
       4    1.08       5    1.08       6    2.38     7.5    2.38     8.5    2.98
    14.5    2.98    16.1    4.28    26.4    4.28
#Mann= 3 , 0 , 0
     -14    .035       0       0    .035       0    16.1    .035       0
#XS Ineff= 2 , 0
               0      20    16.1              20
Permanent Ineff=
       F       F
#Block Obstruct= 2 , 0
                            16.1
Bank Sta=0,16.1
XS Rating Curve= 0
Exp/Cntr=.3,.1

Type RM Length L Ch R = 1 ,0       ,0,0,0
#Sta/Elev= 15
   -21.4    2.71   -11.4    2.71   -10.8    3.31   -10.3    3.31    -8.5    1.61
    -6.5    1.61      -2    4.31       0    4.31     3.2    2.71     3.2    1.21
     6.5    1.21     7.9    4.51    15.9    4.51    20.2    7.31    25.2    8.31
#Mann= 3 , 0 , 0
   -21.4    .035       0       0    .035       0     7.9    .035       0
#XS Ineff= 2 , 0
               0      20     7.9              20
Permanent Ineff=
       F       F
#Block Obstruct= 2 , 0
                             7.9
Bank Sta=0,7.9
XS Rating Curve= 0
Exp/Cntr=.3,.1

Chan Stop Cuts=-1