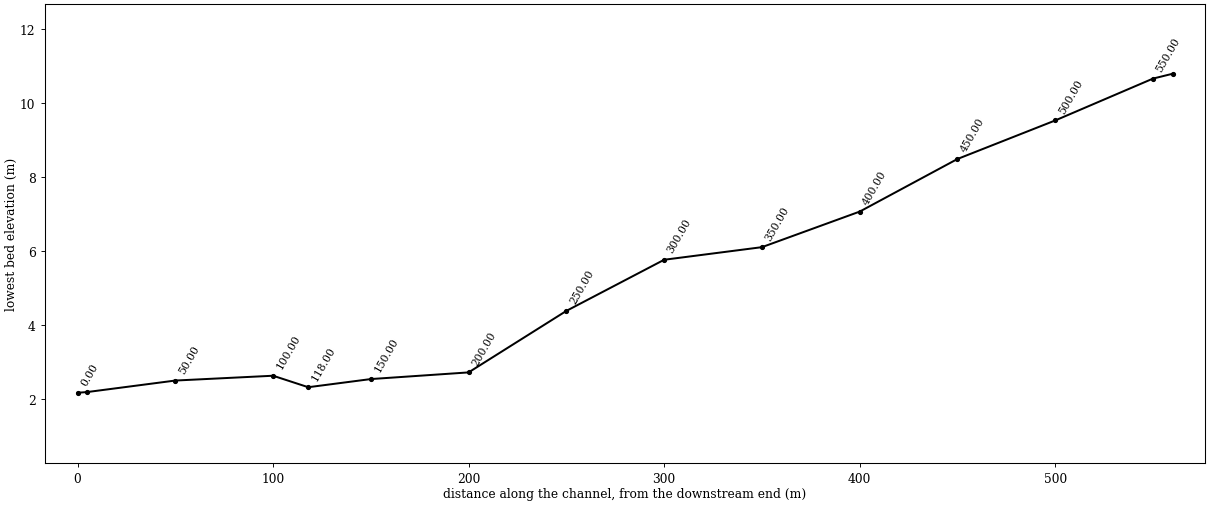
--- shc.prj (project) ---

Proj Title=suhang
Current Plan=p02
Default Exp/Contr=.3,.1
SI Units
Geom File=g02
Geom File=g01
Flow File=f02
Flow File=f01
Plan File=p02
Plan File=p01
Y Axis Title=Elevation
X Axis Title(PF)=Main Channel Distance
X Axis Title(XS)=Station
BEGIN DESCRIPTION:
           BACK WATER COMPUTATION
      APPLICATION OF HEC-2 BY Samju Construction Engineering
      suhang-ch: 10,20,30,50,80 yr
           BACK WATER COMPUTATION
      APPLICATION OF HEC-2 BY Samju Construction Engineering
      suhang-ch: 10,20,30,50,80 yr
END DESCRIPTION:
DSS Export Rating Curves= 0
DSS Export Rating Curve Sorted= 0
DSS Export Volume Flow Curves= 0
DXF OffsetX= 0
DXF OffsetY= 0
DXF ScaleX= 1
DXF ScaleY= 10

--- shc.p02 (plan) ---

Plan Title=Imported Plan 02
Version=Version 3.0.1  Mar 2001
Short Identifier=Imported Pla
Geom File=g02
Flow File=f02
Subcritical Flow
K Sum by GR= 0
Std Step Tol= 0.003
Critical Tol= 0.003
Num of Std Step Trials= 20
Max Error Tol= 0.1
Flow Tol Ratio= 0.001
Split Flow NTrial= 30
Split Flow Tol= 0.02
Split Flow Ratio= 0.02
Log Output Level= 0
Friction Slope Method= 1
Unsteady Friction Slope Method= 2
Parabolic Critical Depth
Global Vel Dist= 0 , 0 , 0
Global Log Level= 0
CheckData=True
Encroach Param=-1 ,0,0, 0
Computation Interval=1HOUR
Output Interval=1HOUR
Run HTab= 0
Run UNet= 0
Run PostProcess= 0
UNET Theta= 1
UNET ZTol= 0.02
UNET ZSATol= 0.1
UNET MxIter= 20
UNET MaxInSteps= 20
UNET DtIC= 0
UNET DtMin= 0
UNET MaxCRTS= 20
UNET WFStab= 2
UNET SFStab= 1
UNET WFX= 1
UNET SFX= 1
UNET Convert EG Bridges=-1
UNET Use Existing IB Tables=-1
Instantaneous Interval=1HOUR
Write IC File= 0
Write Velocity= 0
Write Detailed= 0

--- shc.p01 (plan) ---

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Plan Title=Imported Plan 01
Geom File=g01
Flow File=f01

--- shc.f02 (steady flow) ---

Flow Title=Imported Flow 02
Version=Version 3.0.1  Mar 2001
Number of Profiles= 5
Profile Names=10yr,20yr,30ry,50yr,80yr
River Rch & RM=RIVER-1,Reach-1         ,560.00
    4.47    4.93    5.19    5.53    5.84
Boundary for River Rch & Prof#=RIVER-1,Reach-1         , 1
Up Type= 0
Dn Type= 3
Dn Slope=.011
Boundary for River Rch & Prof#=RIVER-1,Reach-1         , 2
Up Type= 0
Dn Type= 3
Dn Slope=.011
Boundary for River Rch & Prof#=RIVER-1,Reach-1         , 3
Up Type= 0
Dn Type= 3
Dn Slope=.011
Boundary for River Rch & Prof#=RIVER-1,Reach-1         , 4
Up Type= 0
Dn Type= 3
Dn Slope=.011
Boundary for River Rch & Prof#=RIVER-1,Reach-1         , 5
Up Type= 0
Dn Type= 3
Dn Slope=.011
DSS Import GetInterval= 0
DSS Import GetPeak= 0
DSS Import FillOption= 0

--- shc.f01 (steady flow) ---

Flow Title=Imported Flow 01
Version=Version 3.0.1  Mar 2001
Number of Profiles= 5
Profile Names=PF 1,PF 2,PF 3,PF 4,PF 5
River Rch & RM=RIVER-1,Reach-1         ,16
     180     200     220     230     240
Boundary for River Rch & Prof#=RIVER-1,Reach-1         , 1
Up Type= 0
Dn Type= 3
Dn Slope=.0109
Boundary for River Rch & Prof#=RIVER-1,Reach-1         , 2
Up Type= 0
Dn Type= 3
Dn Slope=.0109
Boundary for River Rch & Prof#=RIVER-1,Reach-1         , 3
Up Type= 0
Dn Type= 3
Dn Slope=.0109
Boundary for River Rch & Prof#=RIVER-1,Reach-1         , 4
Up Type= 0
Dn Type= 3
Dn Slope=.0109
Boundary for River Rch & Prof#=RIVER-1,Reach-1         , 5
Up Type= 0
Dn Type= 3
Dn Slope=.0109
DSS Import GetInterval= 0
DSS Import GetPeak= 0
DSS Import FillOption= 0

--- shc.g02 (geometry) ---

Geom Title=Imported Geom 02
Version=Version 3.0.1  Mar 2001

River Reach=RIVER-1         ,Reach-1
Reach XY= 2
              .5             .95              .5             .05

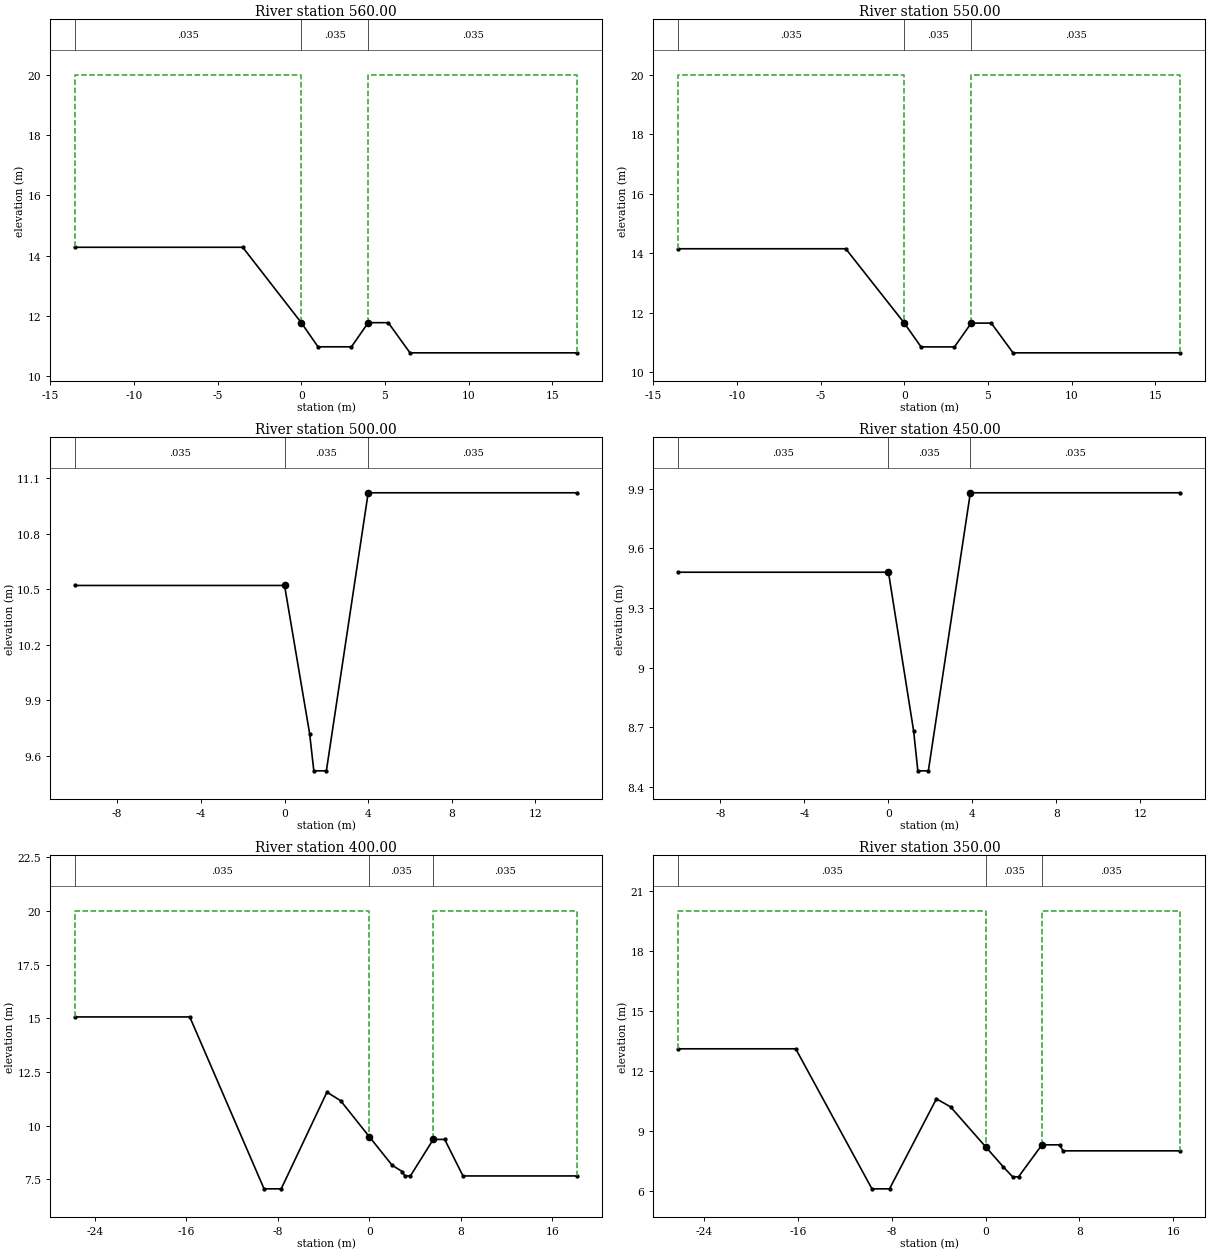
Type RM Length L Ch R = 1 ,560.00  ,10,10,10
BEGIN DESCRIPTION:
11.01
END DESCRIPTION:
#Sta/Elev= 9
   -13.5   14.28    -3.5   14.28       0   11.78       1   10.98       3   10.98
       4   11.78     5.2   11.78     6.5   10.78    16.5   10.78
#Mann= 3 , 0 , 0
   -13.5    .035       0       0    .035       0       4    .035       0
#XS Ineff= 2 , 0
               0      20       4              20
Permanent Ineff=
       F       F
#Block Obstruct= 2 , 0
                               4
Bank Sta=0,4
XS Rating Curve= 0
Exp/Cntr=.3,.1

Type RM Length L Ch R = 1 ,550.00  ,50,50,50
BEGIN DESCRIPTION:
11
END DESCRIPTION:
#Sta/Elev= 9
   -13.5   14.15    -3.5   14.15       0   11.65       1   10.85       3   10.85
       4   11.65     5.2   11.65     6.5   10.65    16.5   10.65
#Mann= 3 , 0 , 0
   -13.5    .035       0       0    .035       0       4    .035       0
#XS Ineff= 2 , 0
               0      20       4              20
Permanent Ineff=
       F       F
#Block Obstruct= 2 , 0
                               4
Bank Sta=0,4
XS Rating Curve= 0
Exp/Cntr=.3,.1

Type RM Length L Ch R = 1 ,500.00  ,50,50,50
BEGIN DESCRIPTION:
10
END DESCRIPTION:
#Sta/Elev= 7
     -10   10.52       0   10.52     1.2    9.72     1.4    9.52       2    9.52
       4   11.02      14   11.02
#Mann= 3 , 0 , 0
     -10    .035       0       0    .035       0       4    .035       0
#XS Ineff= 2 , 0
               0      20       4              20
Permanent Ineff=
       F       F
#Block Obstruct= 2 , 0
                               4
Bank Sta=0,4
XS Rating Curve= 0
Exp/Cntr=.3,.1

Type RM Length L Ch R = 1 ,450.00  ,50,50,50
BEGIN DESCRIPTION:
9
END DESCRIPTION:
#Sta/Elev= 7
     -10    9.48       0    9.48     1.2    8.68     1.4    8.48     1.9    8.48
     3.9    9.88    13.9    9.88
#Mann= 3 , 0 , 0
     -10    .035       0       0    .035       0     3.9    .035       0
#XS Ineff= 2 , 0
               0      20     3.9              20
Permanent Ineff=
       F       F
#Block Obstruct= 2 , 0
                             3.9
Bank Sta=0,3.9
XS Rating Curve= 0
Exp/Cntr=.3,.1

Type RM Length L Ch R = 1 ,400.00  ,50,50,50
BEGIN DESCRIPTION:
8
END DESCRIPTION:
#Sta/Elev= 15
   -25.7   15.06   -15.7   15.06    -9.2    7.06    -7.7    7.06    -3.7   11.56
    -2.5   11.16       0    9.49       2    8.16     2.9    7.86     3.1    7.66
     3.6    7.66     5.6    9.36     6.6    9.36     8.2    7.66    18.2    7.66
#Mann= 3 , 0 , 0
   -25.7    .035       0       0    .035       0     5.6    .035       0
#XS Ineff= 2 , 0
               0      20     5.6              20
Permanent Ineff=
       F       F
#Block Obstruct= 2 , 0
                             5.6
Bank Sta=0,5.6
XS Rating Curve= 0
Exp/Cntr=.3,.1

Type RM Length L Ch R = 1 ,350.00  ,50,50,50
BEGIN DESCRIPTION:
7
END DESCRIPTION:
#Sta/Elev= 14
   -26.2    13.1   -16.2    13.1    -9.7     6.1    -8.2     6.1    -4.2    10.6
      -3    10.2       0     8.2     1.5     7.2     2.3     6.7     2.8     6.7
     4.8     8.3     6.3     8.3     6.6       8    16.6       8
#Mann= 3 , 0 , 0
   -26.2    .035       0       0    .035       0     4.8    .035       0
#XS Ineff= 2 , 0
               0      20     4.8              20
Permanent Ineff=
       F       F
#Block Obstruct= 2 , 0
                             4.8
Bank Sta=0,4.8
XS Rating Curve= 0
Exp/Cntr=.3,.1

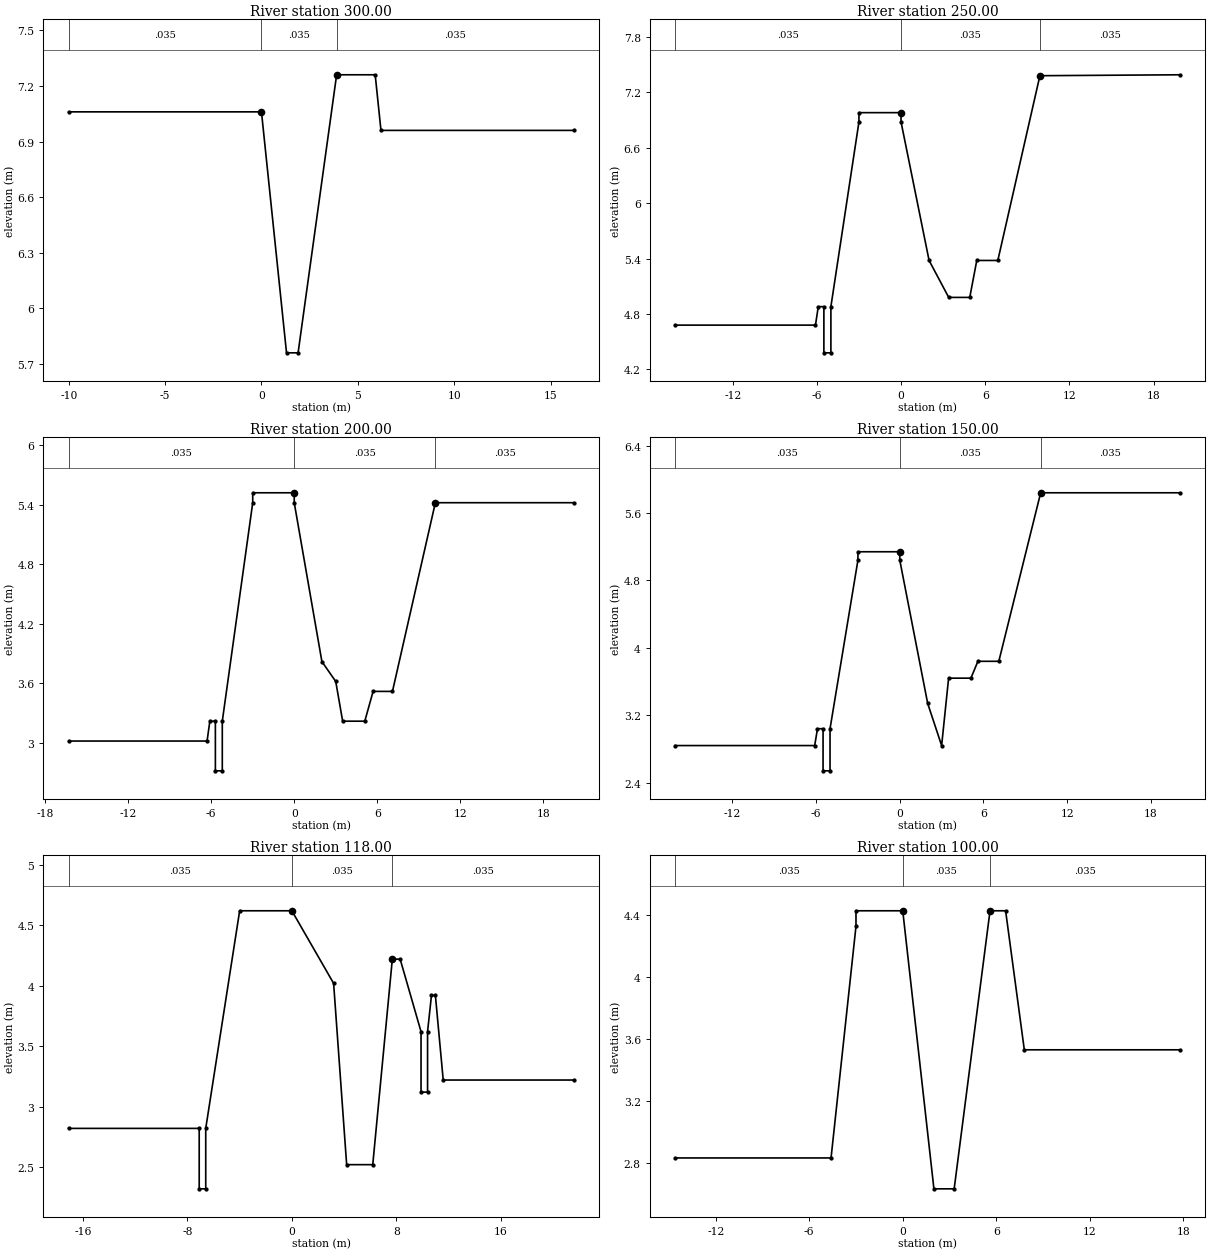
Type RM Length L Ch R = 1 ,300.00  ,50,50,50
BEGIN DESCRIPTION:
6
END DESCRIPTION:
#Sta/Elev= 8
     -10    7.06       0    7.06     1.3    5.76     1.9    5.76     3.9    7.26
     5.9    7.26     6.2    6.96    16.2    6.96
#Mann= 3 , 0 , 0
     -10    .035       0       0    .035       0     3.9    .035       0
#XS Ineff= 2 , 0
               0      20     3.9              20
Permanent Ineff=
       F       F
#Block Obstruct= 2 , 0
                             3.9
Bank Sta=0,3.9
XS Rating Curve= 0
Exp/Cntr=.3,.1

Type RM Length L Ch R = 1 ,250.00  ,50,50,50
BEGIN DESCRIPTION:
5
END DESCRIPTION:
#Sta/Elev= 18
   -16.1    4.68    -6.1    4.68    -5.9    4.88    -5.5    4.88    -5.5    4.38
      -5    4.38      -5    4.88      -3    6.88      -3    6.98       0    6.98
       0    6.88       2    5.38     3.4    4.98     4.9    4.98     5.4    5.38
     6.9    5.38     9.9    7.38    19.9    7.39
#Mann= 3 , 0 , 0
   -16.1    .035       0       0    .035       0     9.9    .035       0
#XS Ineff= 2 , 0
               0      20     9.9              20
Permanent Ineff=
       F       F
#Block Obstruct= 2 , 0
                             9.9
Bank Sta=0,9.9
XS Rating Curve= 0
Exp/Cntr=.3,.1

Type RM Length L Ch R = 1 ,200.00  ,50,50,50
BEGIN DESCRIPTION:
4
END DESCRIPTION:
#Sta/Elev= 19
   -16.3    3.02    -6.3    3.02    -6.1    3.22    -5.7    3.22    -5.7    2.72
    -5.2    2.72    -5.2    3.22      -3    5.42      -3    5.52       0    5.52
       0    5.42       2    3.82       3    3.62     3.5    3.22     5.1    3.22
     5.7    3.52     7.1    3.52    10.2    5.42    20.2    5.42
#Mann= 3 , 0 , 0
   -16.3    .035       0       0    .035       0    10.2    .035       0
#XS Ineff= 2 , 0
               0      20    10.2              20
Permanent Ineff=
       F       F
#Block Obstruct= 2 , 0
                            10.2
Bank Sta=0,10.2
XS Rating Curve= 0
Exp/Cntr=.3,.1

Type RM Length L Ch R = 1 ,150.00  ,32,32,32
BEGIN DESCRIPTION:
3
END DESCRIPTION:
#Sta/Elev= 19
   -16.1    2.84    -6.1    2.84    -5.9    3.04    -5.5    3.04    -5.5    2.54
      -5    2.54      -5    3.04      -3    5.04      -3    5.14       0    5.14
       0    5.04       2    3.34       3    2.84     3.5    3.64     5.1    3.64
     5.6    3.84     7.1    3.84    10.1    5.84    20.1    5.84
#Mann= 3 , 0 , 0
   -16.1    .035       0       0    .035       0    10.1    .035       0
#XS Ineff= 2 , 0
               0      20    10.1              20
Permanent Ineff=
       F       F
#Block Obstruct= 2 , 0
                            10.1
Bank Sta=0,10.1
XS Rating Curve= 0
Exp/Cntr=.3,.1

Type RM Length L Ch R = 1 ,118.00  ,18,18,18
BEGIN DESCRIPTION:
2.018
END DESCRIPTION:
#Sta/Elev= 20
   -17.1    2.82    -7.1    2.82    -7.1    2.32    -6.6    2.32    -6.6    2.82
      -4    4.62       0    4.62     3.2    4.02     4.2    2.52     6.2    2.52
     7.7    4.22     8.3    4.22     9.9    3.62     9.9    3.12    10.4    3.12
    10.4    3.62    10.7    3.92      11    3.92    11.6    3.22    21.6    3.22
#Mann= 3 , 0 , 0
   -17.1    .035       0       0    .035       0     7.7    .035       0
#XS Ineff= 2 , 0
               0      20     7.7              20
Permanent Ineff=
       F       F
#Block Obstruct= 2 , 0
                             7.7
Bank Sta=0,7.7
XS Rating Curve= 0
Exp/Cntr=.3,.1

Type RM Length L Ch R = 1 ,100.00  ,50,50,50
BEGIN DESCRIPTION:
2
END DESCRIPTION:
#Sta/Elev= 11
   -14.6    2.83    -4.6    2.83      -3    4.33      -3    4.43       0    4.43
       2    2.63     3.3    2.63     5.6    4.43     6.6    4.43     7.8    3.53
    17.8    3.53
#Mann= 3 , 0 , 0
   -14.6    .035       0       0    .035       0     5.6    .035       0
#XS Ineff= 2 , 0
               0      20     5.6              20
Permanent Ineff=
       F       F
#Block Obstruct= 2 , 0
                             5.6
Bank Sta=0,5.6
XS Rating Curve= 0
Exp/Cntr=.3,.1

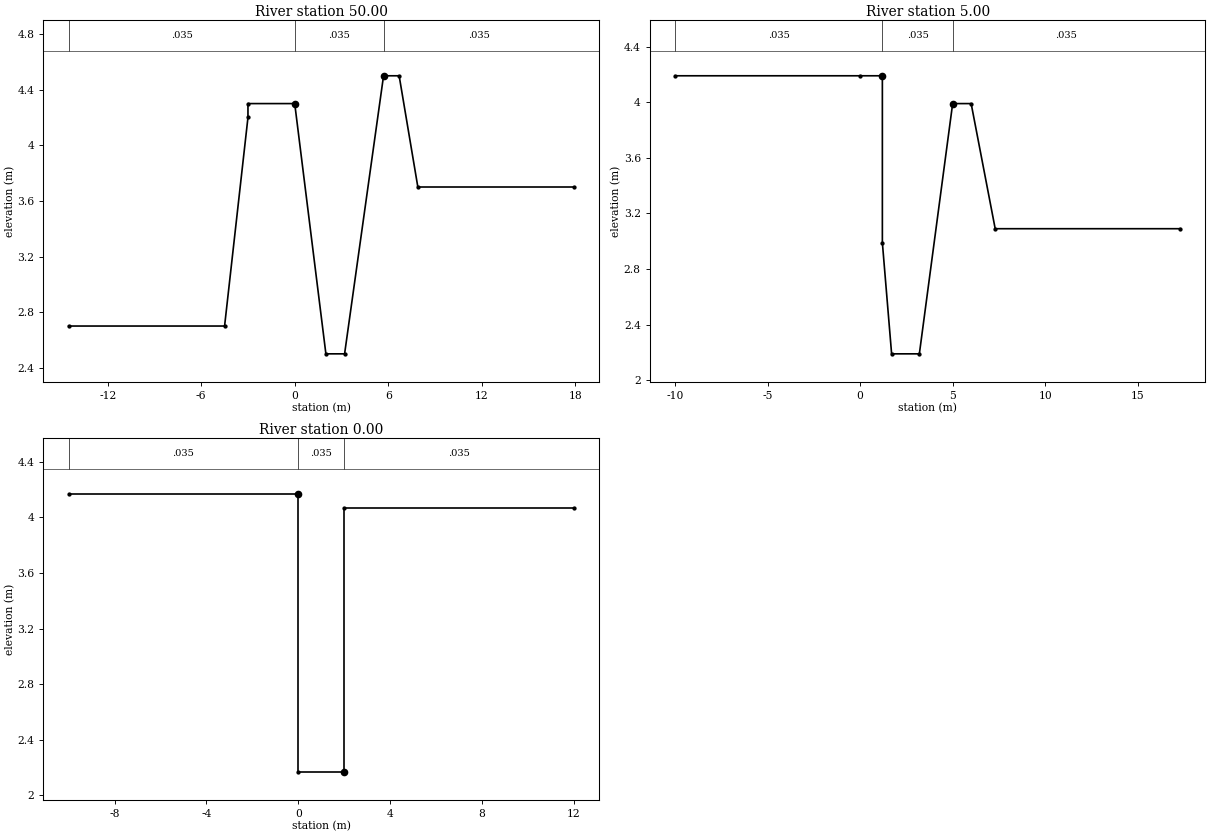
Type RM Length L Ch R = 1 ,50.00   ,45,45,45
BEGIN DESCRIPTION:
1
END DESCRIPTION:
#Sta/Elev= 11
   -14.5     2.7    -4.5     2.7      -3     4.2      -3     4.3       0     4.3
       2     2.5     3.2     2.5     5.7     4.5     6.7     4.5     7.9     3.7
    17.9     3.7
#Mann= 3 , 0 , 0
   -14.5    .035       0       0    .035       0     5.7    .035       0
#XS Ineff= 2 , 0
               0      20     5.7              20
Permanent Ineff=
       F       F
#Block Obstruct= 2 , 0
                             5.7
Bank Sta=0,5.7
XS Rating Curve= 0
Exp/Cntr=.3,.1

Type RM Length L Ch R = 1 ,5.00    ,5,5,5
BEGIN DESCRIPTION:
0.005
END DESCRIPTION:
#Sta/Elev= 10
     -10    4.19       0    4.19     1.2    4.19     1.2    2.99     1.7    2.19
     3.2    2.19       5    3.99       6    3.99     7.3    3.09    17.3    3.09
#Mann= 3 , 0 , 0
     -10    .035       0     1.2    .035       0       5    .035       0
#XS Ineff= 2 , 0
             1.2      20       5              20
Permanent Ineff=
       F       F
#Block Obstruct= 2 , 0
             1.2               5
Bank Sta=1.2,5
XS Rating Curve= 0
Exp/Cntr=.3,.1

Type RM Length L Ch R = 1 ,0.00    ,0,0,0
BEGIN DESCRIPTION:
0
END DESCRIPTION:
#Sta/Elev= 6
     -10    4.17       0    4.17       0    2.17       2    2.17       2    4.07
      12    4.07
#Mann= 3 , 0 , 0
     -10    .035       0       0    .035       0       2    .035       0
#XS Ineff= 2 , 0
               0      20       2              20
Permanent Ineff=
       F       F
#Block Obstruct= 2 , 0
                               2
Bank Sta=0,2
XS Rating Curve= 0
Exp/Cntr=.3,.1

Chan Stop Cuts=-1

--- shc.g01 (geometry) ---

Geom Title=Imported Geom 01
Version=Version 3.0.1  Mar 2001

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
River Reach=RIVER-1         ,Reach-1

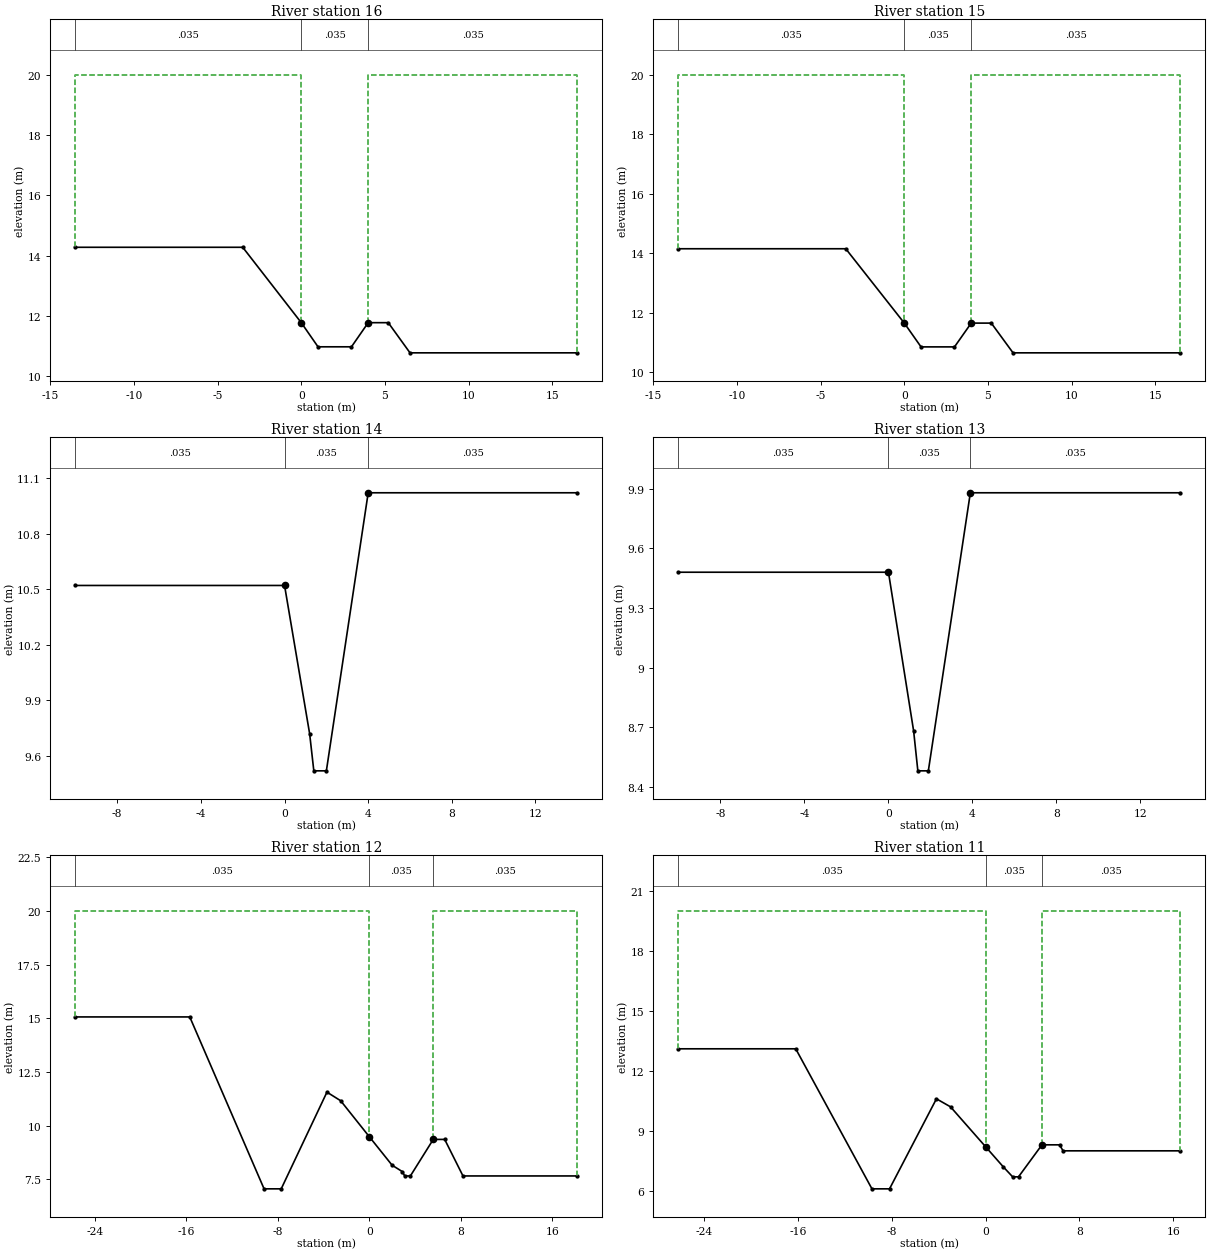
Type RM Length L Ch R = 1 ,16      ,10,10,10
BEGIN DESCRIPTION:
11.01
END DESCRIPTION:
#Sta/Elev= 9
   -13.5   14.28    -3.5   14.28       0   11.78       1   10.98       3   10.98
       4   11.78     5.2   11.78     6.5   10.78    16.5   10.78
#Mann= 3 , 0 , 0
   -13.5    .035       0       0    .035       0       4    .035       0
#XS Ineff= 2 , 0
               0      20       4              20
Permanent Ineff=
       F       F
#Block Obstruct= 2 , 0
                               4
Bank Sta=0,4
XS Rating Curve= 0
Exp/Cntr=.3,.1

Type RM Length L Ch R = 1 ,15      ,50,50,50
BEGIN DESCRIPTION:
11
END DESCRIPTION:
#Sta/Elev= 9
   -13.5   14.15    -3.5   14.15       0   11.65       1   10.85       3   10.85
       4   11.65     5.2   11.65     6.5   10.65    16.5   10.65
#Mann= 3 , 0 , 0
   -13.5    .035       0       0    .035       0       4    .035       0
#XS Ineff= 2 , 0
               0      20       4              20
Permanent Ineff=
       F       F
#Block Obstruct= 2 , 0
                               4
Bank Sta=0,4
XS Rating Curve= 0
Exp/Cntr=.3,.1

Type RM Length L Ch R = 1 ,14      ,50,50,50
BEGIN DESCRIPTION:
10
END DESCRIPTION:
#Sta/Elev= 7
     -10   10.52       0   10.52     1.2    9.72     1.4    9.52       2    9.52
       4   11.02      14   11.02
#Mann= 3 , 0 , 0
     -10    .035       0       0    .035       0       4    .035       0
#XS Ineff= 2 , 0
               0      20       4              20
Permanent Ineff=
       F       F
#Block Obstruct= 2 , 0
                               4
Bank Sta=0,4
XS Rating Curve= 0
Exp/Cntr=.3,.1

Type RM Length L Ch R = 1 ,13      ,50,50,50
BEGIN DESCRIPTION:
9
END DESCRIPTION:
#Sta/Elev= 7
     -10    9.48       0    9.48     1.2    8.68     1.4    8.48     1.9    8.48
     3.9    9.88    13.9    9.88
#Mann= 3 , 0 , 0
     -10    .035       0       0    .035       0     3.9    .035       0
#XS Ineff= 2 , 0
               0      20     3.9              20
Permanent Ineff=
       F       F
#Block Obstruct= 2 , 0
                             3.9
Bank Sta=0,3.9
XS Rating Curve= 0
Exp/Cntr=.3,.1

Type RM Length L Ch R = 1 ,12      ,50,50,50
BEGIN DESCRIPTION:
8
END DESCRIPTION:
#Sta/Elev= 15
   -25.7   15.06   -15.7   15.06    -9.2    7.06    -7.7    7.06    -3.7   11.56
    -2.5   11.16       0    9.49       2    8.16     2.9    7.86     3.1    7.66
     3.6    7.66     5.6    9.36     6.6    9.36     8.2    7.66    18.2    7.66
#Mann= 3 , 0 , 0
   -25.7    .035       0       0    .035       0     5.6    .035       0
#XS Ineff= 2 , 0
               0      20     5.6              20
Permanent Ineff=
       F       F
#Block Obstruct= 2 , 0
                             5.6
Bank Sta=0,5.6
XS Rating Curve= 0
Exp/Cntr=.3,.1

Type RM Length L Ch R = 1 ,11      ,50,50,50
BEGIN DESCRIPTION:
7
END DESCRIPTION:
#Sta/Elev= 14
   -26.2    13.1   -16.2    13.1    -9.7     6.1    -8.2     6.1    -4.2    10.6
      -3    10.2       0     8.2     1.5     7.2     2.3     6.7     2.8     6.7
     4.8     8.3     6.3     8.3     6.6       8    16.6       8
#Mann= 3 , 0 , 0
   -26.2    .035       0       0    .035       0     4.8    .035       0
#XS Ineff= 2 , 0
               0      20     4.8              20
Permanent Ineff=
       F       F
#Block Obstruct= 2 , 0
                             4.8
Bank Sta=0,4.8
XS Rating Curve= 0
Exp/Cntr=.3,.1

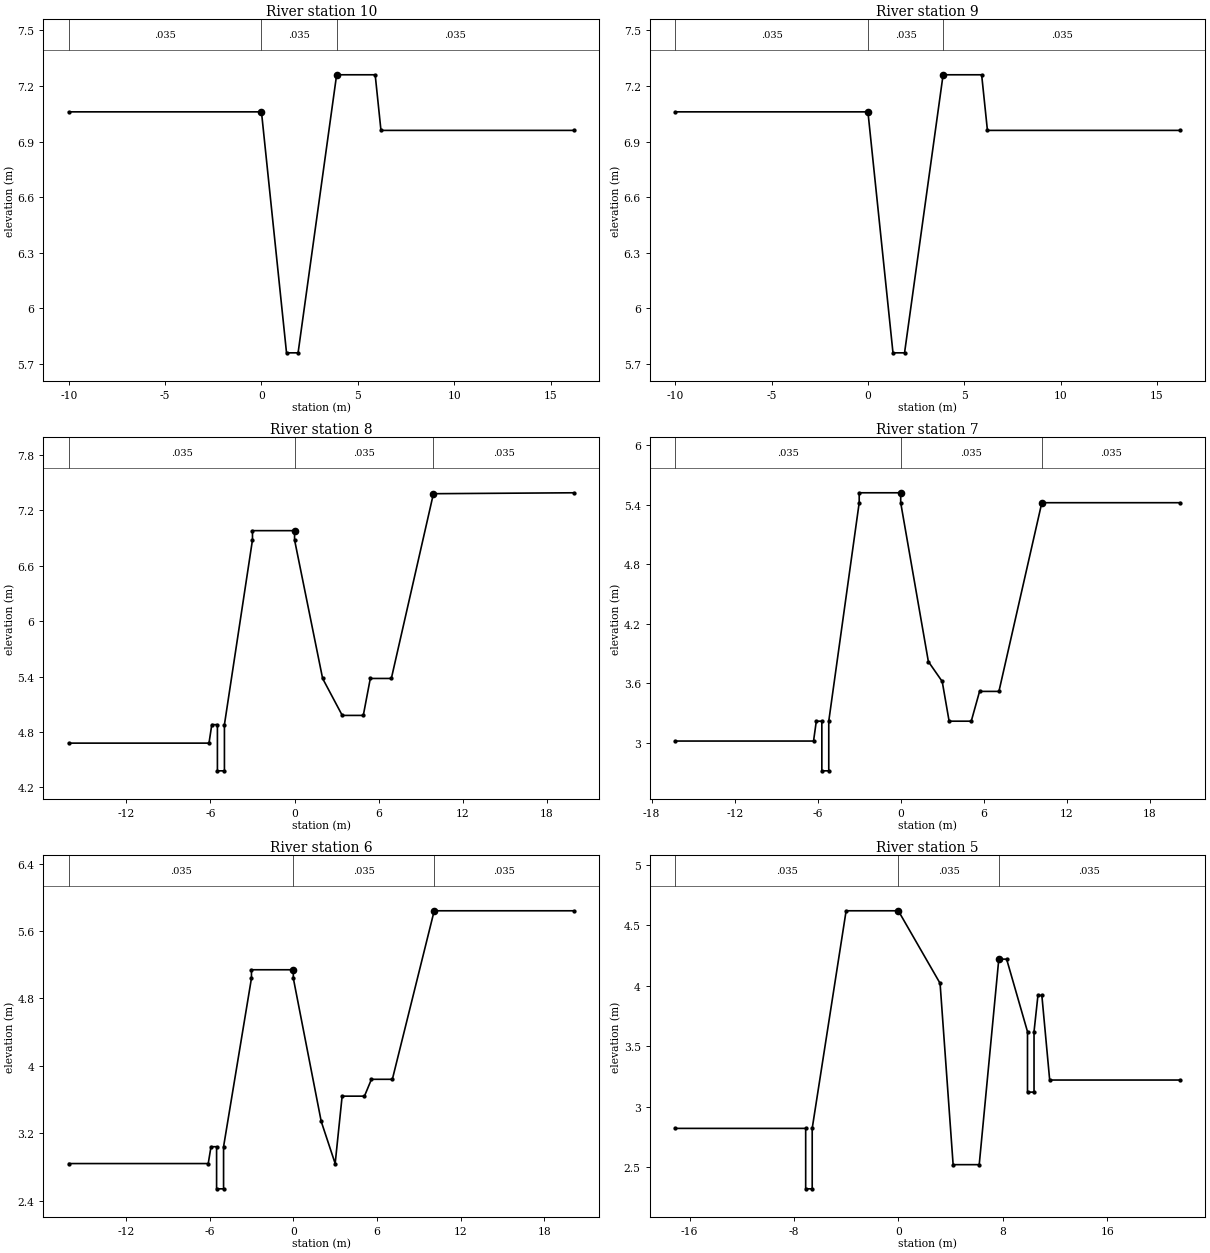
Type RM Length L Ch R = 1 ,10      ,50,50,50
BEGIN DESCRIPTION:
6
END DESCRIPTION:
#Sta/Elev= 8
     -10    7.06       0    7.06     1.3    5.76     1.9    5.76     3.9    7.26
     5.9    7.26     6.2    6.96    16.2    6.96
#Mann= 3 , 0 , 0
     -10    .035       0       0    .035       0     3.9    .035       0
#XS Ineff= 2 , 0
               0      20     3.9              20
Permanent Ineff=
       F       F
#Block Obstruct= 2 , 0
                             3.9
Bank Sta=0,3.9
XS Rating Curve= 0
Exp/Cntr=.3,.1

Type RM Length L Ch R = 1 ,9       ,50,50,50
BEGIN DESCRIPTION:
6
END DESCRIPTION:
#Sta/Elev= 8
     -10    7.06       0    7.06     1.3    5.76     1.9    5.76     3.9    7.26
     5.9    7.26     6.2    6.96    16.2    6.96
#Mann= 3 , 0 , 0
     -10    .035       0       0    .035       0     3.9    .035       0
#XS Ineff= 2 , 0
               0      20     3.9              20
Permanent Ineff=
       F       F
#Block Obstruct= 2 , 0
                             3.9
Bank Sta=0,3.9
XS Rating Curve= 0
Exp/Cntr=.3,.1

Type RM Length L Ch R = 1 ,8       ,50,50,50
BEGIN DESCRIPTION:
5
END DESCRIPTION:
#Sta/Elev= 18
   -16.1    4.68    -6.1    4.68    -5.9    4.88    -5.5    4.88    -5.5    4.38
      -5    4.38      -5    4.88      -3    6.88      -3    6.98       0    6.98
       0    6.88       2    5.38     3.4    4.98     4.9    4.98     5.4    5.38
     6.9    5.38     9.9    7.38    19.9    7.39
#Mann= 3 , 0 , 0
   -16.1    .035       0       0    .035       0     9.9    .035       0
#XS Ineff= 2 , 0
               0      20     9.9              20
Permanent Ineff=
       F       F
#Block Obstruct= 2 , 0
                             9.9
Bank Sta=0,9.9
XS Rating Curve= 0
Exp/Cntr=.3,.1

Type RM Length L Ch R = 1 ,7       ,50,50,50
BEGIN DESCRIPTION:
4
END DESCRIPTION:
#Sta/Elev= 19
   -16.3    3.02    -6.3    3.02    -6.1    3.22    -5.7    3.22    -5.7    2.72
    -5.2    2.72    -5.2    3.22      -3    5.42      -3    5.52       0    5.52
       0    5.42       2    3.82       3    3.62     3.5    3.22     5.1    3.22
     5.7    3.52     7.1    3.52    10.2    5.42    20.2    5.42
#Mann= 3 , 0 , 0
   -16.3    .035       0       0    .035       0    10.2    .035       0
#XS Ineff= 2 , 0
               0      20    10.2              20
Permanent Ineff=
       F       F
#Block Obstruct= 2 , 0
                            10.2
Bank Sta=0,10.2
XS Rating Curve= 0
Exp/Cntr=.3,.1

Type RM Length L Ch R = 1 ,6       ,32,32,32
BEGIN DESCRIPTION:
3
END DESCRIPTION:
#Sta/Elev= 19
   -16.1    2.84    -6.1    2.84    -5.9    3.04    -5.5    3.04    -5.5    2.54
      -5    2.54      -5    3.04      -3    5.04      -3    5.14       0    5.14
       0    5.04       2    3.34       3    2.84     3.5    3.64     5.1    3.64
     5.6    3.84     7.1    3.84    10.1    5.84    20.1    5.84
#Mann= 3 , 0 , 0
   -16.1    .035       0       0    .035       0    10.1    .035       0
#XS Ineff= 2 , 0
               0      20    10.1              20
Permanent Ineff=
       F       F
#Block Obstruct= 2 , 0
                            10.1
Bank Sta=0,10.1
XS Rating Curve= 0
Exp/Cntr=.3,.1

Type RM Length L Ch R = 1 ,5       ,18,18,18
BEGIN DESCRIPTION:
2.018
END DESCRIPTION:
#Sta/Elev= 20
   -17.1    2.82    -7.1    2.82    -7.1    2.32    -6.6    2.32    -6.6    2.82
      -4    4.62       0    4.62     3.2    4.02     4.2    2.52     6.2    2.52
     7.7    4.22     8.3    4.22     9.9    3.62     9.9    3.12    10.4    3.12
    10.4    3.62    10.7    3.92      11    3.92    11.6    3.22    21.6    3.22
#Mann= 3 , 0 , 0
   -17.1    .035       0       0    .035       0     7.7    .035       0
#XS Ineff= 2 , 0
               0      20     7.7              20
Permanent Ineff=
       F       F
#Block Obstruct= 2 , 0
                             7.7
Bank Sta=0,7.7
XS Rating Curve= 0
Exp/Cntr=.3,.1

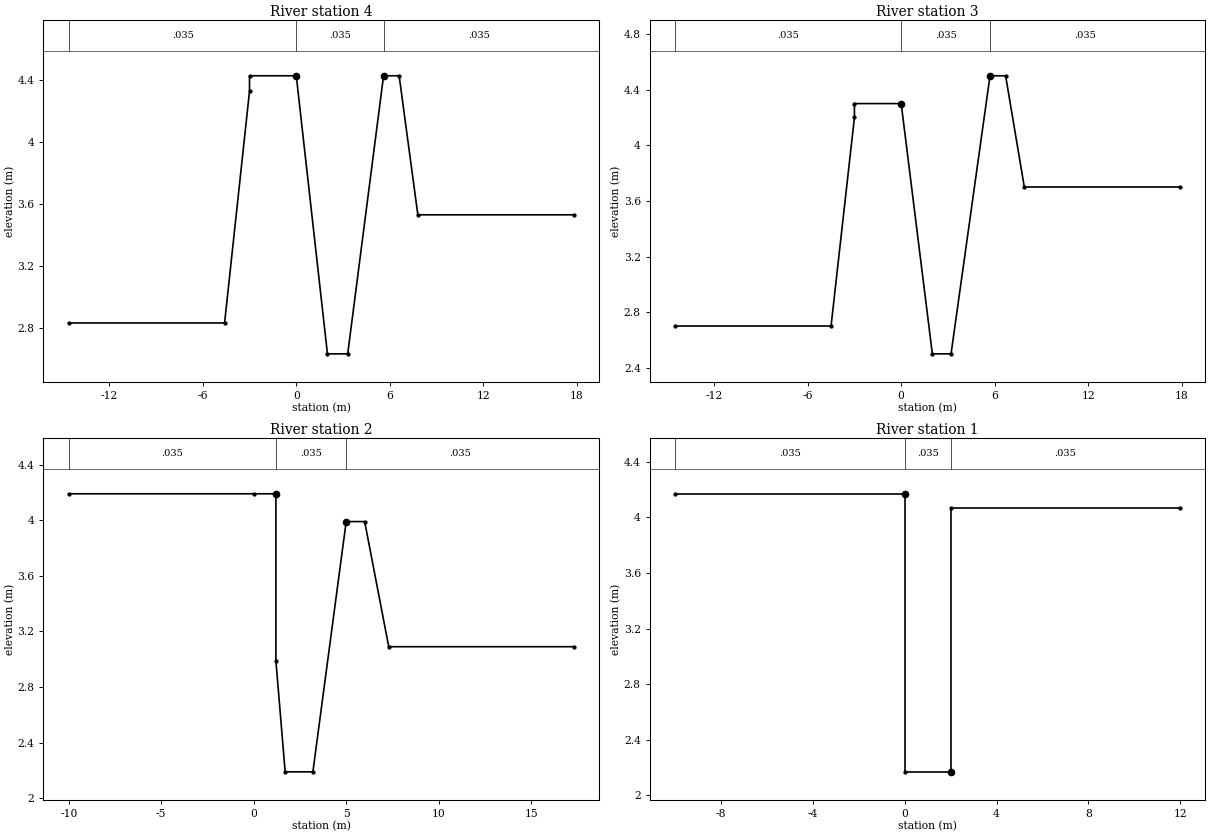
Type RM Length L Ch R = 1 ,4       ,50,50,50
BEGIN DESCRIPTION:
2
END DESCRIPTION:
#Sta/Elev= 11
   -14.6    2.83    -4.6    2.83      -3    4.33      -3    4.43       0    4.43
       2    2.63     3.3    2.63     5.6    4.43     6.6    4.43     7.8    3.53
    17.8    3.53
#Mann= 3 , 0 , 0
   -14.6    .035       0       0    .035       0     5.6    .035       0
#XS Ineff= 2 , 0
               0      20     5.6              20
Permanent Ineff=
       F       F
#Block Obstruct= 2 , 0
                             5.6
Bank Sta=0,5.6
XS Rating Curve= 0
Exp/Cntr=.3,.1

Type RM Length L Ch R = 1 ,3       ,45,45,45
BEGIN DESCRIPTION:
1
END DESCRIPTION:
#Sta/Elev= 11
   -14.5     2.7    -4.5     2.7      -3     4.2      -3     4.3       0     4.3
       2     2.5     3.2     2.5     5.7     4.5     6.7     4.5     7.9     3.7
    17.9     3.7
#Mann= 3 , 0 , 0
   -14.5    .035       0       0    .035       0     5.7    .035       0
#XS Ineff= 2 , 0
               0      20     5.7              20
Permanent Ineff=
       F       F
#Block Obstruct= 2 , 0
                             5.7
Bank Sta=0,5.7
XS Rating Curve= 0
Exp/Cntr=.3,.1

Type RM Length L Ch R = 1 ,2       ,5,5,5
BEGIN DESCRIPTION:
0.005
END DESCRIPTION:
#Sta/Elev= 10
     -10    4.19       0    4.19     1.2    4.19     1.2    2.99     1.7    2.19
     3.2    2.19       5    3.99       6    3.99     7.3    3.09    17.3    3.09
#Mann= 3 , 0 , 0
     -10    .035       0     1.2    .035       0       5    .035       0
#XS Ineff= 2 , 0
             1.2      20       5              20
Permanent Ineff=
       F       F
#Block Obstruct= 2 , 0
             1.2               5
Bank Sta=1.2,5
XS Rating Curve= 0
Exp/Cntr=.3,.1

Type RM Length L Ch R = 1 ,1       ,0,0,0
BEGIN DESCRIPTION:
0
END DESCRIPTION:
#Sta/Elev= 6
     -10    4.17       0    4.17       0    2.17       2    2.17       2    4.07
      12    4.07
#Mann= 3 , 0 , 0
     -10    .035       0       0    .035       0       2    .035       0
#XS Ineff= 2 , 0
               0      20       2              20
Permanent Ineff=
       F       F
#Block Obstruct= 2 , 0
                               2
Bank Sta=0,2
XS Rating Curve= 0
Exp/Cntr=.3,.1