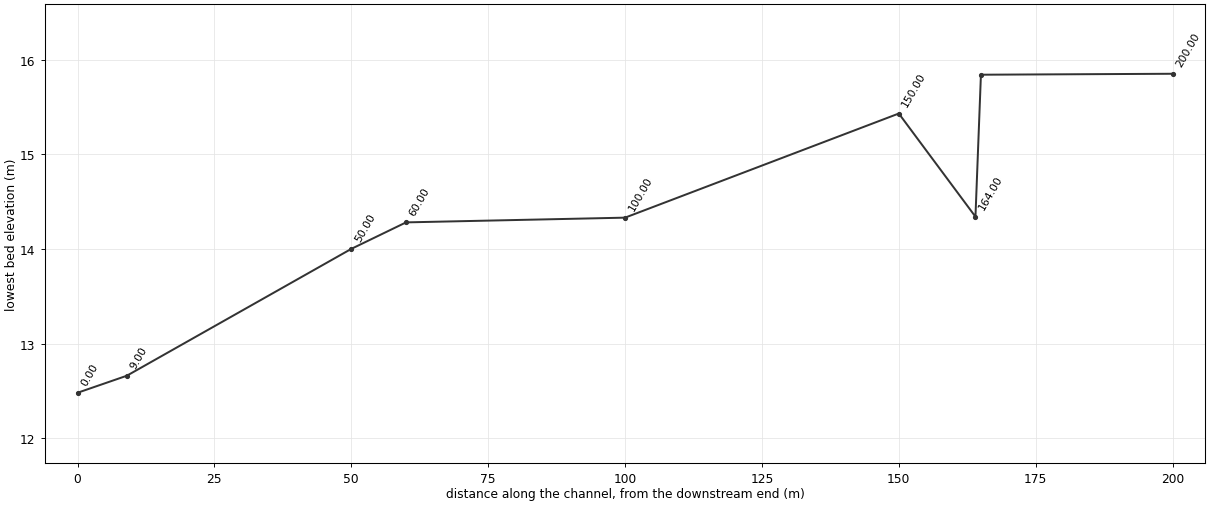
HEC-RAS study JJC.prj: JAEJUNG

--- JJC.g01 (geometry) --- (continued)

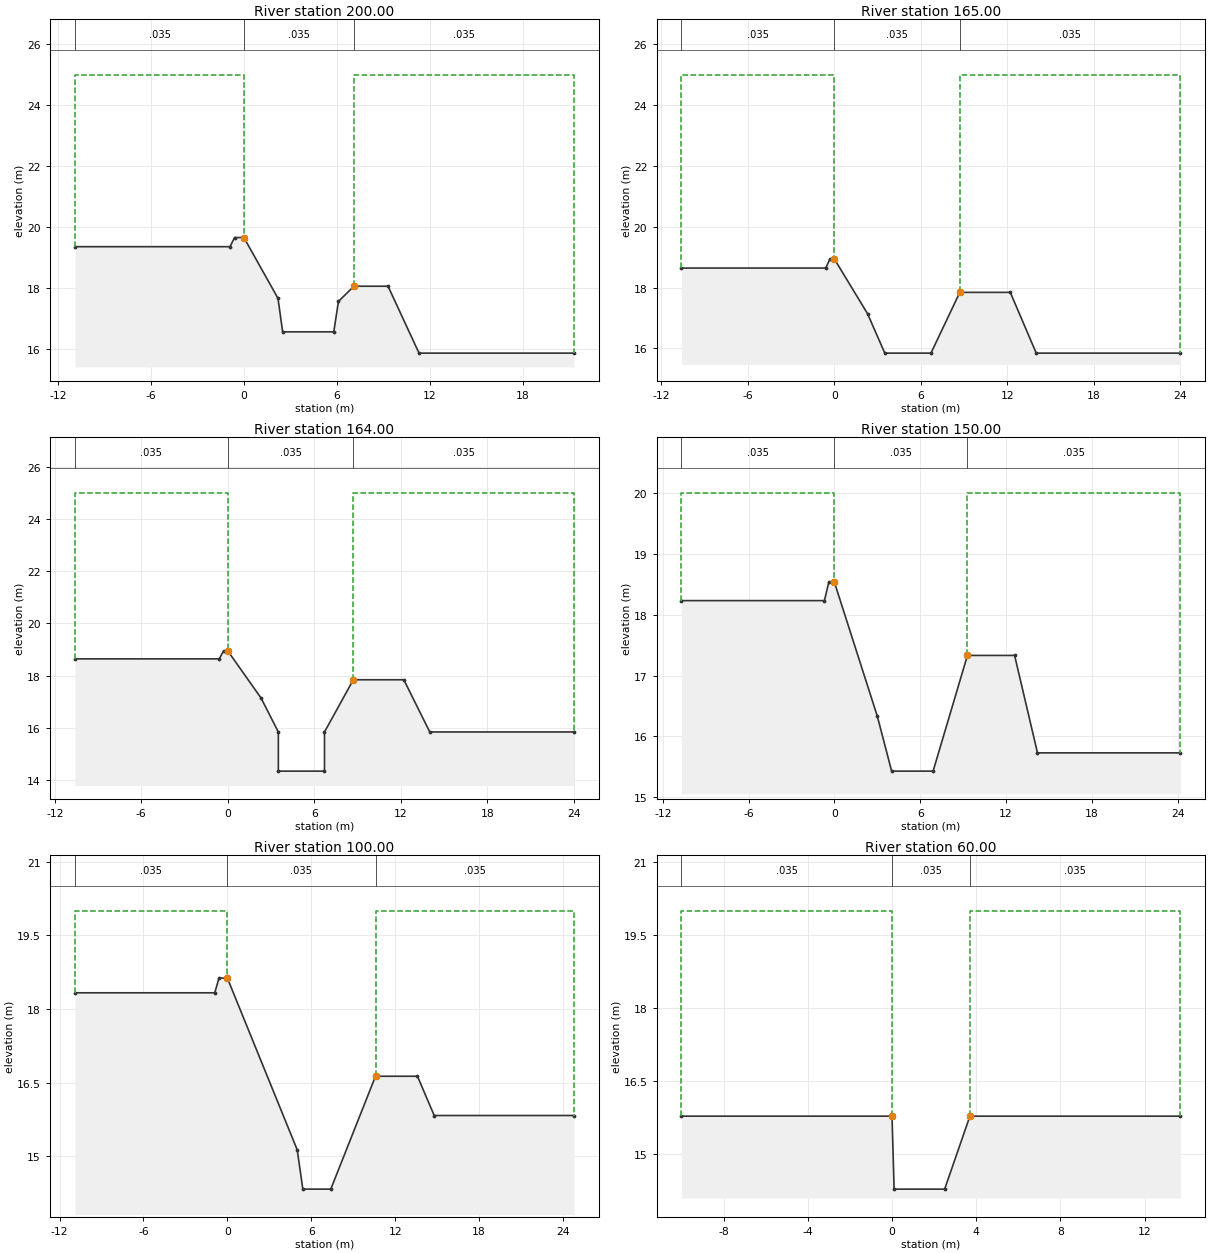
Type RM Length L Ch R = 1 ,200.00  ,35,35,35
BEGIN DESCRIPTION:
4
END DESCRIPTION:
#Sta/Elev= 12
   -10.9   19.35     -.9   19.35     -.6   19.65       0   19.65     2.2   17.65
     2.5   16.55     5.8   16.55     6.1   17.55     7.1   18.05     9.3   18.05
    11.3   15.85    21.3   15.85
#Mann= 3 , 0 , 0
   -10.9    .035       0       0    .035       0     7.1    .035       0
#XS Ineff= 2 , 0
               0      25     7.1              25
Permanent Ineff=
       F       F
#Block Obstruct= 2 , 0
                             7.1
Bank Sta=0,7.1
XS Rating Curve= 0
Exp/Cntr=.3,.1

Type RM Length L Ch R = 1 ,165.00  ,1,1,1
BEGIN DESCRIPTION:
3.015
END DESCRIPTION:
#Sta/Elev= 11
   -10.6   18.64     -.6   18.64     -.3   18.94       0   18.94     2.3   17.14
     3.5   15.84     6.7   15.84     8.7   17.84    12.2   17.84      14   15.84
      24   15.84
#Mann= 3 , 0 , 0
   -10.6    .035       0       0    .035       0     8.7    .035       0
#XS Ineff= 2 , 0
               0      25     8.7              25
Permanent Ineff=
       F       F
#Block Obstruct= 2 , 0
                             8.7
Bank Sta=0,8.7
XS Rating Curve= 0
Exp/Cntr=.3,.1

Type RM Length L Ch R = 1 ,164.00  ,14,14,14
BEGIN DESCRIPTION:
3.014
END DESCRIPTION:
#Sta/Elev= 13
   -10.6   18.64     -.6   18.64     -.3   18.94       0   18.94     2.3   17.14
     3.5   15.84     3.5   14.34     6.7   14.34     6.7   15.84     8.7   17.84
    12.2   17.84      14   15.84      24   15.84
#Mann= 3 , 0 , 0
   -10.6    .035       0       0    .035       0     8.7    .035       0
#XS Ineff= 2 , 0
               0      25     8.7              25
Permanent Ineff=
       F       F
#Block Obstruct= 2 , 0
                             8.7
Bank Sta=0,8.7
XS Rating Curve= 0
Exp/Cntr=.3,.1

Type RM Length L Ch R = 1 ,150.00  ,50,50,50
BEGIN DESCRIPTION:
3
END DESCRIPTION:
#Sta/Elev= 11
   -10.7   18.23     -.7   18.23     -.4   18.53       0   18.53       3   16.33
       4   15.43     6.9   15.43     9.3   17.33    12.6   17.33    14.2   15.73
    24.2   15.73
#Mann= 3 , 0 , 0
   -10.7    .035       0       0    .035       0     9.3    .035       0
#XS Ineff= 2 , 0
               0      20     9.3              20
Permanent Ineff=
       F       F
#Block Obstruct= 2 , 0
                             9.3
Bank Sta=0,9.3
XS Rating Curve= 0
Exp/Cntr=.3,.1

Type RM Length L Ch R = 1 ,100.00  ,40,40,40
BEGIN DESCRIPTION:
2
END DESCRIPTION:
#Sta/Elev= 11
   -10.9   18.33     -.9   18.33     -.6   18.63       0   18.63       5   15.13
     5.4   14.33     7.4   14.33    10.6   16.63    13.6   16.63    14.8   15.83
    24.8   15.83
#Mann= 3 , 0 , 0
   -10.9    .035       0       0    .035       0    10.6    .035       0
#XS Ineff= 2 , 0
               0      20    10.6              20
Permanent Ineff=
       F       F
#Block Obstruct= 2 , 0
                            10.6
Bank Sta=0,10.6
XS Rating Curve= 0
Exp/Cntr=.3,.1

Type RM Length L Ch R = 1 ,60.00   ,10,10,10
BEGIN DESCRIPTION:
1.01
END DESCRIPTION:
#Sta/Elev= 6
     -10   15.78       0   15.78      .1   14.28     2.5   14.28     3.7   15.78
    13.7   15.78
#Mann= 3 , 0 , 0
     -10    .035       0       0    .035       0     3.7    .035       0
#XS Ineff= 2 , 0
               0      20     3.7              20
Permanent Ineff=
       F       F
#Block Obstruct= 2 , 0
                             3.7
Bank Sta=0,3.7
XS Rating Curve= 0
Exp/Cntr=.3,.1

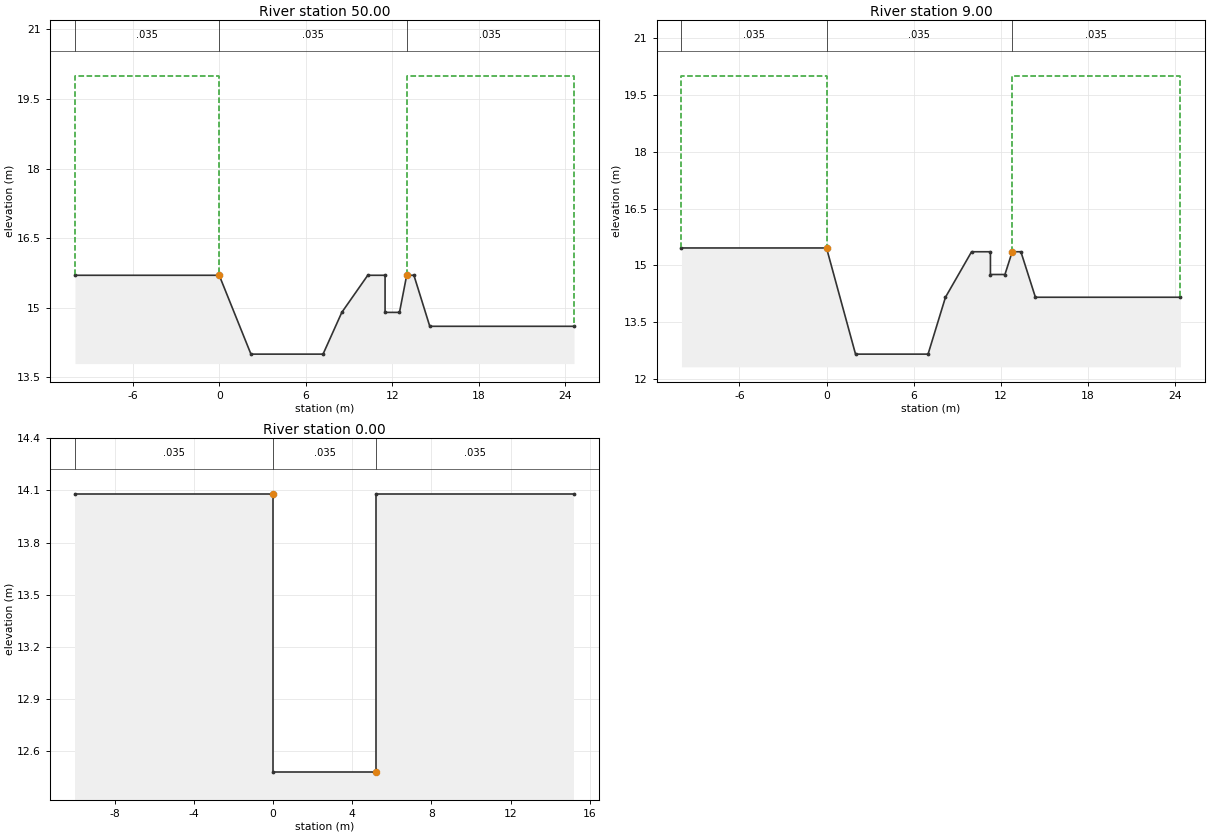
Type RM Length L Ch R = 1 ,50.00   ,41,41,41
BEGIN DESCRIPTION:
1
END DESCRIPTION:
#Sta/Elev= 13
     -10    15.7       0    15.7     2.2      14     7.2      14     8.5    14.9
    10.3    15.7    11.5    15.7    11.5    14.9    12.5    14.9      13    15.7
    13.5    15.7    14.6    14.6    24.6    14.6
#Mann= 3 , 0 , 0
     -10    .035       0       0    .035       0      13    .035       0
#XS Ineff= 2 , 0
               0      20      13              20
Permanent Ineff=
       F       F
#Block Obstruct= 2 , 0
                              13
Bank Sta=0,13
XS Rating Curve= 0
Exp/Cntr=.3,.1

Type RM Length L Ch R = 1 ,9.00    ,9,9,9
BEGIN DESCRIPTION:
0.009
END DESCRIPTION:
#Sta/Elev= 13
     -10   15.46       0   15.46       2   12.66       7   12.66     8.2   14.16
      10   15.36    11.3   15.36    11.3   14.76    12.3   14.76    12.8   15.36
    13.4   15.36    14.4   14.16    24.4   14.16
#Mann= 3 , 0 , 0
     -10    .035       0       0    .035       0    12.8    .035       0
#XS Ineff= 2 , 0
               0      20    12.8              20
Permanent Ineff=
       F       F
#Block Obstruct= 2 , 0
                            12.8
Bank Sta=0,12.8
XS Rating Curve= 0
Exp/Cntr=.3,.1

Type RM Length L Ch R = 1 ,0.00    ,0,0,0
BEGIN DESCRIPTION:
0
END DESCRIPTION:
#Sta/Elev= 6
     -10   14.08       0   14.08       0   12.48     5.2   12.48     5.2   14.08
    15.2   14.08
#Mann= 3 , 0 , 0
     -10    .035       0       0    .035       0     5.2    .035       0
#XS Ineff= 2 , 0
               0      20     5.2              20
Permanent Ineff=
       F       F
#Block Obstruct= 2 , 0
                             5.2
Bank Sta=0,5.2
XS Rating Curve= 0
Exp/Cntr=.3,.1

Chan Stop Cuts=-1