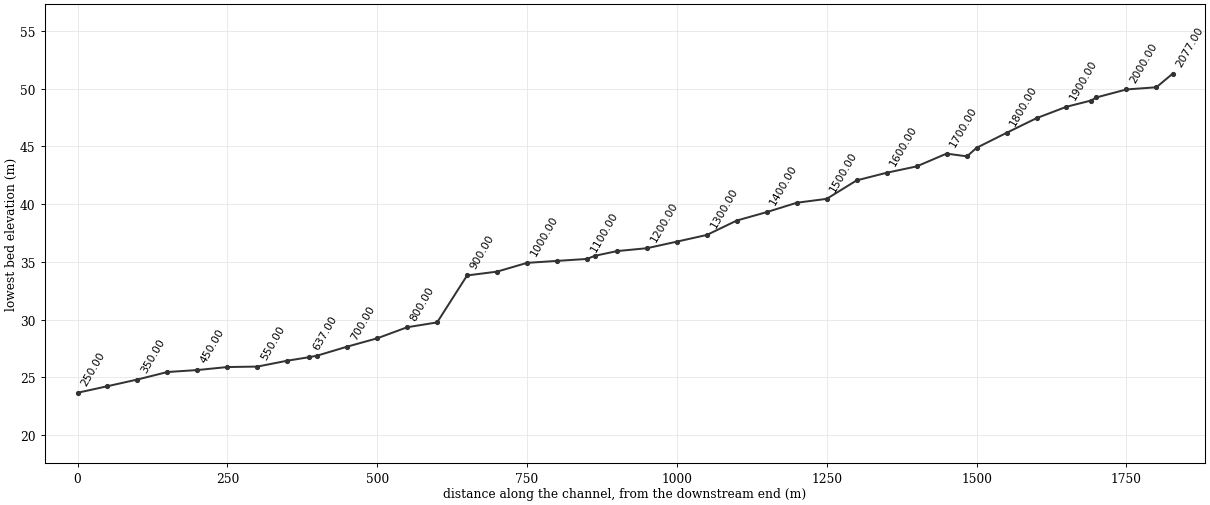
--- YAC.prj (project) ---

Proj Title=YEUMYA
Current Plan=p01
Default Exp/Contr=.3,.1
SI Units
Geom File=g01
Flow File=f01
Plan File=p01
Y Axis Title=Elevation
X Axis Title(PF)=Main Channel Distance
X Axis Title(XS)=Station
BEGIN DESCRIPTION:
           BACK WATER COMPUTATION
      APPLICATION OF HEC-2 BY Samju Construction Engineering
      eumya-ch: 10,20,30,50,80 yr
END DESCRIPTION:
DSS Export Rating Curves= 0
DSS Export Rating Curve Sorted= 0
DSS Export Volume Flow Curves= 0
DXF OffsetX= 0
DXF OffsetY= 0
DXF ScaleX= 1
DXF ScaleY= 10

--- YAC.p01 (plan) ---

Plan Title=Imported Plan 01
Version=Version 3.0.1  Mar 2001
Short Identifier=Imported Pla
Geom File=g01
Flow File=f01
Subcritical Flow
K Sum by GR= 0
Std Step Tol= 0.003
Critical Tol= 0.003
Num of Std Step Trials= 20
Max Error Tol= 0.1
Flow Tol Ratio= 0.001
Split Flow NTrial= 30
Split Flow Tol= 0.02
Split Flow Ratio= 0.02
Log Output Level= 0
Friction Slope Method= 1
Unsteady Friction Slope Method= 2
Parabolic Critical Depth
Global Vel Dist= 0 , 0 , 0
Global Log Level= 0
CheckData=True
Encroach Param=-1 ,0,0, 0
Computation Interval=1HOUR
Output Interval=1HOUR
Run HTab= 0
Run UNet= 0
Run PostProcess= 0
UNET Theta= 1
UNET ZTol= 0.02
UNET ZSATol= 0.1
UNET MxIter= 20
UNET MaxInSteps= 20
UNET DtIC= 0
UNET DtMin= 0
UNET MaxCRTS= 20
UNET WFStab= 2
UNET SFStab= 1
UNET WFX= 1
UNET SFX= 1
UNET Convert EG Bridges=-1
UNET Use Existing IB Tables=-1
Instantaneous Interval=1HOUR
Write IC File= 0
Write Velocity= 0
Write Detailed= 0

--- YAC.f01 (steady flow) ---

Flow Title=Imported Flow 01
Version=Version 3.0.1  Mar 2001
Number of Profiles= 5
Profile Names=10YR,20YR,30YR,50YR,80YR
River Rch & RM=RIVER-1,Reach-1         ,2077.00
  100.16  110.47  115.51   124.1   131.1
River Rch & RM=RIVER-1,Reach-1         ,1050.00
  113.06  124.75  131.59   140.2  148.12
Boundary for River Rch & Prof#=RIVER-1,Reach-1         , 1
Up Type= 0
Dn Type= 3
Dn Slope=.015
Boundary for River Rch & Prof#=RIVER-1,Reach-1         , 2
Up Type= 0
Dn Type= 3
Dn Slope=.015
Boundary for River Rch & Prof#=RIVER-1,Reach-1         , 3
Up Type= 0
Dn Type= 3
Dn Slope=.015
Boundary for River Rch & Prof#=RIVER-1,Reach-1         , 4
Up Type= 0
Dn Type= 3
Dn Slope=.015
Boundary for River Rch & Prof#=RIVER-1,Reach-1         , 5
Up Type= 0
Dn Type= 3
Dn Slope=.015
DSS Import GetInterval= 0
DSS Import GetPeak= 0
DSS Import FillOption= 0

--- YAC.g01 (geometry) ---

Geom Title=Imported Geom 01
Version=Version 3.0.1  Mar 2001

River Reach=RIVER-1         ,Reach-1
Reach XY= 2
              .5             .95              .5             .05

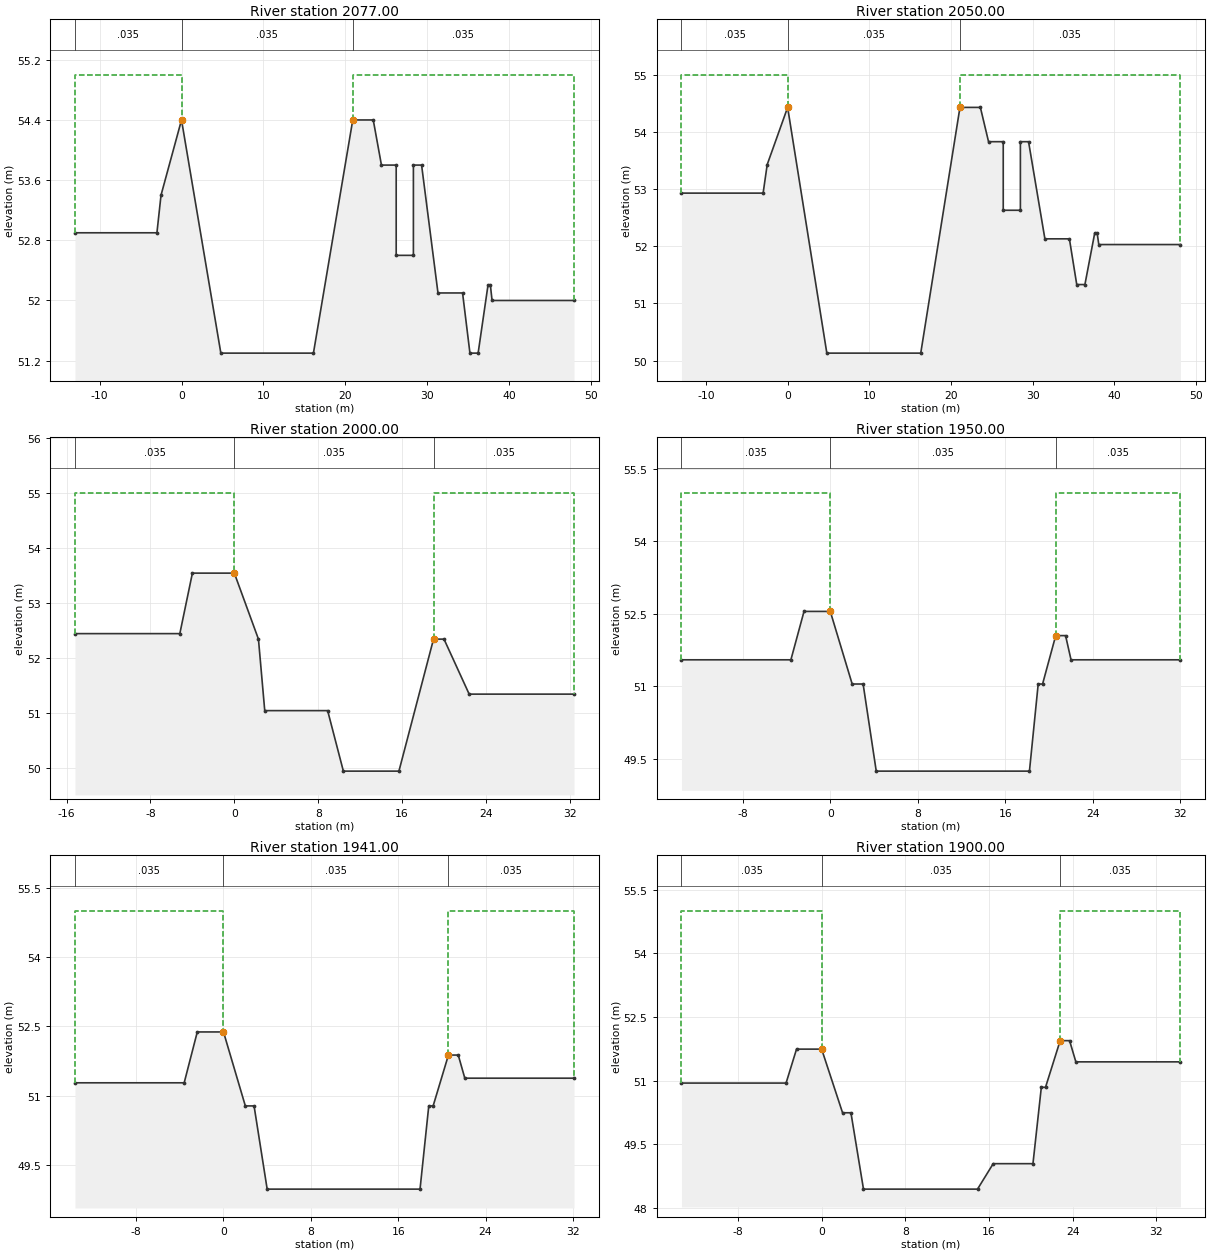
Type RM Length L Ch R = 1 ,2077.00 ,27,27,27
BEGIN DESCRIPTION:
41.027
END DESCRIPTION:
#Sta/Elev= 22
     -13    52.9      -3    52.9    -2.5    53.4       0    54.4     4.8    51.3
    16.1    51.3    20.9    54.4    23.4    54.4    24.4    53.8    26.2    53.8
    26.2    52.6    28.3    52.6    28.3    53.8    29.3    53.8    31.3    52.1
    34.3    52.1    35.2    51.3    36.2    51.3    37.4    52.2    37.7    52.2
    37.9      52    47.9      52
#Mann= 3 , 0 , 0
     -13    .035       0       0    .035       0    20.9    .035       0
#XS Ineff= 2 , 0
               0      55    20.9              55
Permanent Ineff=
       F       F
#Block Obstruct= 2 , 0
                            20.9
Bank Sta=0,20.9
XS Rating Curve= 0
Exp/Cntr=.3,.1

Type RM Length L Ch R = 1 ,2050.00 ,50,50,50
BEGIN DESCRIPTION:
41
END DESCRIPTION:
#Sta/Elev= 22
     -13   52.93      -3   52.93    -2.5   53.43       0   54.43     4.8   50.13
    16.3   50.13    21.1   54.43    23.6   54.43    24.6   53.83    26.4   53.83
    26.4   52.63    28.5   52.63    28.5   53.83    29.5   53.83    31.5   52.13
    34.5   52.13    35.4   51.33    36.4   51.33    37.6   52.23    37.9   52.23
    38.1   52.03    48.1   52.03
#Mann= 3 , 0 , 0
     -13    .035       0       0    .035       0    21.1    .035       0
#XS Ineff= 2 , 0
               0      55    21.1              55
Permanent Ineff=
       F       F
#Block Obstruct= 2 , 0
                            21.1
Bank Sta=0,21.1
XS Rating Curve= 0
Exp/Cntr=.3,.1

Type RM Length L Ch R = 1 ,2000.00 ,50,50,50
BEGIN DESCRIPTION:
40
END DESCRIPTION:
#Sta/Elev= 13
   -15.2   52.44    -5.2   52.44      -4   53.54       0   53.54     2.3   52.34
     2.9   51.04     8.9   51.04    10.4   49.94    15.7   49.94      19   52.34
      20   52.34    22.4   51.34    32.4   51.34
#Mann= 3 , 0 , 0
   -15.2    .035       0       0    .035       0      19    .035       0
#XS Ineff= 2 , 0
               0      55      19              55
Permanent Ineff=
       F       F
#Block Obstruct= 2 , 0
                              19
Bank Sta=0,19
XS Rating Curve= 0
Exp/Cntr=.3,.1

Type RM Length L Ch R = 1 ,1950.00 ,9,9,9
BEGIN DESCRIPTION:
39
END DESCRIPTION:
#Sta/Elev= 14
   -13.6   51.55    -3.6   51.55    -2.4   52.55       0   52.55       2   51.05
       3   51.05     4.2   49.25    18.2   49.25      19   51.05    19.4   51.05
    20.6   52.05    21.5   52.05      22   51.55      32   51.55
#Mann= 3 , 0 , 0
   -13.6    .035       0       0    .035       0    20.6    .035       0
#XS Ineff= 2 , 0
               0      55    20.6              55
Permanent Ineff=
       F       F
#Block Obstruct= 2 , 0
                            20.6
Bank Sta=0,20.6
XS Rating Curve= 0
Exp/Cntr=.3,.1

Type RM Length L Ch R = 1 ,1941.00 ,41,41,41
BEGIN DESCRIPTION:
38.041
END DESCRIPTION:
#Sta/Elev= 14
   -13.6   51.28    -3.6   51.28    -2.4   52.38       0   52.38       2   50.78
     2.8   50.78       4   48.98      18   48.98    18.8   50.78    19.2   50.78
    20.6   51.88    21.5   51.88    22.1   51.38    32.1   51.38
#Mann= 3 , 0 , 0
   -13.6    .035       0       0    .035       0    20.6    .035       0
#XS Ineff= 2 , 0
               0      55    20.6              55
Permanent Ineff=
       F       F
#Block Obstruct= 2 , 0
                            20.6
Bank Sta=0,20.6
XS Rating Curve= 0
Exp/Cntr=.3,.1

Type RM Length L Ch R = 1 ,1900.00 ,50,50,50
BEGIN DESCRIPTION:
38
END DESCRIPTION:
#Sta/Elev= 16
   -13.4   50.94    -3.4   50.94    -2.4   51.74       0   51.74       2   50.24
     2.8   50.24       4   48.44    14.9   48.44    16.4   49.04    20.2   49.04
      21   50.84    21.4   50.84    22.8   51.94    23.7   51.94    24.3   51.44
    34.3   51.44
#Mann= 3 , 0 , 0
   -13.4    .035       0       0    .035       0    22.8    .035       0
#XS Ineff= 2 , 0
               0      55    22.8              55
Permanent Ineff=
       F       F
#Block Obstruct= 2 , 0
                            22.8
Bank Sta=0,22.8
XS Rating Curve= 0
Exp/Cntr=.3,.1

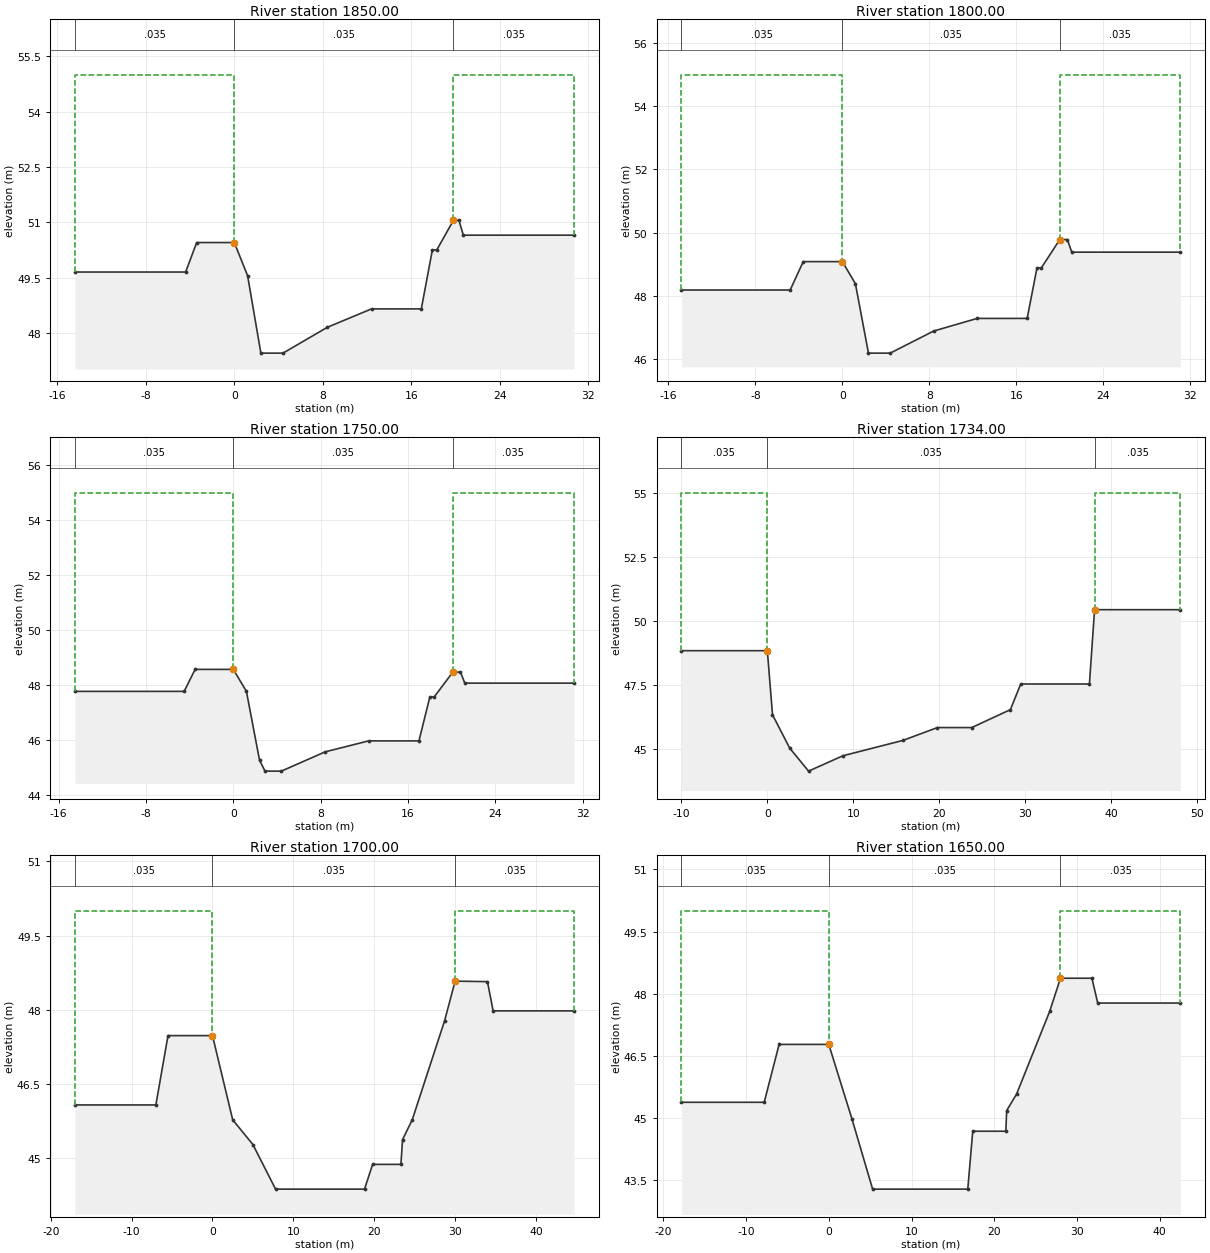
Type RM Length L Ch R = 1 ,1850.00 ,50,50,50
BEGIN DESCRIPTION:
37
END DESCRIPTION:
#Sta/Elev= 16
   -14.4   49.65    -4.4   49.65    -3.4   50.45       0   50.45     1.2   49.55
     2.4   47.45     4.4   47.45     8.4   48.15    12.4   48.65    16.9   48.65
    17.9   50.25    18.3   50.25    19.8   51.05    20.3   51.05    20.7   50.65
    30.7   50.65
#Mann= 3 , 0 , 0
   -14.4    .035       0       0    .035       0    19.8    .035       0
#XS Ineff= 2 , 0
               0      55    19.8              55
Permanent Ineff=
       F       F
#Block Obstruct= 2 , 0
                            19.8
Bank Sta=0,19.8
XS Rating Curve= 0
Exp/Cntr=.3,.1

Type RM Length L Ch R = 1 ,1800.00 ,50,50,50
BEGIN DESCRIPTION:
36
END DESCRIPTION:
#Sta/Elev= 16
   -14.8   48.18    -4.8   48.18    -3.6   49.08       0   49.08     1.2   48.38
     2.4   46.18     4.4   46.18     8.4   46.88    12.4   47.28      17   47.28
    17.9   48.88    18.3   48.88      20   49.78    20.7   49.78    21.1   49.38
    31.1   49.38
#Mann= 3 , 0 , 0
   -14.8    .035       0       0    .035       0      20    .035       0
#XS Ineff= 2 , 0
               0      55      20              55
Permanent Ineff=
       F       F
#Block Obstruct= 2 , 0
                              20
Bank Sta=0,20
XS Rating Curve= 0
Exp/Cntr=.3,.1

Type RM Length L Ch R = 1 ,1750.00 ,16,16,16
BEGIN DESCRIPTION:
35
END DESCRIPTION:
#Sta/Elev= 17
   -14.5   47.78    -4.5   47.78    -3.5   48.58       0   48.58     1.2   47.78
     2.4   45.28     2.9   44.88     4.4   44.88     8.4   45.58    12.4   45.98
      17   45.98      18   47.58    18.4   47.58    20.1   48.48    20.8   48.48
    21.2   48.08    31.2   48.08
#Mann= 3 , 0 , 0
   -14.5    .035       0       0    .035       0    20.1    .035       0
#XS Ineff= 2 , 0
               0      55    20.1              55
Permanent Ineff=
       F       F
#Block Obstruct= 2 , 0
                            20.1
Bank Sta=0,20.1
XS Rating Curve= 0
Exp/Cntr=.3,.1

Type RM Length L Ch R = 1 ,1734.00 ,34,34,34
BEGIN DESCRIPTION:
34.034
END DESCRIPTION:
#Sta/Elev= 14
     -10   48.84       0   48.84      .6   46.34     2.6   45.04     4.8   44.14
     8.8   44.74    15.8   45.34    19.8   45.84    23.8   45.84    28.3   46.54
    29.5   47.54    37.5   47.54    38.1   50.44    48.1   50.44
#Mann= 3 , 0 , 0
     -10    .035       0       0    .035       0    38.1    .035       0
#XS Ineff= 2 , 0
               0      55    38.1              55
Permanent Ineff=
       F       F
#Block Obstruct= 2 , 0
                            38.1
Bank Sta=0,38.1
XS Rating Curve= 0
Exp/Cntr=.3,.1

Type RM Length L Ch R = 1 ,1700.00 ,50,50,50
BEGIN DESCRIPTION:
34
END DESCRIPTION:
#Sta/Elev= 17
     -17   46.08      -7   46.08    -5.5   47.48       0   47.48     2.5   45.78
       5   45.28     7.8   44.38    18.8   44.38    19.8   44.88    23.3   44.88
    23.5   45.38    24.7   45.78    28.7   47.78      30   48.58      34   48.57
    34.7   47.98    44.7   47.98
#Mann= 3 , 0 , 0
     -17    .035       0       0    .035       0      30    .035       0
#XS Ineff= 2 , 0
               0      50      30              50
Permanent Ineff=
       F       F
#Block Obstruct= 2 , 0
                              30
Bank Sta=0,30
XS Rating Curve= 0
Exp/Cntr=.3,.1

Type RM Length L Ch R = 1 ,1650.00 ,50,50,50
BEGIN DESCRIPTION:
33
END DESCRIPTION:
#Sta/Elev= 16
   -17.8   45.37    -7.8   45.37      -6   46.77       0   46.77     2.8   44.97
     5.3   43.27    16.8   43.27    17.4   44.67    21.4   44.67    21.5   45.17
    22.7   45.57    26.7   47.57      28   48.37    31.8   48.37    32.5   47.77
    42.5   47.77
#Mann= 3 , 0 , 0
   -17.8    .035       0       0    .035       0      28    .035       0
#XS Ineff= 2 , 0
               0      50      28              50
Permanent Ineff=
       F       F
#Block Obstruct= 2 , 0
                              28
Bank Sta=0,28
XS Rating Curve= 0
Exp/Cntr=.3,.1

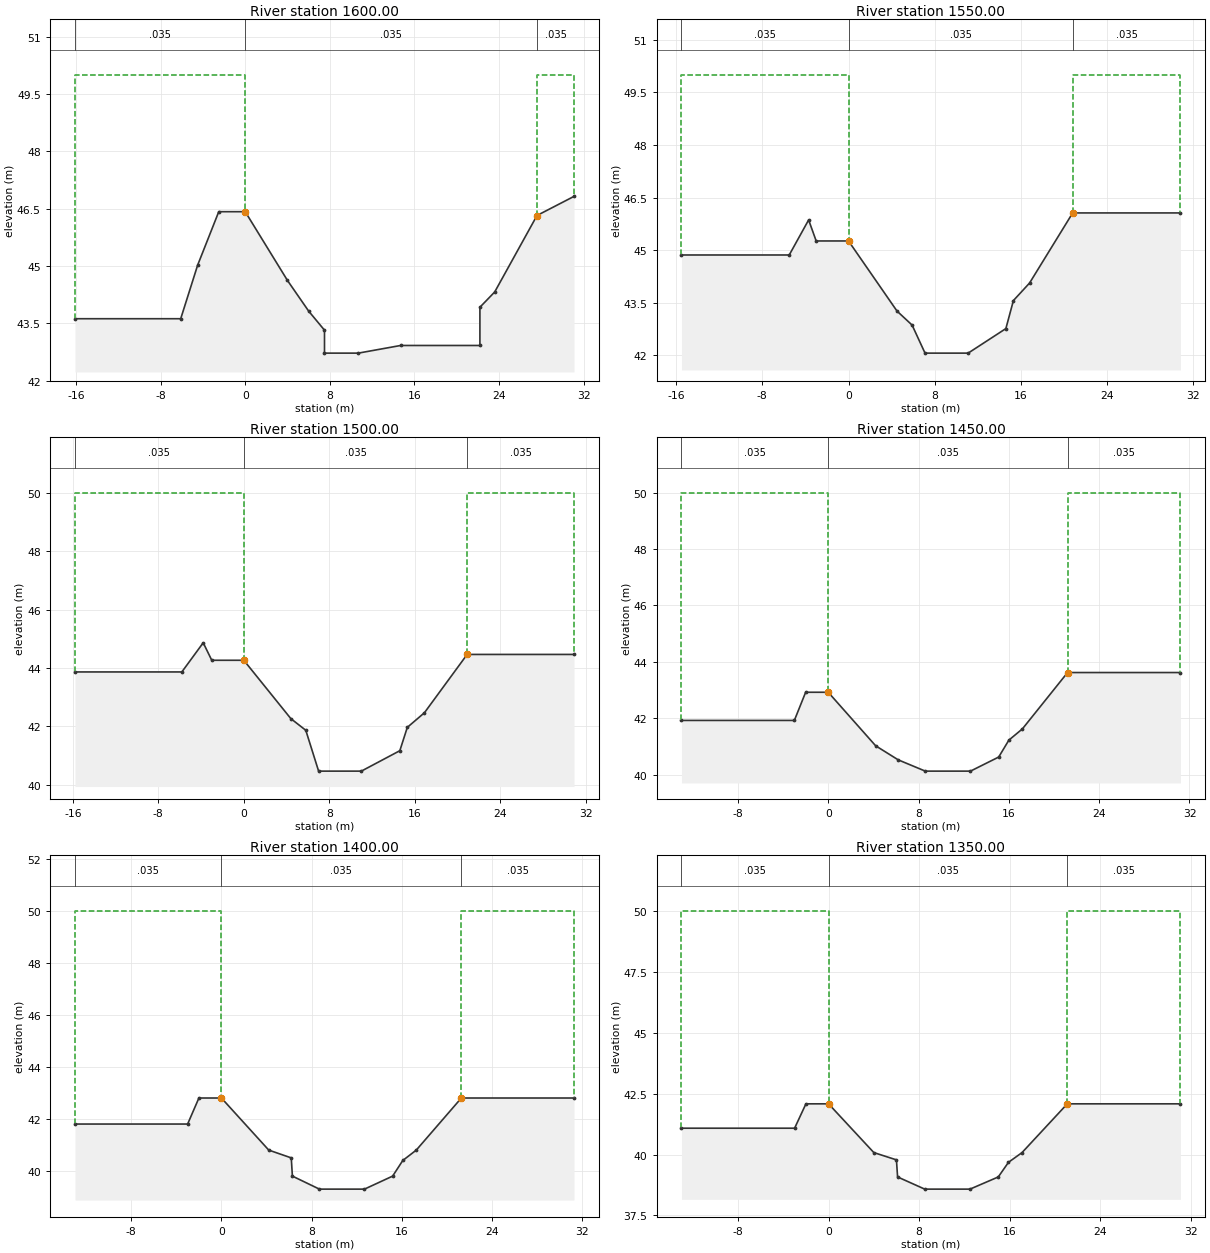
Type RM Length L Ch R = 1 ,1600.00 ,50,50,50
BEGIN DESCRIPTION:
32
END DESCRIPTION:
#Sta/Elev= 16
   -16.1   43.62    -6.1   43.62    -4.5   45.02    -2.5   46.42       0   46.42
       4   44.62       6   43.82     7.5   43.32     7.5   42.72    10.7   42.72
    14.7   42.92    22.2   42.92    22.2   43.92    23.6   44.32    27.6   46.32
    31.1   46.82
#Mann= 3 , 0 , 0
   -16.1    .035       0       0    .035       0    27.6    .035       0
#XS Ineff= 2 , 0
               0      50    27.6              50
Permanent Ineff=
       F       F
#Block Obstruct= 2 , 0
                            27.6
Bank Sta=0,27.6
XS Rating Curve= 0
Exp/Cntr=.3,.1

Type RM Length L Ch R = 1 ,1550.00 ,50,50,50
BEGIN DESCRIPTION:
31
END DESCRIPTION:
#Sta/Elev= 14
   -15.5   44.86    -5.5   44.86    -3.7   45.86      -3   45.26       0   45.26
     4.5   43.26     5.9   42.86     7.1   42.06    11.1   42.06    14.6   42.76
    15.3   43.56    16.8   44.06    20.8   46.06    30.8   46.06
#Mann= 3 , 0 , 0
   -15.5    .035       0       0    .035       0    20.8    .035       0
#XS Ineff= 2 , 0
               0      50    20.8              50
Permanent Ineff=
       F       F
#Block Obstruct= 2 , 0
                            20.8
Bank Sta=0,20.8
XS Rating Curve= 0
Exp/Cntr=.3,.1

Type RM Length L Ch R = 1 ,1500.00 ,50,50,50
BEGIN DESCRIPTION:
30
END DESCRIPTION:
#Sta/Elev= 14
   -15.8   43.86    -5.8   43.86    -3.8   44.86      -3   44.26       0   44.26
     4.4   42.26     5.8   41.86       7   40.46      11   40.46    14.6   41.16
    15.3   41.96    16.9   42.46    20.9   44.46    30.9   44.46
#Mann= 3 , 0 , 0
   -15.8    .035       0       0    .035       0    20.9    .035       0
#XS Ineff= 2 , 0
               0      50    20.9              50
Permanent Ineff=
       F       F
#Block Obstruct= 2 , 0
                            20.9
Bank Sta=0,20.9
XS Rating Curve= 0
Exp/Cntr=.3,.1

Type RM Length L Ch R = 1 ,1450.00 ,50,50,50
BEGIN DESCRIPTION:
29
END DESCRIPTION:
#Sta/Elev= 13
     -13   41.92      -3   41.92      -2   42.92       0   42.92     4.2   41.02
     6.2   40.52     8.6   40.12    12.6   40.12    15.1   40.62      16   41.22
    17.2   41.62    21.2   43.62    31.2   43.62
#Mann= 3 , 0 , 0
     -13    .035       0       0    .035       0    21.2    .035       0
#XS Ineff= 2 , 0
               0      50    21.2              50
Permanent Ineff=
       F       F
#Block Obstruct= 2 , 0
                            21.2
Bank Sta=0,21.2
XS Rating Curve= 0
Exp/Cntr=.3,.1

Type RM Length L Ch R = 1 ,1400.00 ,50,50,50
BEGIN DESCRIPTION:
28
END DESCRIPTION:
#Sta/Elev= 14
     -13   41.81      -3   41.81      -2   42.81       0   42.81     4.2   40.81
     6.2   40.51     6.3   39.81     8.7   39.31    12.7   39.31    15.2   39.81
    16.1   40.41    17.3   40.81    21.3   42.81    31.3   42.81
#Mann= 3 , 0 , 0
     -13    .035       0       0    .035       0    21.3    .035       0
#XS Ineff= 2 , 0
               0      50    21.3              50
Permanent Ineff=
       F       F
#Block Obstruct= 2 , 0
                            21.3
Bank Sta=0,21.3
XS Rating Curve= 0
Exp/Cntr=.3,.1

Type RM Length L Ch R = 1 ,1350.00 ,50,50,50
BEGIN DESCRIPTION:
27
END DESCRIPTION:
#Sta/Elev= 14
     -13   41.08      -3   41.08      -2   42.08       0   42.08       4   40.08
       6   39.78     6.1   39.08     8.5   38.58    12.5   38.58      15   39.08
    15.9   39.68    17.1   40.08    21.1   42.08    31.1   42.08
#Mann= 3 , 0 , 0
     -13    .035       0       0    .035       0    21.1    .035       0
#XS Ineff= 2 , 0
               0      50    21.1              50
Permanent Ineff=
       F       F
#Block Obstruct= 2 , 0
                            21.1
Bank Sta=0,21.1
XS Rating Curve= 0
Exp/Cntr=.3,.1

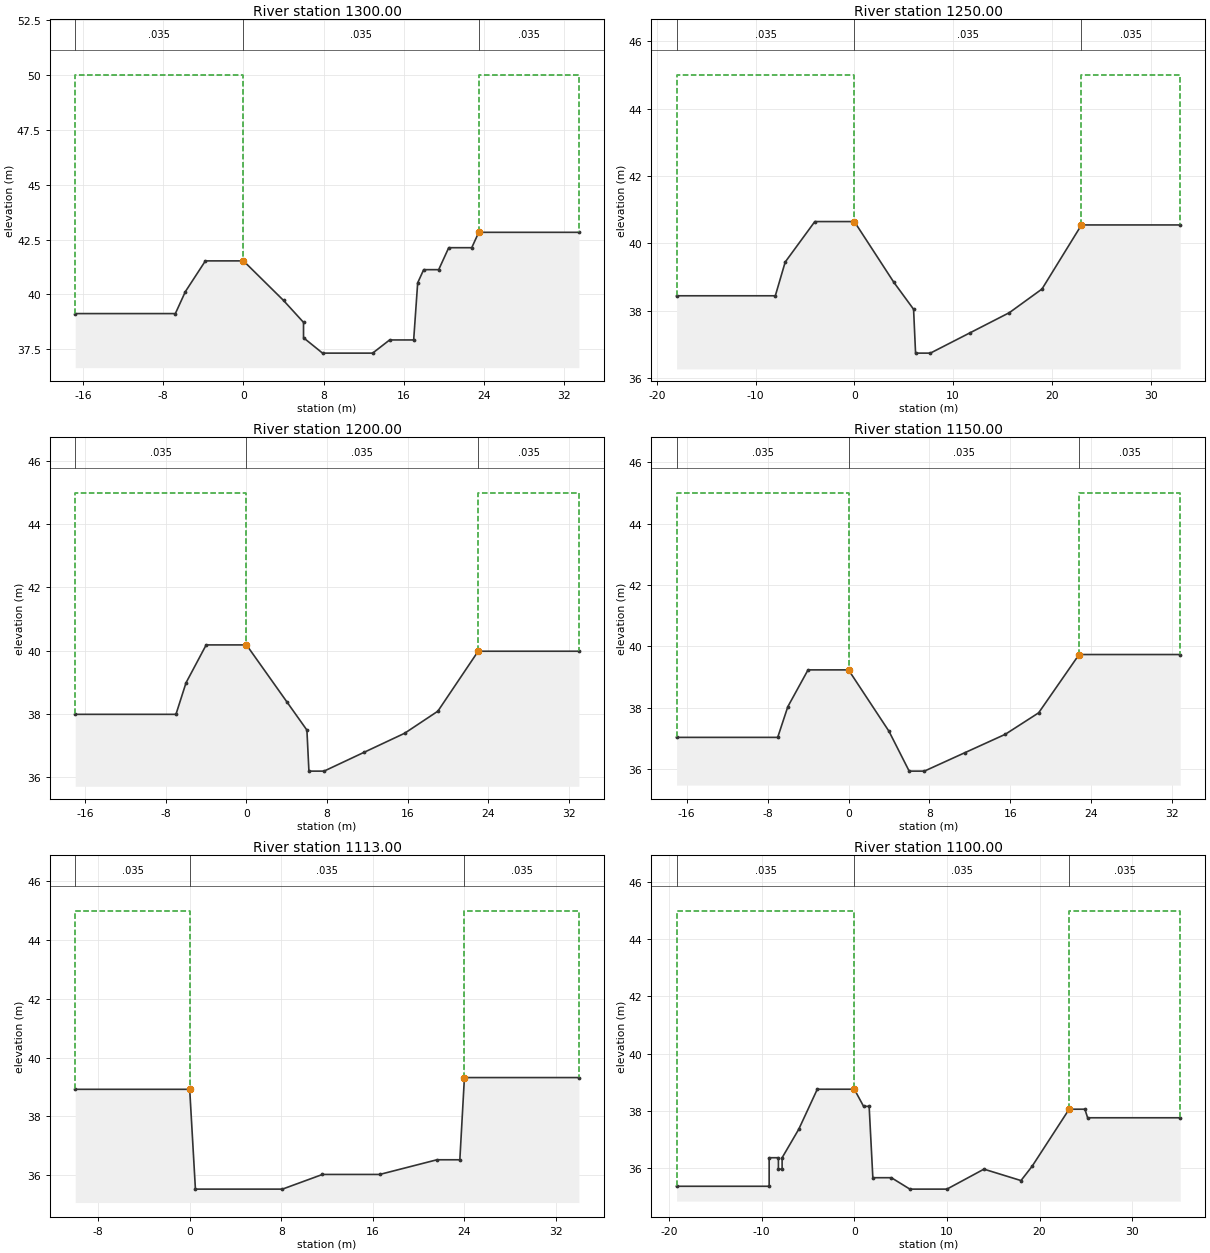
Type RM Length L Ch R = 1 ,1300.00 ,50,50,50
BEGIN DESCRIPTION:
26
END DESCRIPTION:
#Sta/Elev= 19
   -16.8   39.13    -6.8   39.13    -5.8   40.13    -3.8   41.53       0   41.53
       4   39.73       6   38.73       6   38.03     7.9   37.33    12.9   37.33
    14.6   37.93      17   37.93    17.4   40.53      18   41.13    19.5   41.13
    20.5   42.13    22.8   42.13    23.5   42.83    33.5   42.83
#Mann= 3 , 0 , 0
   -16.8    .035       0       0    .035       0    23.5    .035       0
#XS Ineff= 2 , 0
               0      50    23.5              50
Permanent Ineff=
       F       F
#Block Obstruct= 2 , 0
                            23.5
Bank Sta=0,23.5
XS Rating Curve= 0
Exp/Cntr=.3,.1

Type RM Length L Ch R = 1 ,1250.00 ,50,50,50
BEGIN DESCRIPTION:
25
END DESCRIPTION:
#Sta/Elev= 14
     -18   38.45      -8   38.45      -7   39.45      -4   40.65       0   40.65
       4   38.85       6   38.05     6.2   36.75     7.7   36.75    11.7   37.35
    15.7   37.95      19   38.65      23   40.55      33   40.55
#Mann= 3 , 0 , 0
     -18    .035       0       0    .035       0      23    .035       0
#XS Ineff= 2 , 0
               0      45      23              45
Permanent Ineff=
       F       F
#Block Obstruct= 2 , 0
                              23
Bank Sta=0,23
XS Rating Curve= 0
Exp/Cntr=.3,.1

Type RM Length L Ch R = 1 ,1200.00 ,50,50,50
BEGIN DESCRIPTION:
24
END DESCRIPTION:
#Sta/Elev= 14
     -17   37.98      -7   37.98      -6   38.98      -4   40.18       0   40.18
       4   38.38       6   37.48     6.2   36.18     7.7   36.18    11.7   36.78
    15.7   37.38      19   38.08      23   39.98      33   39.98
#Mann= 3 , 0 , 0
     -17    .035       0       0    .035       0      23    .035       0
#XS Ineff= 2 , 0
               0      45      23              45
Permanent Ineff=
       F       F
#Block Obstruct= 2 , 0
                              23
Bank Sta=0,23
XS Rating Curve= 0
Exp/Cntr=.3,.1

Type RM Length L Ch R = 1 ,1150.00 ,37,37,37
BEGIN DESCRIPTION:
23
END DESCRIPTION:
#Sta/Elev= 13
     -17   37.03      -7   37.03      -6   38.03      -4   39.23       0   39.23
       4   37.23       6   35.93     7.5   35.93    11.5   36.53    15.5   37.13
    18.8   37.83    22.8   39.73    32.8   39.73
#Mann= 3 , 0 , 0
     -17    .035       0       0    .035       0    22.8    .035       0
#XS Ineff= 2 , 0
               0      45    22.8              45
Permanent Ineff=
       F       F
#Block Obstruct= 2 , 0
                            22.8
Bank Sta=0,22.8
XS Rating Curve= 0
Exp/Cntr=.3,.1

Type RM Length L Ch R = 1 ,1113.00 ,13,13,13
BEGIN DESCRIPTION:
22.013
END DESCRIPTION:
#Sta/Elev= 10
     -10   38.92       0   38.92      .5   35.52     8.1   35.52    11.6   36.02
    16.6   36.02    21.6   36.52    23.6   36.52      24   39.32      34   39.32
#Mann= 3 , 0 , 0
     -10    .035       0       0    .035       0      24    .035       0
#XS Ineff= 2 , 0
               0      45      24              45
Permanent Ineff=
       F       F
#Block Obstruct= 2 , 0
                              24
Bank Sta=0,24
XS Rating Curve= 0
Exp/Cntr=.3,.1

Type RM Length L Ch R = 1 ,1100.00 ,50,50,50
BEGIN DESCRIPTION:
22
END DESCRIPTION:
#Sta/Elev= 23
   -19.2   35.35    -9.2   35.35    -9.2   36.35    -8.2   36.35    -8.2   35.95
    -7.8   35.95    -7.8   36.35      -6   37.35      -4   38.75       0   38.75
       1   38.15     1.6   38.15       2   35.65       4   35.65       6   35.25
      10   35.25      14   35.95      18   35.55    19.2   36.05    23.2   38.05
    24.9   38.05    25.2   37.75    35.2   37.75
#Mann= 3 , 0 , 0
   -19.2    .035       0       0    .035       0    23.2    .035       0
#XS Ineff= 2 , 0
               0      45    23.2              45
Permanent Ineff=
       F       F
#Block Obstruct= 2 , 0
                            23.2
Bank Sta=0,23.2
XS Rating Curve= 0
Exp/Cntr=.3,.1

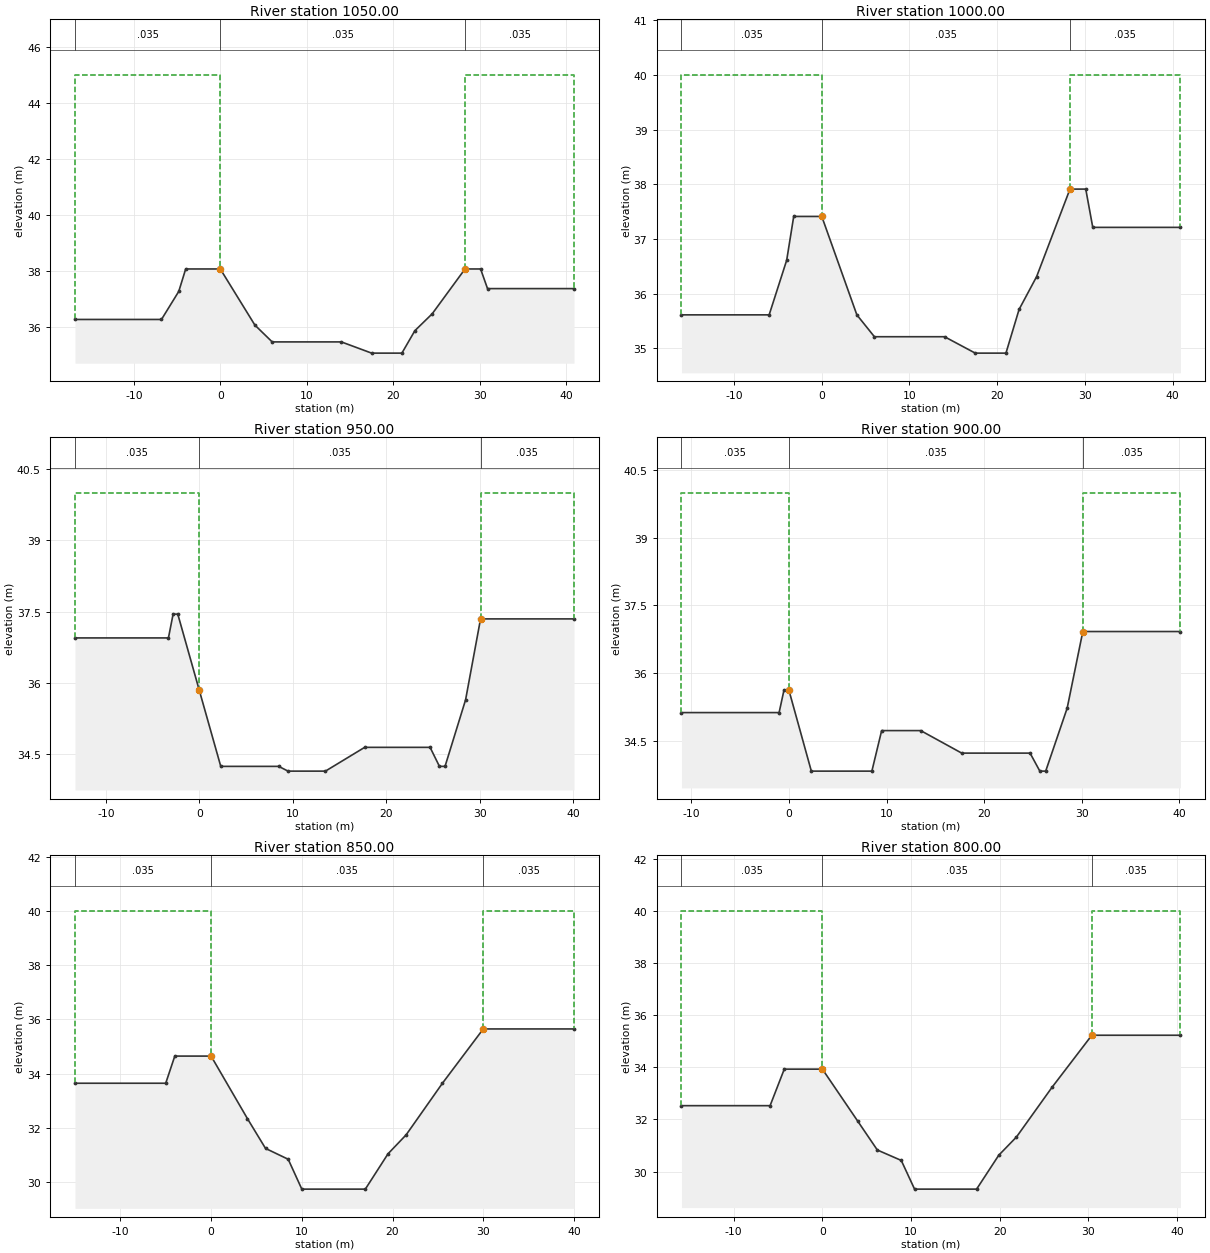
Type RM Length L Ch R = 1 ,1050.00 ,50,50,50
BEGIN DESCRIPTION:
21
END DESCRIPTION:
#Sta/Elev= 16
   -16.8   36.28    -6.8   36.28    -4.8   37.28      -4   38.08       0   38.08
       4   36.08       6   35.48      14   35.48    17.5   35.08      21   35.08
    22.5   35.88    24.5   36.48    28.3   38.08    30.1   38.08    30.9   37.38
    40.9   37.38
#Mann= 3 , 0 , 0
   -16.8    .035       0       0    .035       0    28.3    .035       0
#XS Ineff= 2 , 0
               0      45    28.3              45
Permanent Ineff=
       F       F
#Block Obstruct= 2 , 0
                            28.3
Bank Sta=0,28.3
XS Rating Curve= 0
Exp/Cntr=.3,.1

Type RM Length L Ch R = 1 ,1000.00 ,50,50,50
BEGIN DESCRIPTION:
20
END DESCRIPTION:
#Sta/Elev= 16
     -16   35.61      -6   35.61      -4   36.61    -3.2   37.41       0   37.41
       4   35.61       6   35.21      14   35.21    17.5   34.91      21   34.91
    22.5   35.71    24.5   36.31    28.3   37.91    30.1   37.91    30.9   37.21
    40.9   37.21
#Mann= 3 , 0 , 0
     -16    .035       0       0    .035       0    28.3    .035       0
#XS Ineff= 2 , 0
               0      40    28.3              40
Permanent Ineff=
       F       F
#Block Obstruct= 2 , 0
                            28.3
Bank Sta=0,28.3
XS Rating Curve= 0
Exp/Cntr=.3,.1

Type RM Length L Ch R = 1 ,950.00  ,50,50,50
BEGIN DESCRIPTION:
19
END DESCRIPTION:
#Sta/Elev= 16
   -13.3   36.95    -3.3   36.95    -2.8   37.45    -2.3   37.45       0   35.85
     2.3   34.25     8.5   34.25     9.5   34.15    13.5   34.15    17.7   34.65
    24.7   34.65    25.7   34.25    26.3   34.25    28.5   35.65    30.1   37.35
    40.1   37.35
#Mann= 3 , 0 , 0
   -13.3    .035       0       0    .035       0    30.1    .035       0
#XS Ineff= 2 , 0
               0      40    30.1              40
Permanent Ineff=
       F       F
#Block Obstruct= 2 , 0
                            30.1
Bank Sta=0,30.1
XS Rating Curve= 0
Exp/Cntr=.3,.1

Type RM Length L Ch R = 1 ,900.00  ,50,50,50
BEGIN DESCRIPTION:
18
END DESCRIPTION:
#Sta/Elev= 15
     -11   35.12      -1   35.12     -.5   35.62       0   35.62     2.3   33.82
     8.5   33.82     9.5   34.72    13.5   34.72    17.7   34.22    24.7   34.22
    25.7   33.82    26.3   33.82    28.5   35.22    30.1   36.92    40.1   36.92
#Mann= 3 , 0 , 0
     -11    .035       0       0    .035       0    30.1    .035       0
#XS Ineff= 2 , 0
               0      40    30.1              40
Permanent Ineff=
       F       F
#Block Obstruct= 2 , 0
                            30.1
Bank Sta=0,30.1
XS Rating Curve= 0
Exp/Cntr=.3,.1

Type RM Length L Ch R = 1 ,850.00  ,50,50,50
BEGIN DESCRIPTION:
17
END DESCRIPTION:
#Sta/Elev= 14
     -15   33.65      -5   33.65      -4   34.65       0   34.65       4   32.35
       6   31.25     8.5   30.85      10   29.75      17   29.75    19.5   31.05
    21.5   31.75    25.5   33.65      30   35.65      40   35.65
#Mann= 3 , 0 , 0
     -15    .035       0       0    .035       0      30    .035       0
#XS Ineff= 2 , 0
               0      40      30              40
Permanent Ineff=
       F       F
#Block Obstruct= 2 , 0
                              30
Bank Sta=0,30
XS Rating Curve= 0
Exp/Cntr=.3,.1

Type RM Length L Ch R = 1 ,800.00  ,50,50,50
BEGIN DESCRIPTION:
16
END DESCRIPTION:
#Sta/Elev= 14
   -15.9   32.53    -5.9   32.53    -4.3   33.93       0   33.93       4   31.93
     6.2   30.83     8.9   30.43    10.4   29.33    17.4   29.33    19.9   30.63
    21.9   31.33    25.9   33.23    30.4   35.23    40.4   35.23
#Mann= 3 , 0 , 0
   -15.9    .035       0       0    .035       0    30.4    .035       0
#XS Ineff= 2 , 0
               0      40    30.4              40
Permanent Ineff=
       F       F
#Block Obstruct= 2 , 0
                            30.4
Bank Sta=0,30.4
XS Rating Curve= 0
Exp/Cntr=.3,.1

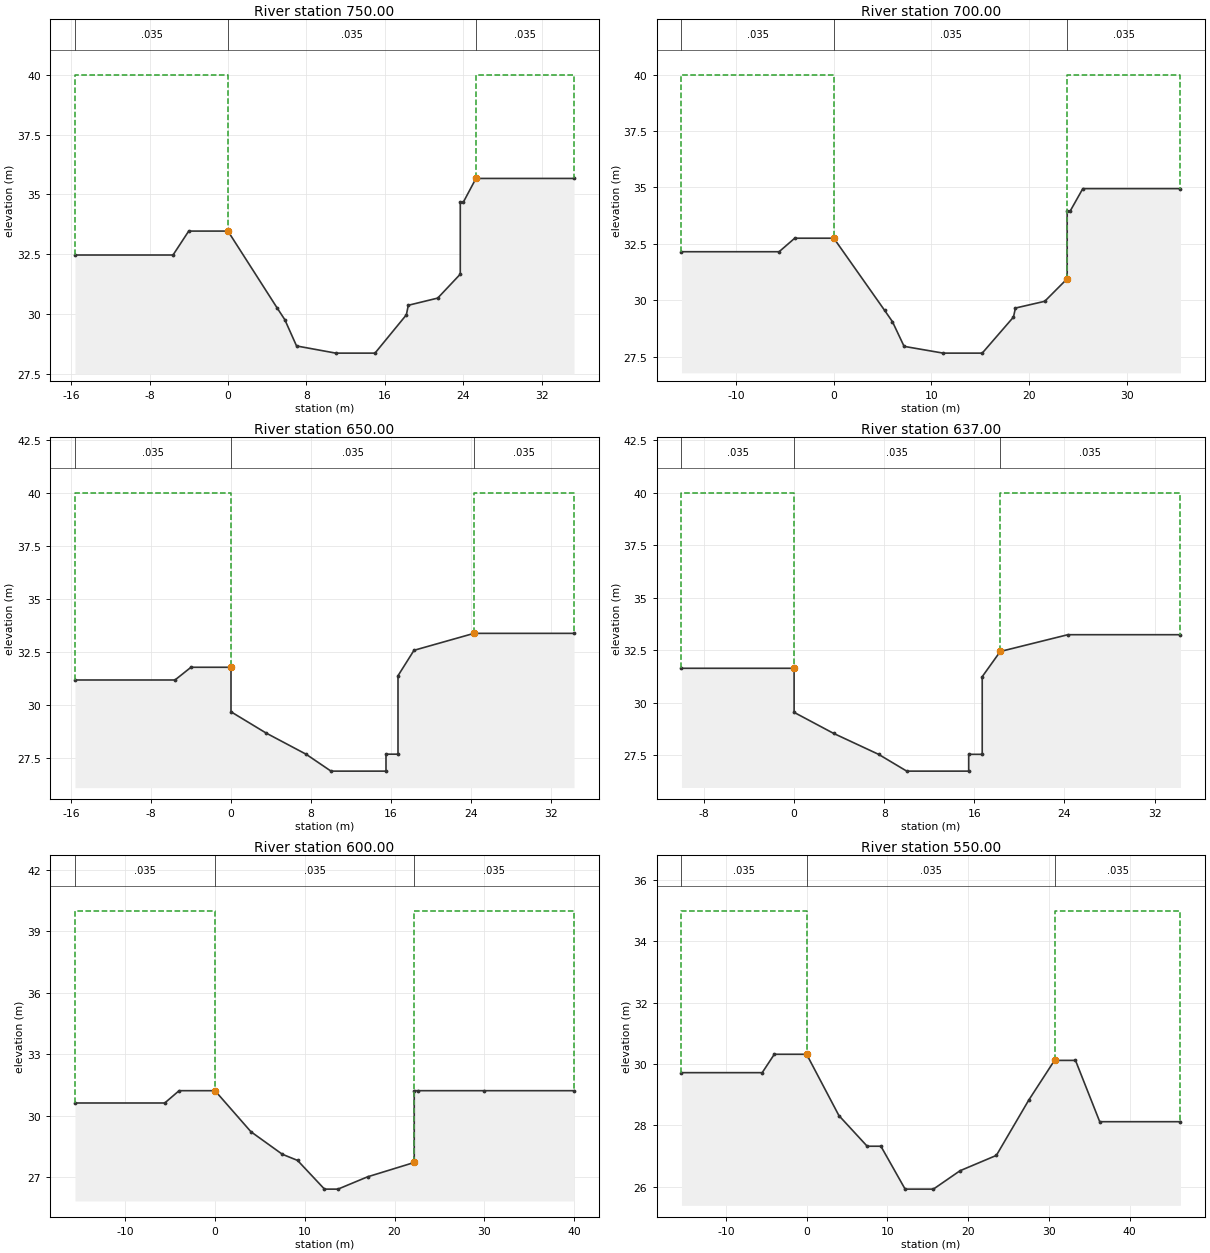
Type RM Length L Ch R = 1 ,750.00  ,50,50,50
BEGIN DESCRIPTION:
15
END DESCRIPTION:
#Sta/Elev= 17
   -15.6   32.47    -5.6   32.47      -4   33.47       0   33.47       5   30.27
     5.8   29.77       7   28.67      11   28.37      15   28.37    18.2   29.97
    18.4   30.37    21.4   30.67    23.7   31.67    23.7   34.67      24   34.67
    25.3   35.67    35.3   35.67
#Mann= 3 , 0 , 0
   -15.6    .035       0       0    .035       0    25.3    .035       0
#XS Ineff= 2 , 0
               0      40    25.3              40
Permanent Ineff=
       F       F
#Block Obstruct= 2 , 0
                            25.3
Bank Sta=0,25.3
XS Rating Curve= 0
Exp/Cntr=.3,.1

Type RM Length L Ch R = 1 ,700.00  ,50,50,50
BEGIN DESCRIPTION:
14
END DESCRIPTION:
#Sta/Elev= 17
   -15.6   32.15    -5.6   32.15      -4   32.75       0   32.75     5.2   29.55
       6   29.05     7.2   27.95    11.2   27.65    15.2   27.65    18.4   29.25
    18.6   29.65    21.6   29.95    23.9   30.95    23.9   33.95    24.2   33.95
    25.5   34.95    35.5   34.95
#Mann= 3 , 0 , 0
   -15.6    .035       0       0    .035       0    23.9    .035       0
#XS Ineff= 2 , 0
               0      40    23.9              40
Permanent Ineff=
       F       F
#Block Obstruct= 2 , 0
                            23.9
Bank Sta=0,23.9
XS Rating Curve= 0
Exp/Cntr=.3,.1

Type RM Length L Ch R = 1 ,650.00  ,13,13,13
BEGIN DESCRIPTION:
13
END DESCRIPTION:
#Sta/Elev= 15
   -15.6   31.17    -5.6   31.17      -4   31.77       0   31.77       0   29.67
     3.5   28.67     7.5   27.67      10   26.87    15.5   26.87    15.5   27.67
    16.7   27.67    16.7   31.37    18.3   32.57    24.3   33.37    34.3   33.37
#Mann= 3 , 0 , 0
   -15.6    .035       0       0    .035       0    24.3    .035       0
#XS Ineff= 2 , 0
               0      40    24.3              40
Permanent Ineff=
       F       F
#Block Obstruct= 2 , 0
                            24.3
Bank Sta=0,24.3
XS Rating Curve= 0
Exp/Cntr=.3,.1

Type RM Length L Ch R = 1 ,637.00  ,37,37,37
BEGIN DESCRIPTION:
12.037
END DESCRIPTION:
#Sta/Elev= 13
     -10   31.64       0   31.64       0   29.54     3.5   28.54     7.5   27.54
      10   26.74    15.5   26.74    15.5   27.54    16.7   27.54    16.7   31.24
    18.3   32.44    24.3   33.24    34.3   33.24
#Mann= 3 , 0 , 0
     -10    .035       0       0    .035       0    18.3    .035       0
#XS Ineff= 2 , 0
               0      40    18.3              40
Permanent Ineff=
       F       F
#Block Obstruct= 2 , 0
                            18.3
Bank Sta=0,18.3
XS Rating Curve= 0
Exp/Cntr=.3,.1

Type RM Length L Ch R = 1 ,600.00  ,50,50,50
BEGIN DESCRIPTION:
12
END DESCRIPTION:
#Sta/Elev= 15
   -15.6   30.63    -5.6   30.63      -4   31.23       0   31.23       4   29.23
     7.5   28.13     9.2   27.83    12.2   26.43    13.7   26.43      17   27.03
    22.2   27.73    22.2   31.23    22.6   31.23      30   31.23      40   31.23
#Mann= 3 , 0 , 0
   -15.6    .035       0       0    .035       0    22.2    .035       0
#XS Ineff= 2 , 0
               0      40    22.2              40
Permanent Ineff=
       F       F
#Block Obstruct= 2 , 0
                            22.2
Bank Sta=0,22.2
XS Rating Curve= 0
Exp/Cntr=.3,.1

Type RM Length L Ch R = 1 ,550.00  ,50,50,50
BEGIN DESCRIPTION:
11
END DESCRIPTION:
#Sta/Elev= 16
   -15.5   29.72    -5.5   29.72      -4   30.32       0   30.32       4   28.32
     7.5   27.32     9.2   27.32    12.2   25.92    15.7   25.92      19   26.52
    23.5   27.02    27.5   28.82    30.7   30.12    33.3   30.12    36.3   28.12
    46.3   28.12
#Mann= 3 , 0 , 0
   -15.5    .035       0       0    .035       0    30.7    .035       0
#XS Ineff= 2 , 0
               0      35    30.7              35
Permanent Ineff=
       F       F
#Block Obstruct= 2 , 0
                            30.7
Bank Sta=0,30.7
XS Rating Curve= 0
Exp/Cntr=.3,.1

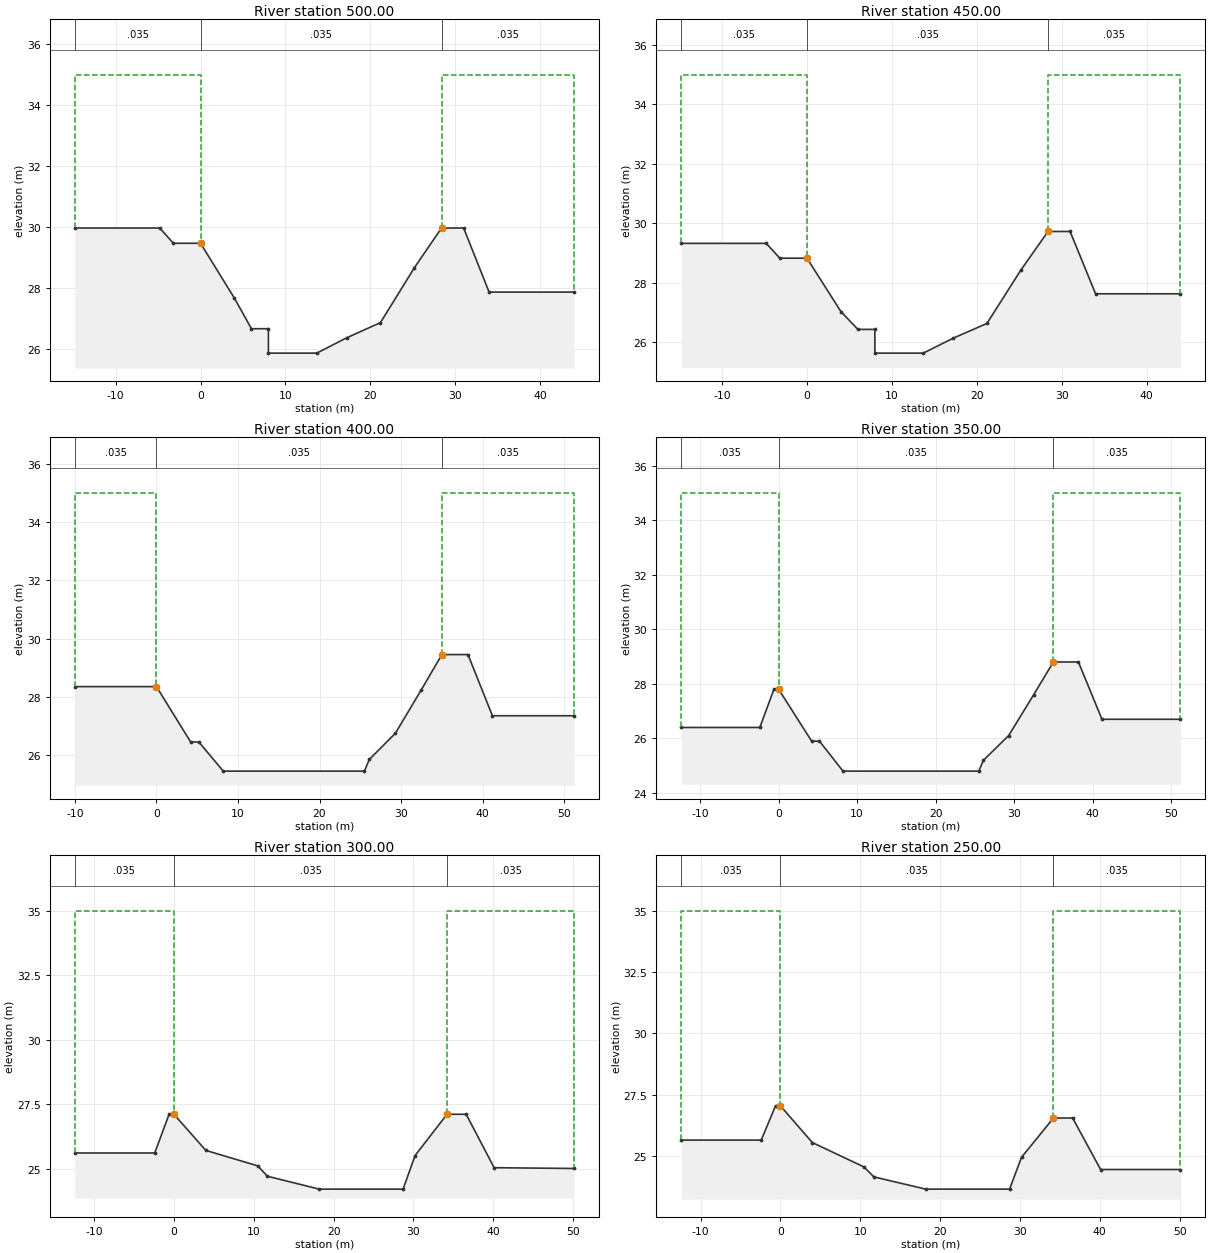
Type RM Length L Ch R = 1 ,500.00  ,50,50,50
BEGIN DESCRIPTION:
10
END DESCRIPTION:
#Sta/Elev= 16
   -14.8   29.98    -4.8   29.98    -3.2   29.48       0   29.48       4   27.68
       6   26.68       8   26.68       8   25.88    13.7   25.88    17.2   26.38
    21.2   26.88    25.2   28.68    28.4   29.98      31   29.98      34   27.88
      44   27.88
#Mann= 3 , 0 , 0
   -14.8    .035       0       0    .035       0    28.4    .035       0
#XS Ineff= 2 , 0
               0      35    28.4              35
Permanent Ineff=
       F       F
#Block Obstruct= 2 , 0
                            28.4
Bank Sta=0,28.4
XS Rating Curve= 0
Exp/Cntr=.3,.1

Type RM Length L Ch R = 1 ,450.00  ,50,50,50
BEGIN DESCRIPTION:
9
END DESCRIPTION:
#Sta/Elev= 16
   -14.8   29.32    -4.8   29.32    -3.2   28.82       0   28.82       4   27.02
       6   26.42       8   26.42       8   25.62    13.7   25.62    17.2   26.12
    21.2   26.62    25.2   28.42    28.4   29.72      31   29.72      34   27.62
      44   27.62
#Mann= 3 , 0 , 0
   -14.8    .035       0       0    .035       0    28.4    .035       0
#XS Ineff= 2 , 0
               0      35    28.4              35
Permanent Ineff=
       F       F
#Block Obstruct= 2 , 0
                            28.4
Bank Sta=0,28.4
XS Rating Curve= 0
Exp/Cntr=.3,.1

Type RM Length L Ch R = 1 ,400.00  ,50,50,50
BEGIN DESCRIPTION:
8
END DESCRIPTION:
#Sta/Elev= 13
     -10   28.35       0   28.35     4.2   26.45     5.2   26.45     8.2   25.45
    25.5   25.45    26.1   25.85    29.3   26.75    32.5   28.25      35   29.45
    38.2   29.45    41.2   27.35    51.2   27.35
#Mann= 3 , 0 , 0
     -10    .035       0       0    .035       0      35    .035       0
#XS Ineff= 2 , 0
               0      35      35              35
Permanent Ineff=
       F       F
#Block Obstruct= 2 , 0
                              35
Bank Sta=0,35
XS Rating Curve= 0
Exp/Cntr=.3,.1

Type RM Length L Ch R = 1 ,350.00  ,50,50,50
BEGIN DESCRIPTION:
7
END DESCRIPTION:
#Sta/Elev= 15
   -12.4    26.4    -2.4    26.4     -.6    27.8       0    27.8     4.2    25.9
     5.2    25.9     8.2    24.8    25.5    24.8    26.1    25.2    29.3    26.1
    32.5    27.6      35    28.8    38.2    28.8    41.2    26.7    51.2    26.7
#Mann= 3 , 0 , 0
   -12.4    .035       0       0    .035       0      35    .035       0
#XS Ineff= 2 , 0
               0      35      35              35
Permanent Ineff=
       F       F
#Block Obstruct= 2 , 0
                              35
Bank Sta=0,35
XS Rating Curve= 0
Exp/Cntr=.3,.1

Type RM Length L Ch R = 1 ,300.00  ,50,50,50
BEGIN DESCRIPTION:
6
END DESCRIPTION:
#Sta/Elev= 14
   -12.4   25.62    -2.4   25.62     -.6   27.12       0   27.12       4   25.72
    10.5   25.12    11.7   24.72    18.2   24.22    28.7   24.22    30.2   25.52
    34.2   27.12    36.6   27.12    40.1   25.05    50.1   25.02
#Mann= 3 , 0 , 0
   -12.4    .035       0       0    .035       0    34.2    .035       0
#XS Ineff= 2 , 0
               0      35    34.2              35
Permanent Ineff=
       F       F
#Block Obstruct= 2 , 0
                            34.2
Bank Sta=0,34.2
XS Rating Curve= 0
Exp/Cntr=.3,.1

Type RM Length L Ch R = 1 ,250.00  ,50,50,50
BEGIN DESCRIPTION:
5
END DESCRIPTION:
#Sta/Elev= 14
   -12.4   25.65    -2.4   25.65     -.6   27.05       0   27.05       4   25.55
    10.5   24.55    11.7   24.15    18.2   23.65    28.7   23.65    30.2   24.95
    34.2   26.55    36.6   26.55    40.1   24.45    50.1   24.45
#Mann= 3 , 0 , 0
   -12.4    .035       0       0    .035       0    34.2    .035       0
#XS Ineff= 2 , 0
               0      35    34.2              35
Permanent Ineff=
       F       F
#Block Obstruct= 2 , 0
                            34.2
Bank Sta=0,34.2
XS Rating Curve= 0
Exp/Cntr=.3,.1