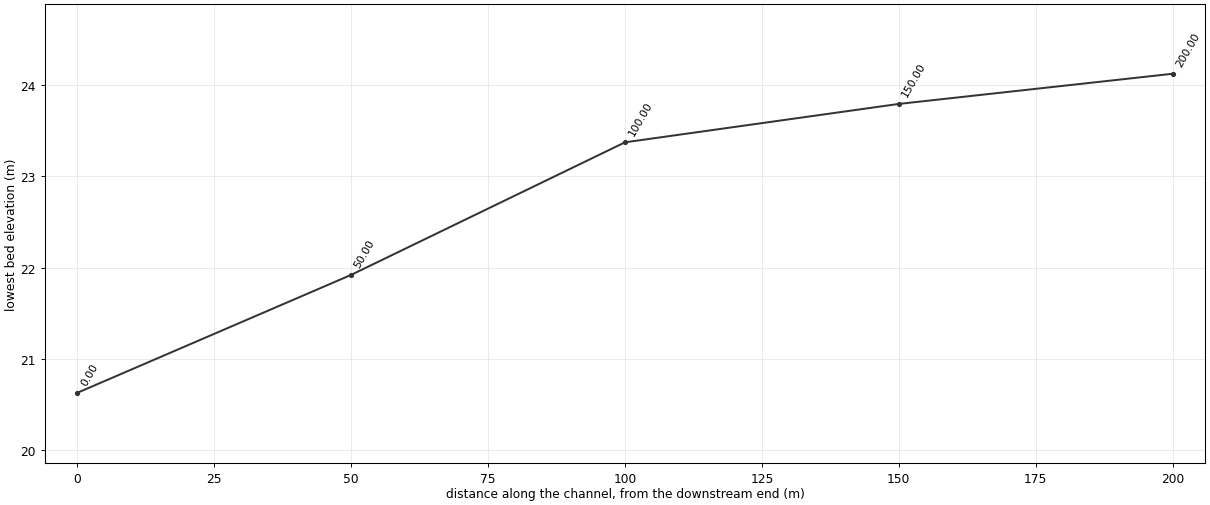
HEC-RAS study YAC.prj: YEUMYA

--- YAC.g01 (geometry) --- (continued)

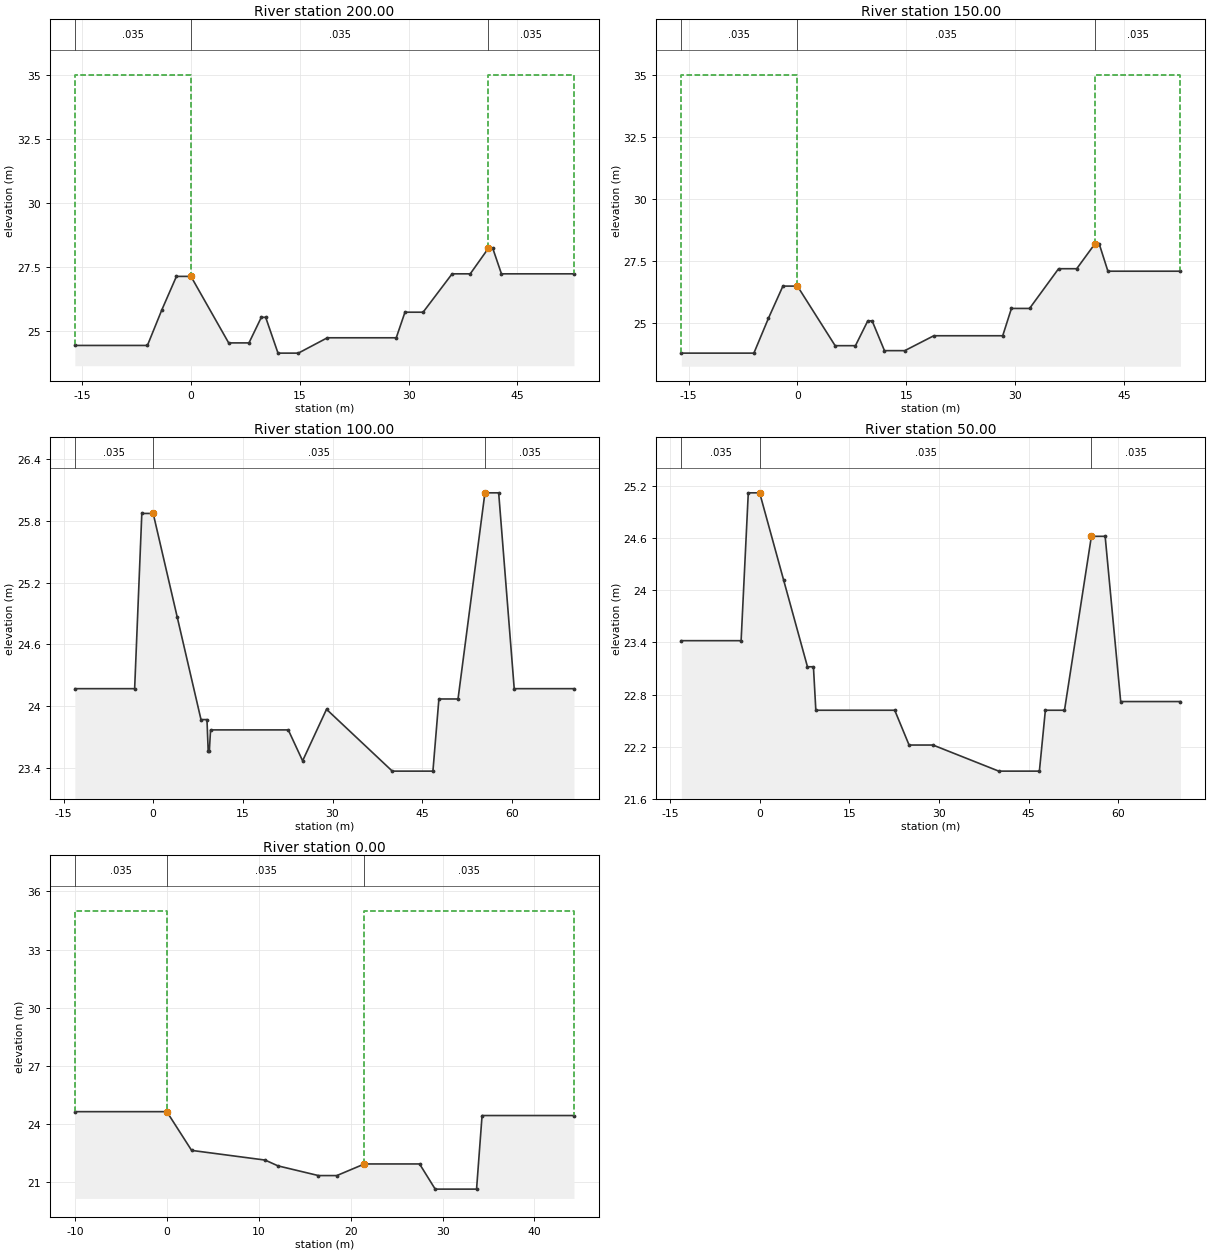
Type RM Length L Ch R = 1 ,200.00  ,50,50,50
BEGIN DESCRIPTION:
4
END DESCRIPTION:
#Sta/Elev= 21
     -16   24.42      -6   24.42      -4   25.82      -2   27.12       0   27.12
     5.2   24.52       8   24.52     9.7   25.52    10.3   25.52      12   24.12
    14.8   24.12    18.8   24.72    28.3   24.72    29.5   25.72      32   25.72
      36   27.22    38.5   27.22      41   28.22    41.6   28.22    42.8   27.22
    52.8   27.22
#Mann= 3 , 0 , 0
     -16    .035       0       0    .035       0      41    .035       0
#XS Ineff= 2 , 0
               0      35      41              35
Permanent Ineff=
       F       F
#Block Obstruct= 2 , 0
                              41
Bank Sta=0,41
XS Rating Curve= 0
Exp/Cntr=.3,.1

Type RM Length L Ch R = 1 ,150.00  ,50,50,50
BEGIN DESCRIPTION:
3
END DESCRIPTION:
#Sta/Elev= 21
     -16   23.79      -6   23.79      -4   25.19      -2   26.49       0   26.49
     5.2   24.09       8   24.09     9.7   25.09    10.3   25.09      12   23.89
    14.8   23.89    18.8   24.49    28.3   24.49    29.5   25.59      32   25.59
      36   27.19    38.5   27.19      41   28.19    41.6   28.19    42.8   27.09
    52.8   27.09
#Mann= 3 , 0 , 0
     -16    .035       0       0    .035       0      41    .035       0
#XS Ineff= 2 , 0
               0      35      41              35
Permanent Ineff=
       F       F
#Block Obstruct= 2 , 0
                              41
Bank Sta=0,41
XS Rating Curve= 0
Exp/Cntr=.3,.1

Type RM Length L Ch R = 1 ,100.00  ,50,50,50
BEGIN DESCRIPTION:
2
END DESCRIPTION:
#Sta/Elev= 21
   -13.1   24.17    -3.1   24.17    -1.9   25.87       0   25.87       4   24.87
       8   23.87       9   23.87     9.2   23.57     9.4   23.57     9.6   23.77
    22.6   23.77      25   23.47      29   23.97      40   23.37    46.8   23.37
    47.8   24.07      51   24.07    55.5   26.07    57.8   26.07    60.4   24.17
    70.4   24.17
#Mann= 3 , 0 , 0
   -13.1    .035       0       0    .035       0    55.5    .035       0
#XS Ineff= 2 , 0
               0      35    55.5              35
Permanent Ineff=
       F       F
#Block Obstruct= 2 , 0
                            55.5
Bank Sta=0,55.5
XS Rating Curve= 0
Exp/Cntr=.3,.1

Type RM Length L Ch R = 1 ,50.00   ,50,50,50
BEGIN DESCRIPTION:
1
END DESCRIPTION:
#Sta/Elev= 19
   -13.1   23.42    -3.1   23.42    -1.9   25.12       0   25.12       4   24.12
       8   23.12       9   23.12     9.4   22.62    22.6   22.62      25   22.22
      29   22.22      40   21.92    46.8   21.92    47.8   22.62      51   22.62
    55.5   24.62    57.8   24.62    60.4   22.72    70.4   22.72
#Mann= 3 , 0 , 0
   -13.1    .035       0       0    .035       0    55.5    .035       0
#XS Ineff= 2 , 0
               0      35    55.5              35
Permanent Ineff=
       F       F
#Block Obstruct= 2 , 0
                            55.5
Bank Sta=0,55.5
XS Rating Curve= 0
Exp/Cntr=.3,.1

Type RM Length L Ch R = 1 ,0.00    ,0,0,0
BEGIN DESCRIPTION:
0
END DESCRIPTION:
#Sta/Elev= 13
     -10   24.63       0   24.63     2.7   22.63    10.7   22.13    12.1   21.83
    16.5   21.33    18.5   21.33    21.5   21.93    27.5   21.93    29.2   20.63
    33.7   20.63    34.3   24.43    44.3   24.43
#Mann= 3 , 0 , 0
     -10    .035       0       0    .035       0    21.5    .035       0
#XS Ineff= 2 , 0
               0      35    21.5              35
Permanent Ineff=
       F       F
#Block Obstruct= 2 , 0
                            21.5
Bank Sta=0,21.5
XS Rating Curve= 0
Exp/Cntr=.3,.1

Chan Stop Cuts=-1