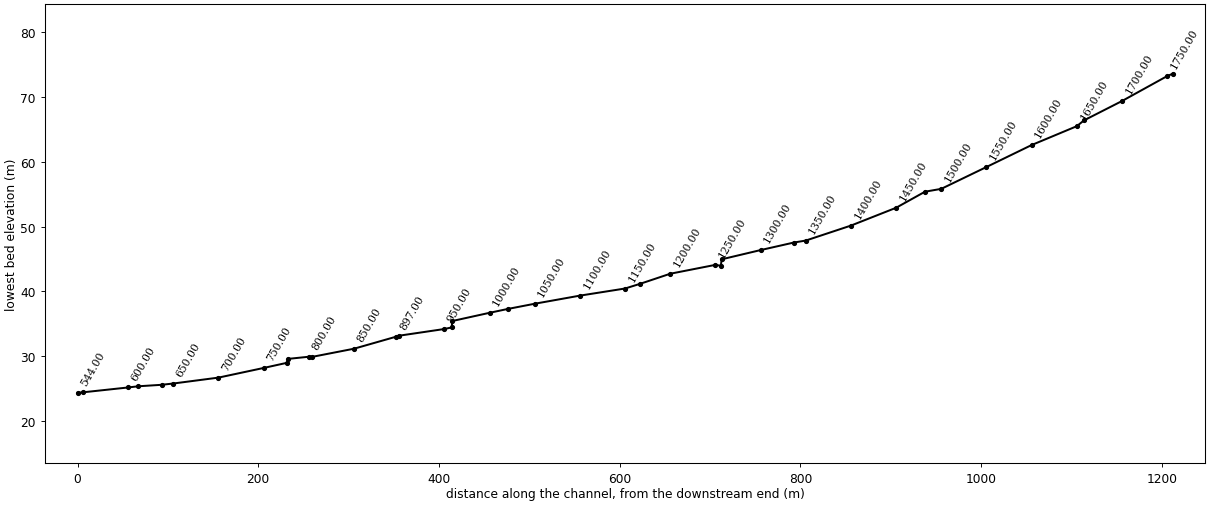
--- NSC.prj (project) ---

Proj Title=NEUNGSIN
Current Plan=p01
Default Exp/Contr=.3,.1
SI Units
Geom File=g01
Flow File=f01
Plan File=p01
Y Axis Title=Elevation
X Axis Title(PF)=Main Channel Distance
X Axis Title(XS)=Station
BEGIN DESCRIPTION:
           BACK WATER COMPUTATION
      APPLICATION OF HEC-2 BY Samju Construction Engineering
      nungsin-ch: 10,20,30,50,80 yr
END DESCRIPTION:
DSS Export Rating Curves= 0
DSS Export Rating Curve Sorted= 0
DSS Export Volume Flow Curves= 0
DXF OffsetX= 0
DXF OffsetY= 0
DXF ScaleX= 1
DXF ScaleY= 10

--- NSC.p01 (plan) ---

Plan Title=Imported Plan 01
Version=Version 3.0.1  Mar 2001
Short Identifier=Imported Pla
Geom File=g01
Flow File=f01
Subcritical Flow
K Sum by GR= 0
Std Step Tol= 0.003
Critical Tol= 0.003
Num of Std Step Trials= 20
Max Error Tol= 0.1
Flow Tol Ratio= 0.001
Split Flow NTrial= 30
Split Flow Tol= 0.02
Split Flow Ratio= 0.02
Log Output Level= 0
Friction Slope Method= 1
Unsteady Friction Slope Method= 2
Parabolic Critical Depth
Global Vel Dist= 0 , 0 , 0
Global Log Level= 0
CheckData=True
Encroach Param=-1 ,0,0, 0
Computation Interval=1HOUR
Output Interval=1HOUR
Run HTab= 0
Run UNet= 0
Run PostProcess= 0
UNET Theta= 1
UNET ZTol= 0.02
UNET ZSATol= 0.1
UNET MxIter= 20
UNET MaxInSteps= 20
UNET DtIC= 0
UNET DtMin= 0
UNET MaxCRTS= 20
UNET WFStab= 2
UNET SFStab= 1
UNET WFX= 1
UNET SFX= 1
UNET Convert EG Bridges=-1
UNET Use Existing IB Tables=-1
Instantaneous Interval=1HOUR
Write IC File= 0
Write Velocity= 0
Write Detailed= 0

--- NSC.f01 (steady flow) ---

Flow Title=Imported Flow 01
Version=Version 3.0.1  Mar 2001
Number of Profiles= 5
Profile Names=10yr,20yr,30yr,50yr,80yr
River Rch & RM=NEUNGSIN,NEUNGSIN        ,1756.00
    14.6   16.08   16.95   18.04   19.04
River Rch & RM=NEUNGSIN,NEUNGSIN        ,550.00
   18.37   20.25   21.34   22.72   23.99
Boundary for River Rch & Prof#=NEUNGSIN,NEUNGSIN        , 1
Up Type= 0
Dn Type= 3
Dn Slope=.034
Boundary for River Rch & Prof#=NEUNGSIN,NEUNGSIN        , 2
Up Type= 0
Dn Type= 3
Dn Slope=.034
Boundary for River Rch & Prof#=NEUNGSIN,NEUNGSIN        , 3
Up Type= 0
Dn Type= 3
Dn Slope=.034
Boundary for River Rch & Prof#=NEUNGSIN,NEUNGSIN        , 4
Up Type= 0
Dn Type= 3
Dn Slope=.034
Boundary for River Rch & Prof#=NEUNGSIN,NEUNGSIN        , 5
Up Type= 0
Dn Type= 3
Dn Slope=.034
DSS Import GetInterval= 0
DSS Import GetPeak= 0
DSS Import FillOption= 0

--- NSC.g01 (geometry) ---

Geom Title=Imported Geom 01
Version=Version 3.0.1  Mar 2001

River Reach=NEUNGSIN        ,NEUNGSIN
Reach XY= 2
              .5             .95              .5             .05

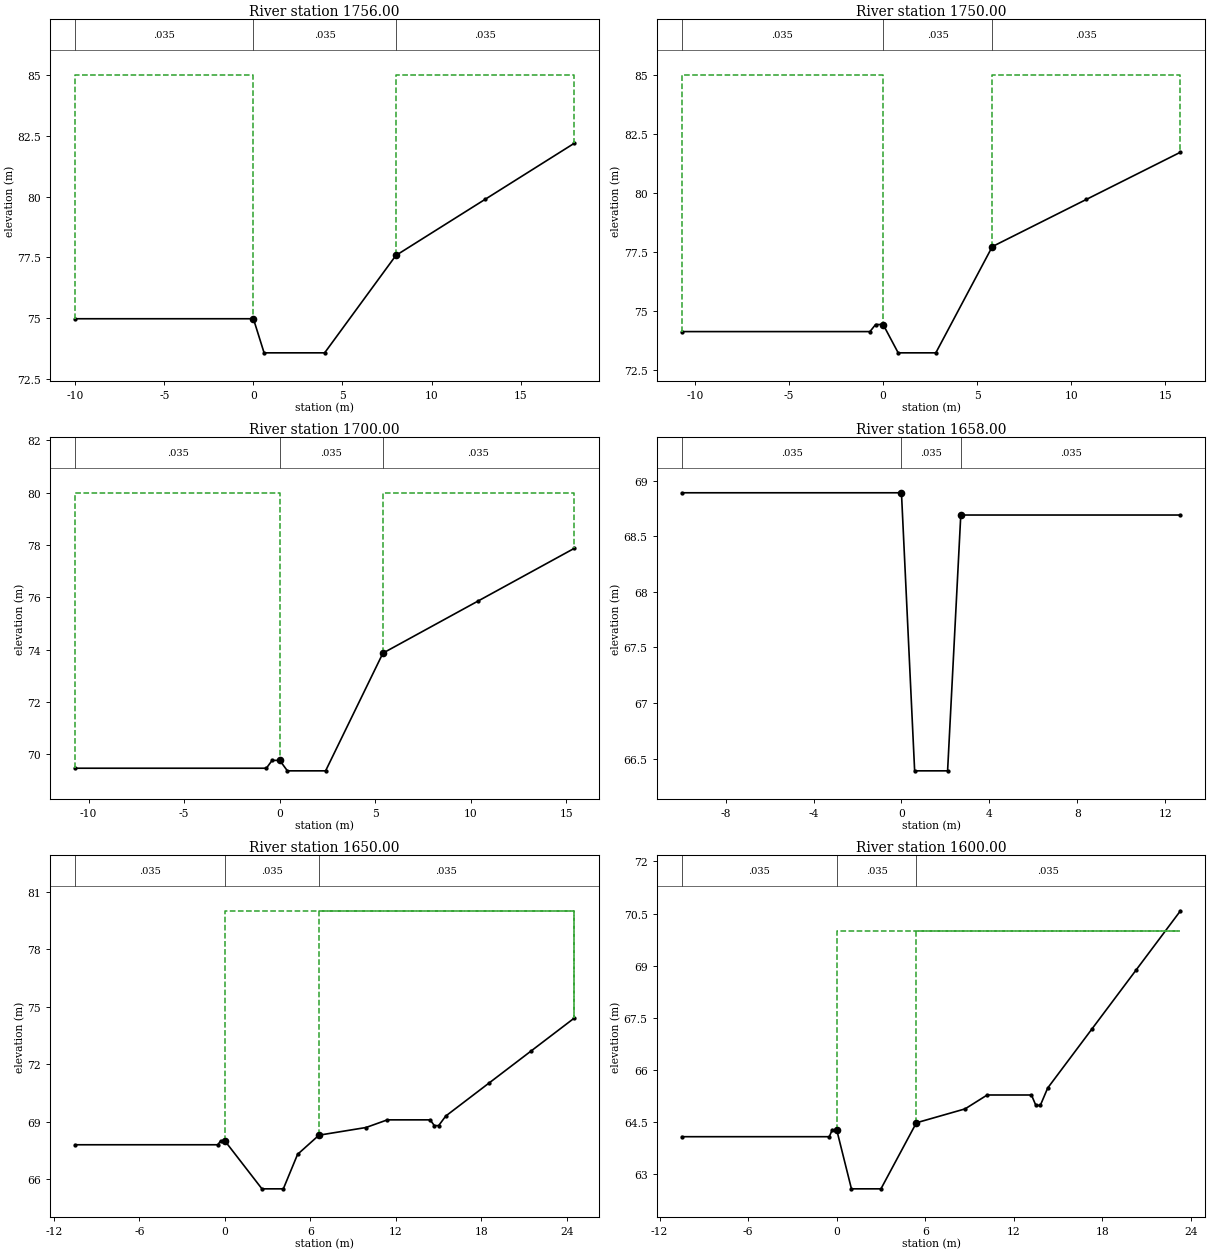
Type RM Length L Ch R = 1 ,1756.00 ,6,6,6
BEGIN DESCRIPTION:
36.006
END DESCRIPTION:
#Sta/Elev= 7
     -10   74.98       0   74.98      .6   73.58       4   73.58       8   77.58
      13   79.88      18   82.18
#Mann= 3 , 0 , 0
     -10    .035       0       0    .035       0       8    .035       0
#XS Ineff= 2 , 0
               0      85       8              85
Permanent Ineff=
       F       F
#Block Obstruct= 2 , 0
                               8
Bank Sta=0,8
XS Rating Curve= 0
Exp/Cntr=.3,.1

Type RM Length L Ch R = 1 ,1750.00 ,50,50,50
BEGIN DESCRIPTION:
36
END DESCRIPTION:
#Sta/Elev= 9
   -10.7   74.12     -.7   74.12     -.4   74.42       0   74.42      .8   73.22
     2.8   73.22     5.8   77.72    10.8   79.72    15.8   81.72
#Mann= 3 , 0 , 0
   -10.7    .035       0       0    .035       0     5.8    .035       0
#XS Ineff= 2 , 0
               0      85     5.8              85
Permanent Ineff=
       F       F
#Block Obstruct= 2 , 0
                             5.8
Bank Sta=0,5.8
XS Rating Curve= 0
Exp/Cntr=.3,.1

Type RM Length L Ch R = 1 ,1700.00 ,42,42,42
BEGIN DESCRIPTION:
35
END DESCRIPTION:
#Sta/Elev= 9
   -10.7   69.47     -.7   69.47     -.4   69.77       0   69.77      .4   69.37
     2.4   69.37     5.4   73.87    10.4   75.87    15.4   77.87
#Mann= 3 , 0 , 0
   -10.7    .035       0       0    .035       0     5.4    .035       0
#XS Ineff= 2 , 0
               0      80     5.4              80
Permanent Ineff=
       F       F
#Block Obstruct= 2 , 0
                             5.4
Bank Sta=0,5.4
XS Rating Curve= 0
Exp/Cntr=.3,.1

Type RM Length L Ch R = 1 ,1658.00 ,8,8,8
BEGIN DESCRIPTION:
34.008
END DESCRIPTION:
#Sta/Elev= 6
     -10   68.89       0   68.89      .6   66.39     2.1   66.39     2.7   68.69
    12.7   68.69
#Mann= 3 , 0 , 0
     -10    .035       0       0    .035       0     2.7    .035       0
#XS Ineff= 2 , 0
               0      80     2.7              80
Permanent Ineff=
       F       F
#Block Obstruct= 2 , 0
                             2.7
Bank Sta=0,2.7
XS Rating Curve= 0
Exp/Cntr=.3,.1

Type RM Length L Ch R = 1 ,1650.00 ,50,50,50
BEGIN DESCRIPTION:
34
END DESCRIPTION:
#Sta/Elev= 17
   -10.5   67.79     -.5   67.79     -.3   67.99       0   67.99     2.6   65.49
     4.1   65.49     5.1   67.29     6.6   68.29     9.9   68.69    11.4   69.09
    14.4   69.09    14.7   68.79      15   68.79    15.5   69.29    18.5   70.99
    21.5   72.69    24.5   74.39
#Mann= 3 , 0 , 0
   -10.5    .035       0       0    .035       0     6.6    .035       0
#XS Ineff= 2 , 0
       0       0      80     6.6       0      80
Permanent Ineff=
       F       F
#Block Obstruct= 2 , 0
       0                     6.6       0
Bank Sta=0,6.6
XS Rating Curve= 0
Exp/Cntr=.3,.1

Type RM Length L Ch R = 1 ,1600.00 ,50,50,50
BEGIN DESCRIPTION:
33
END DESCRIPTION:
#Sta/Elev= 16
   -10.5   64.08     -.5   64.08     -.3   64.28       0   64.28       1   62.58
       3   62.58     5.4   64.48     8.7   64.88    10.2   65.28    13.2   65.28
    13.5   64.98    13.8   64.98    14.3   65.48    17.3   67.18    20.3   68.88
    23.3   70.58
#Mann= 3 , 0 , 0
   -10.5    .035       0       0    .035       0     5.4    .035       0
#XS Ineff= 2 , 0
       0       0      70     5.4       0      70
Permanent Ineff=
       F       F
#Block Obstruct= 2 , 0
       0                     5.4       0
Bank Sta=0,5.4
XS Rating Curve= 0
Exp/Cntr=.3,.1

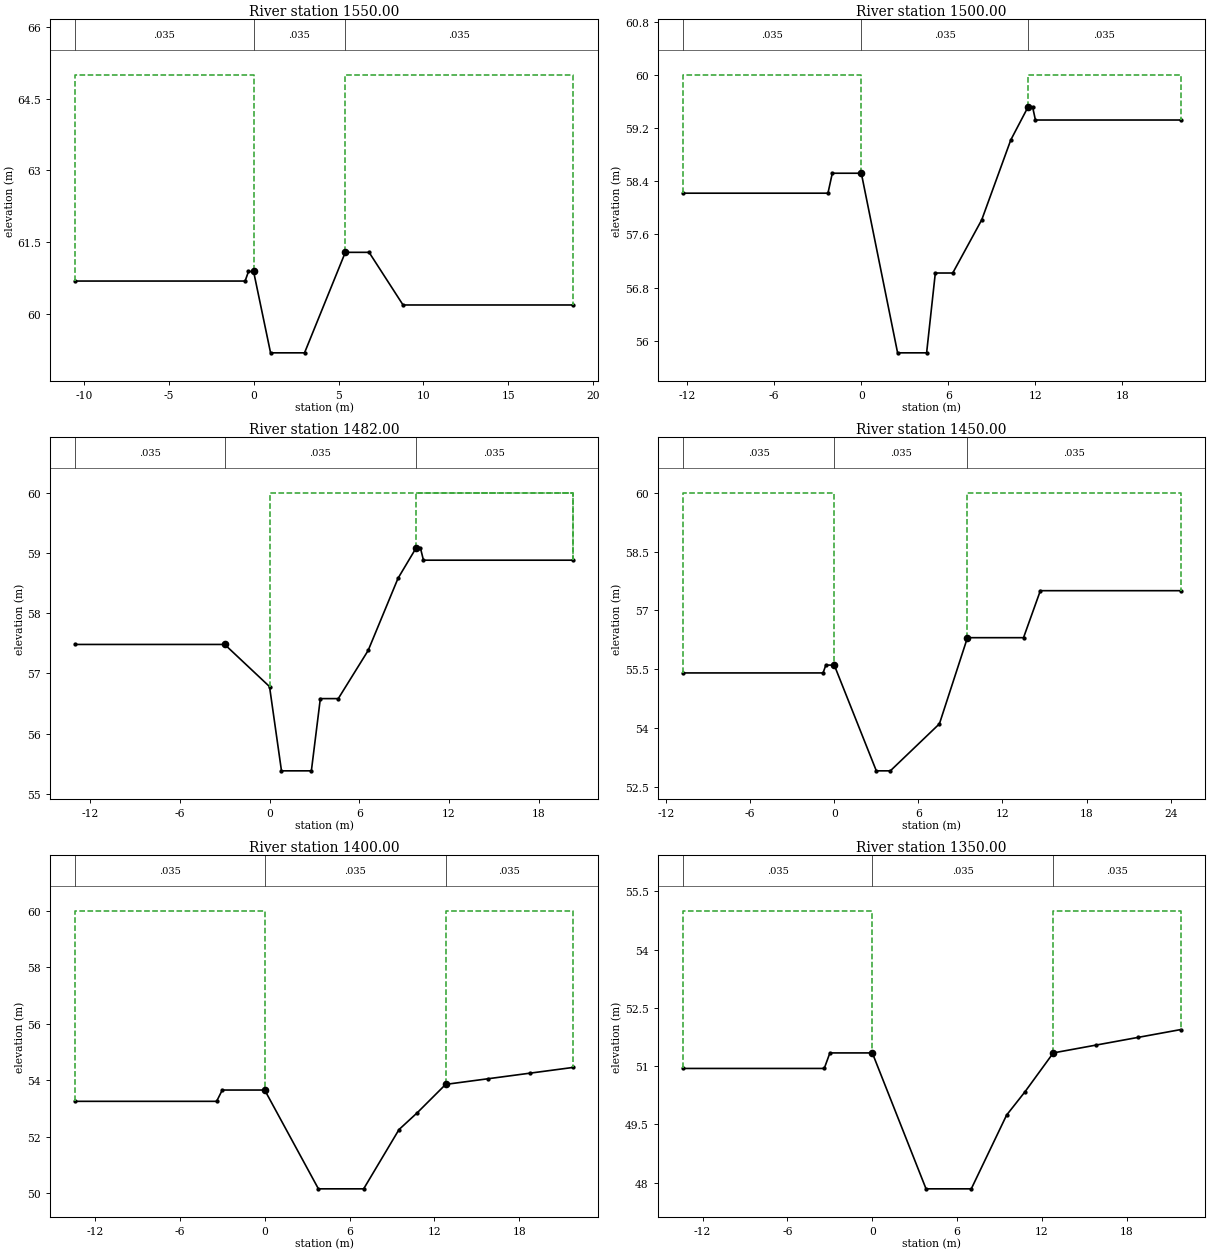
Type RM Length L Ch R = 1 ,1550.00 ,50,50,50
BEGIN DESCRIPTION:
32
END DESCRIPTION:
#Sta/Elev= 10
   -10.5   60.69     -.5   60.69     -.3   60.89       0   60.89       1   59.19
       3   59.19     5.4   61.29     6.8   61.29     8.8   60.19    18.8   60.19
#Mann= 3 , 0 , 0
   -10.5    .035       0       0    .035       0     5.4    .035       0
#XS Ineff= 2 , 0
               0      65     5.4              65
Permanent Ineff=
       F       F
#Block Obstruct= 2 , 0
                             5.4
Bank Sta=0,5.4
XS Rating Curve= 0
Exp/Cntr=.3,.1

Type RM Length L Ch R = 1 ,1500.00 ,18,18,18
BEGIN DESCRIPTION:
31
END DESCRIPTION:
#Sta/Elev= 14
   -12.3   58.22    -2.3   58.22      -2   58.52       0   58.52     2.5   55.82
     4.5   55.82     5.1   57.02     6.3   57.02     8.3   57.82    10.3   59.02
    11.5   59.52    11.8   59.52      12   59.32      22   59.32
#Mann= 3 , 0 , 0
   -12.3    .035       0       0    .035       0    11.5    .035       0
#XS Ineff= 2 , 0
               0      60    11.5              60
Permanent Ineff=
       F       F
#Block Obstruct= 2 , 0
                            11.5
Bank Sta=0,11.5
XS Rating Curve= 0
Exp/Cntr=.3,.1

Type RM Length L Ch R = 1 ,1482.00 ,32,32,32
BEGIN DESCRIPTION:
30.032
END DESCRIPTION:
#Sta/Elev= 13
     -13   57.48      -3   57.48       0   56.78      .8   55.38     2.8   55.38
     3.4   56.58     4.6   56.58     6.6   57.38     8.6   58.58     9.8   59.08
    10.1   59.08    10.3   58.88    20.3   58.88
#Mann= 3 , 0 , 0
     -13    .035       0      -3    .035       0     9.8    .035       0
#XS Ineff= 2 , 0
       0      -3      60     9.8       0      60
Permanent Ineff=
       F       F
#Block Obstruct= 2 , 0
                             9.8
Bank Sta=-3,9.8
XS Rating Curve= 0
Exp/Cntr=.3,.1

Type RM Length L Ch R = 1 ,1450.00 ,50,50,50
BEGIN DESCRIPTION:
30
END DESCRIPTION:
#Sta/Elev= 11
   -10.8    55.4     -.8    55.4     -.6    55.6       0    55.6       3    52.9
       4    52.9     7.5    54.1     9.5    56.3    13.5    56.3    14.7    57.5
    24.7    57.5
#Mann= 3 , 0 , 0
   -10.8    .035       0       0    .035       0     9.5    .035       0
#XS Ineff= 2 , 0
               0      60     9.5              60
Permanent Ineff=
       F       F
#Block Obstruct= 2 , 0
                             9.5
Bank Sta=0,9.5
XS Rating Curve= 0
Exp/Cntr=.3,.1

Type RM Length L Ch R = 1 ,1400.00 ,50,50,50
BEGIN DESCRIPTION:
29
END DESCRIPTION:
#Sta/Elev= 12
   -13.4   53.25    -3.4   53.25      -3   53.65       0   53.65     3.8   50.15
       7   50.15     9.5   52.25    10.8   52.85    12.8   53.85    15.8   54.05
    18.8   54.25    21.8   54.45
#Mann= 3 , 0 , 0
   -13.4    .035       0       0    .035       0    12.8    .035       0
#XS Ineff= 2 , 0
               0      60    12.8              60
Permanent Ineff=
       F       F
#Block Obstruct= 2 , 0
                            12.8
Bank Sta=0,12.8
XS Rating Curve= 0
Exp/Cntr=.3,.1

Type RM Length L Ch R = 1 ,1350.00 ,13,13,13
BEGIN DESCRIPTION:
28
END DESCRIPTION:
#Sta/Elev= 12
   -13.4   50.94    -3.4   50.94      -3   51.34       0   51.34     3.8   47.84
       7   47.84     9.5   49.74    10.8   50.34    12.8   51.34    15.8   51.54
    18.8   51.74    21.8   51.94
#Mann= 3 , 0 , 0
   -13.4    .035       0       0    .035       0    12.8    .035       0
#XS Ineff= 2 , 0
               0      55    12.8              55
Permanent Ineff=
       F       F
#Block Obstruct= 2 , 0
                            12.8
Bank Sta=0,12.8
XS Rating Curve= 0
Exp/Cntr=.3,.1

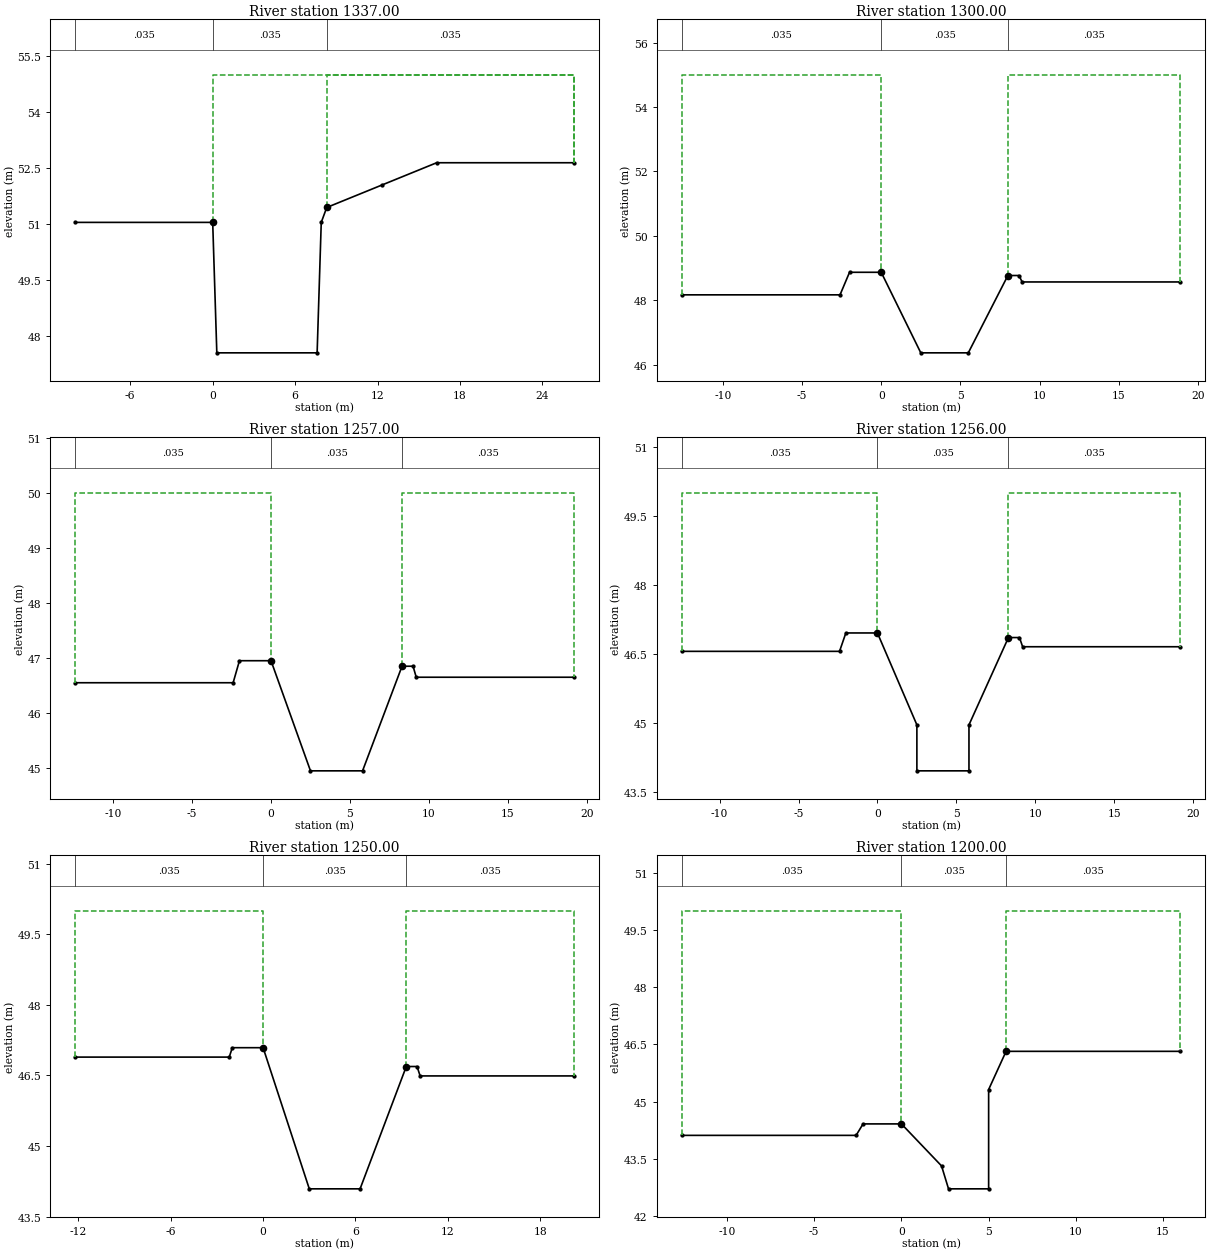
Type RM Length L Ch R = 1 ,1337.00 ,37,37,37
BEGIN DESCRIPTION:
27.037
END DESCRIPTION:
#Sta/Elev= 9
     -10   51.04       0   51.04      .3   47.54     7.6   47.54     7.9   51.04
     8.3   51.44    12.3   52.04    16.3   52.64    26.3   52.64
#Mann= 3 , 0 , 0
     -10    .035       0       0    .035       0     8.3    .035       0
#XS Ineff= 2 , 0
       0       0      55     8.3       0      55
Permanent Ineff=
       F       F
#Block Obstruct= 2 , 0
       0                     8.3       0
Bank Sta=0,8.3
XS Rating Curve= 0
Exp/Cntr=.3,.1

Type RM Length L Ch R = 1 ,1300.00 ,43,43,43
BEGIN DESCRIPTION:
27
END DESCRIPTION:
#Sta/Elev= 10
   -12.6   48.17    -2.6   48.17      -2   48.87       0   48.87     2.5   46.37
     5.5   46.37       8   48.77     8.7   48.77     8.9   48.57    18.9   48.57
#Mann= 3 , 0 , 0
   -12.6    .035       0       0    .035       0       8    .035       0
#XS Ineff= 2 , 0
               0      55       8              55
Permanent Ineff=
       F       F
#Block Obstruct= 2 , 0
                               8
Bank Sta=0,8
XS Rating Curve= 0
Exp/Cntr=.3,.1

Type RM Length L Ch R = 1 ,1257.00 ,1,1,1
BEGIN DESCRIPTION:
26.007
END DESCRIPTION:
#Sta/Elev= 10
   -12.4   46.55    -2.4   46.55      -2   46.95       0   46.95     2.5   44.95
     5.8   44.95     8.3   46.85       9   46.85     9.2   46.65    19.2   46.65
#Mann= 3 , 0 , 0
   -12.4    .035       0       0    .035       0     8.3    .035       0
#XS Ineff= 2 , 0
               0      50     8.3              50
Permanent Ineff=
       F       F
#Block Obstruct= 2 , 0
                             8.3
Bank Sta=0,8.3
XS Rating Curve= 0
Exp/Cntr=.3,.1

Type RM Length L Ch R = 1 ,1256.00 ,6,6,6
BEGIN DESCRIPTION:
26.006
END DESCRIPTION:
#Sta/Elev= 12
   -12.4   46.55    -2.4   46.55      -2   46.95       0   46.95     2.5   44.95
     2.5   43.95     5.8   43.95     5.8   44.95     8.3   46.85       9   46.85
     9.2   46.65    19.2   46.65
#Mann= 3 , 0 , 0
   -12.4    .035       0       0    .035       0     8.3    .035       0
#XS Ineff= 2 , 0
               0      50     8.3              50
Permanent Ineff=
       F       F
#Block Obstruct= 2 , 0
                             8.3
Bank Sta=0,8.3
XS Rating Curve= 0
Exp/Cntr=.3,.1

Type RM Length L Ch R = 1 ,1250.00 ,50,50,50
BEGIN DESCRIPTION:
26
END DESCRIPTION:
#Sta/Elev= 10
   -12.2   46.89    -2.2   46.89      -2   47.09       0   47.09       3   44.09
     6.3   44.09     9.3   46.69      10   46.69    10.2   46.49    20.2   46.49
#Mann= 3 , 0 , 0
   -12.2    .035       0       0    .035       0     9.3    .035       0
#XS Ineff= 2 , 0
               0      50     9.3              50
Permanent Ineff=
       F       F
#Block Obstruct= 2 , 0
                             9.3
Bank Sta=0,9.3
XS Rating Curve= 0
Exp/Cntr=.3,.1

Type RM Length L Ch R = 1 ,1200.00 ,33,33,33
BEGIN DESCRIPTION:
25
END DESCRIPTION:
#Sta/Elev= 10
   -12.6   44.12    -2.6   44.12    -2.2   44.42       0   44.42     2.3   43.32
     2.7   42.72       5   42.72       5   45.32       6   46.32      16   46.32
#Mann= 3 , 0 , 0
   -12.6    .035       0       0    .035       0       6    .035       0
#XS Ineff= 2 , 0
               0      50       6              50
Permanent Ineff=
       F       F
#Block Obstruct= 2 , 0
                               6
Bank Sta=0,6
XS Rating Curve= 0
Exp/Cntr=.3,.1

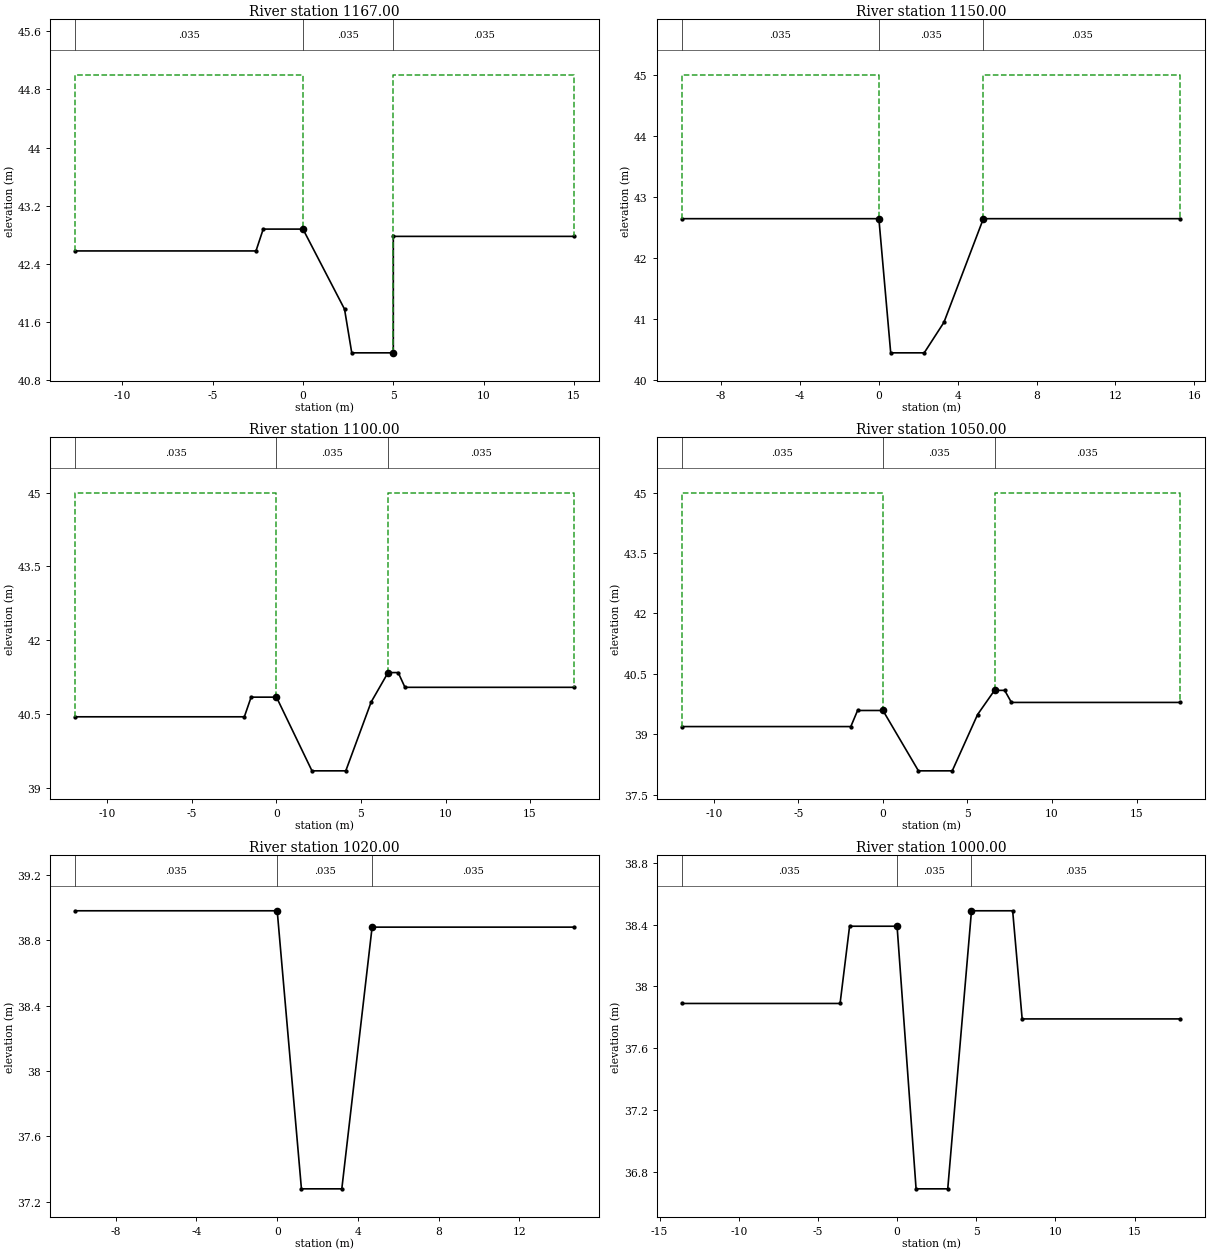
Type RM Length L Ch R = 1 ,1167.00 ,17,17,17
BEGIN DESCRIPTION:
24.017
END DESCRIPTION:
#Sta/Elev= 9
   -12.6   42.58    -2.6   42.58    -2.2   42.88       0   42.88     2.3   41.78
     2.7   41.18       5   41.18       5   42.78      15   42.78
#Mann= 3 , 0 , 0
   -12.6    .035       0       0    .035       0       5    .035       0
#XS Ineff= 2 , 0
               0      45       5              45
Permanent Ineff=
       F       F
#Block Obstruct= 2 , 0
                               5
Bank Sta=0,5
XS Rating Curve= 0
Exp/Cntr=.3,.1

Type RM Length L Ch R = 1 ,1150.00 ,50,50,50
BEGIN DESCRIPTION:
24
END DESCRIPTION:
#Sta/Elev= 7
     -10   42.64       0   42.64      .6   40.44     2.3   40.44     3.3   40.94
     5.3   42.64    15.3   42.64
#Mann= 3 , 0 , 0
     -10    .035       0       0    .035       0     5.3    .035       0
#XS Ineff= 2 , 0
               0      45     5.3              45
Permanent Ineff=
       F       F
#Block Obstruct= 2 , 0
                             5.3
Bank Sta=0,5.3
XS Rating Curve= 0
Exp/Cntr=.3,.1

Type RM Length L Ch R = 1 ,1100.00 ,50,50,50
BEGIN DESCRIPTION:
23
END DESCRIPTION:
#Sta/Elev= 11
   -11.9   40.44    -1.9   40.44    -1.5   40.84       0   40.84     2.1   39.34
     4.1   39.34     5.6   40.74     6.6   41.34     7.2   41.34     7.6   41.04
    17.6   41.04
#Mann= 3 , 0 , 0
   -11.9    .035       0       0    .035       0     6.6    .035       0
#XS Ineff= 2 , 0
               0      45     6.6              45
Permanent Ineff=
       F       F
#Block Obstruct= 2 , 0
                             6.6
Bank Sta=0,6.6
XS Rating Curve= 0
Exp/Cntr=.3,.1

Type RM Length L Ch R = 1 ,1050.00 ,30,30,30
BEGIN DESCRIPTION:
22
END DESCRIPTION:
#Sta/Elev= 11
   -11.9   39.19    -1.9   39.19    -1.5   39.59       0   39.59     2.1   38.09
     4.1   38.09     5.6   39.49     6.6   40.09     7.2   40.09     7.6   39.79
    17.6   39.79
#Mann= 3 , 0 , 0
   -11.9    .035       0       0    .035       0     6.6    .035       0
#XS Ineff= 2 , 0
               0      45     6.6              45
Permanent Ineff=
       F       F
#Block Obstruct= 2 , 0
                             6.6
Bank Sta=0,6.6
XS Rating Curve= 0
Exp/Cntr=.3,.1

Type RM Length L Ch R = 1 ,1020.00 ,20,20,20
BEGIN DESCRIPTION:
21.02
END DESCRIPTION:
#Sta/Elev= 6
     -10   38.98       0   38.98     1.2   37.28     3.2   37.28     4.7   38.88
    14.7   38.88
#Mann= 3 , 0 , 0
     -10    .035       0       0    .035       0     4.7    .035       0
#XS Ineff= 2 , 0
               0      45     4.7              45
Permanent Ineff=
       F       F
#Block Obstruct= 2 , 0
                             4.7
Bank Sta=0,4.7
XS Rating Curve= 0
Exp/Cntr=.3,.1

Type RM Length L Ch R = 1 ,1000.00 ,41,41,41
BEGIN DESCRIPTION:
21
END DESCRIPTION:
#Sta/Elev= 10
   -13.6   37.89    -3.6   37.89      -3   38.39       0   38.39     1.2   36.69
     3.2   36.69     4.7   38.49     7.3   38.49     7.9   37.79    17.9   37.79
#Mann= 3 , 0 , 0
   -13.6    .035       0       0    .035       0     4.7    .035       0
#XS Ineff= 2 , 0
               0      45     4.7              45
Permanent Ineff=
       F       F
#Block Obstruct= 2 , 0
                             4.7
Bank Sta=0,4.7
XS Rating Curve= 0
Exp/Cntr=.3,.1

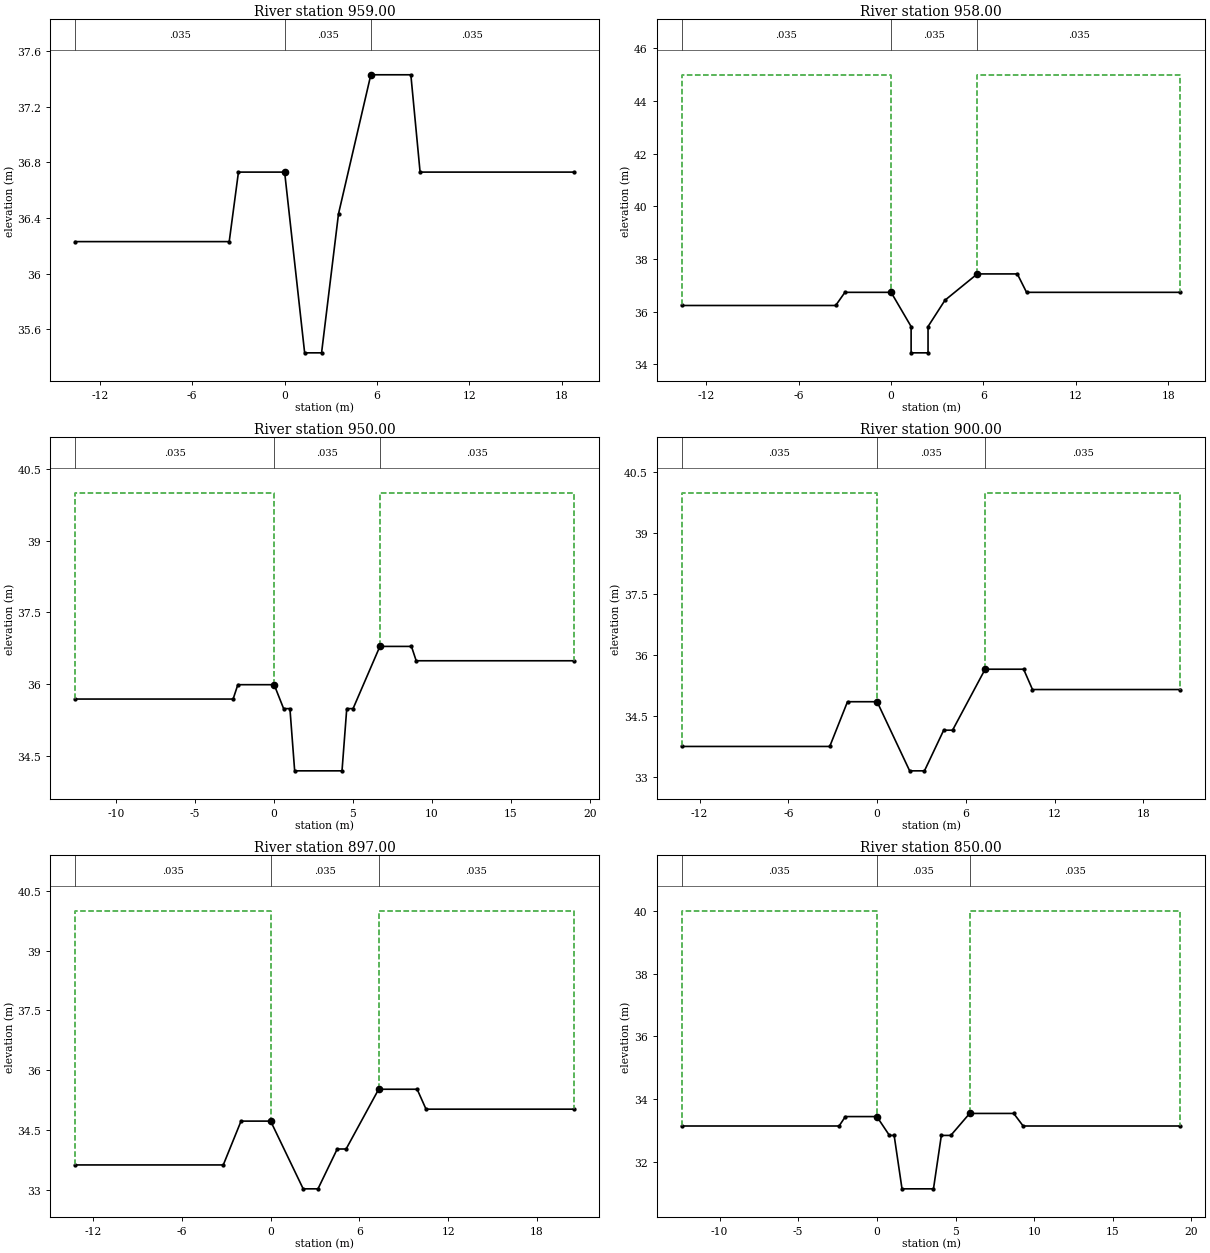
Type RM Length L Ch R = 1 ,959.00  ,1,1,1
BEGIN DESCRIPTION:
20.009
END DESCRIPTION:
#Sta/Elev= 11
   -13.6   36.23    -3.6   36.23      -3   36.73       0   36.73     1.3   35.43
     2.4   35.43     3.5   36.43     5.6   37.43     8.2   37.43     8.8   36.73
    18.8   36.73
#Mann= 3 , 0 , 0
   -13.6    .035       0       0    .035       0     5.6    .035       0
#XS Ineff= 2 , 0
               0      45     5.6              45
Permanent Ineff=
       F       F
#Block Obstruct= 2 , 0
                             5.6
Bank Sta=0,5.6
XS Rating Curve= 0
Exp/Cntr=.3,.1

Type RM Length L Ch R = 1 ,958.00  ,8,8,8
BEGIN DESCRIPTION:
20.008
END DESCRIPTION:
#Sta/Elev= 13
   -13.6   36.23    -3.6   36.23      -3   36.73       0   36.73     1.3   35.43
     1.3   34.43     2.4   34.43     2.4   35.43     3.5   36.43     5.6   37.43
     8.2   37.43     8.8   36.73    18.8   36.73
#Mann= 3 , 0 , 0
   -13.6    .035       0       0    .035       0     5.6    .035       0
#XS Ineff= 2 , 0
               0      45     5.6              45
Permanent Ineff=
       F       F
#Block Obstruct= 2 , 0
                             5.6
Bank Sta=0,5.6
XS Rating Curve= 0
Exp/Cntr=.3,.1

Type RM Length L Ch R = 1 ,950.00  ,50,50,50
BEGIN DESCRIPTION:
20
END DESCRIPTION:
#Sta/Elev= 14
   -12.6   35.69    -2.6   35.69    -2.3   35.99       0   35.99      .6   35.49
       1   35.49     1.3   34.19     4.3   34.19     4.6   35.49       5   35.49
     6.7   36.79     8.7   36.79       9   36.49      19   36.49
#Mann= 3 , 0 , 0
   -12.6    .035       0       0    .035       0     6.7    .035       0
#XS Ineff= 2 , 0
               0      40     6.7              40
Permanent Ineff=
       F       F
#Block Obstruct= 2 , 0
                             6.7
Bank Sta=0,6.7
XS Rating Curve= 0
Exp/Cntr=.3,.1

Type RM Length L Ch R = 1 ,900.00  ,3,3,3
BEGIN DESCRIPTION:
19
END DESCRIPTION:
#Sta/Elev= 12
   -13.2   33.76    -3.2   33.76      -2   34.86       0   34.86     2.2   33.16
     3.2   33.16     4.5   34.16     5.1   34.16     7.3   35.66     9.9   35.66
    10.5   35.16    20.5   35.16
#Mann= 3 , 0 , 0
   -13.2    .035       0       0    .035       0     7.3    .035       0
#XS Ineff= 2 , 0
               0      40     7.3              40
Permanent Ineff=
       F       F
#Block Obstruct= 2 , 0
                             7.3
Bank Sta=0,7.3
XS Rating Curve= 0
Exp/Cntr=.3,.1

Type RM Length L Ch R = 1 ,897.00  ,47,47,47
BEGIN DESCRIPTION:
18.047
END DESCRIPTION:
#Sta/Elev= 12
   -13.2   33.62    -3.2   33.62      -2   34.72       0   34.72     2.2   33.02
     3.2   33.02     4.5   34.02     5.1   34.02     7.3   35.52     9.9   35.52
    10.5   35.02    20.5   35.02
#Mann= 3 , 0 , 0
   -13.2    .035       0       0    .035       0     7.3    .035       0
#XS Ineff= 2 , 0
               0      40     7.3              40
Permanent Ineff=
       F       F
#Block Obstruct= 2 , 0
                             7.3
Bank Sta=0,7.3
XS Rating Curve= 0
Exp/Cntr=.3,.1

Type RM Length L Ch R = 1 ,850.00  ,46,46,46
BEGIN DESCRIPTION:
18
END DESCRIPTION:
#Sta/Elev= 14
   -12.4   33.15    -2.4   33.15      -2   33.45       0   33.45      .8   32.85
     1.1   32.85     1.6   31.15     3.6   31.15     4.1   32.85     4.7   32.85
     5.9   33.55     8.7   33.55     9.3   33.15    19.3   33.15
#Mann= 3 , 0 , 0
   -12.4    .035       0       0    .035       0     5.9    .035       0
#XS Ineff= 2 , 0
               0      40     5.9              40
Permanent Ineff=
       F       F
#Block Obstruct= 2 , 0
                             5.9
Bank Sta=0,5.9
XS Rating Curve= 0
Exp/Cntr=.3,.1

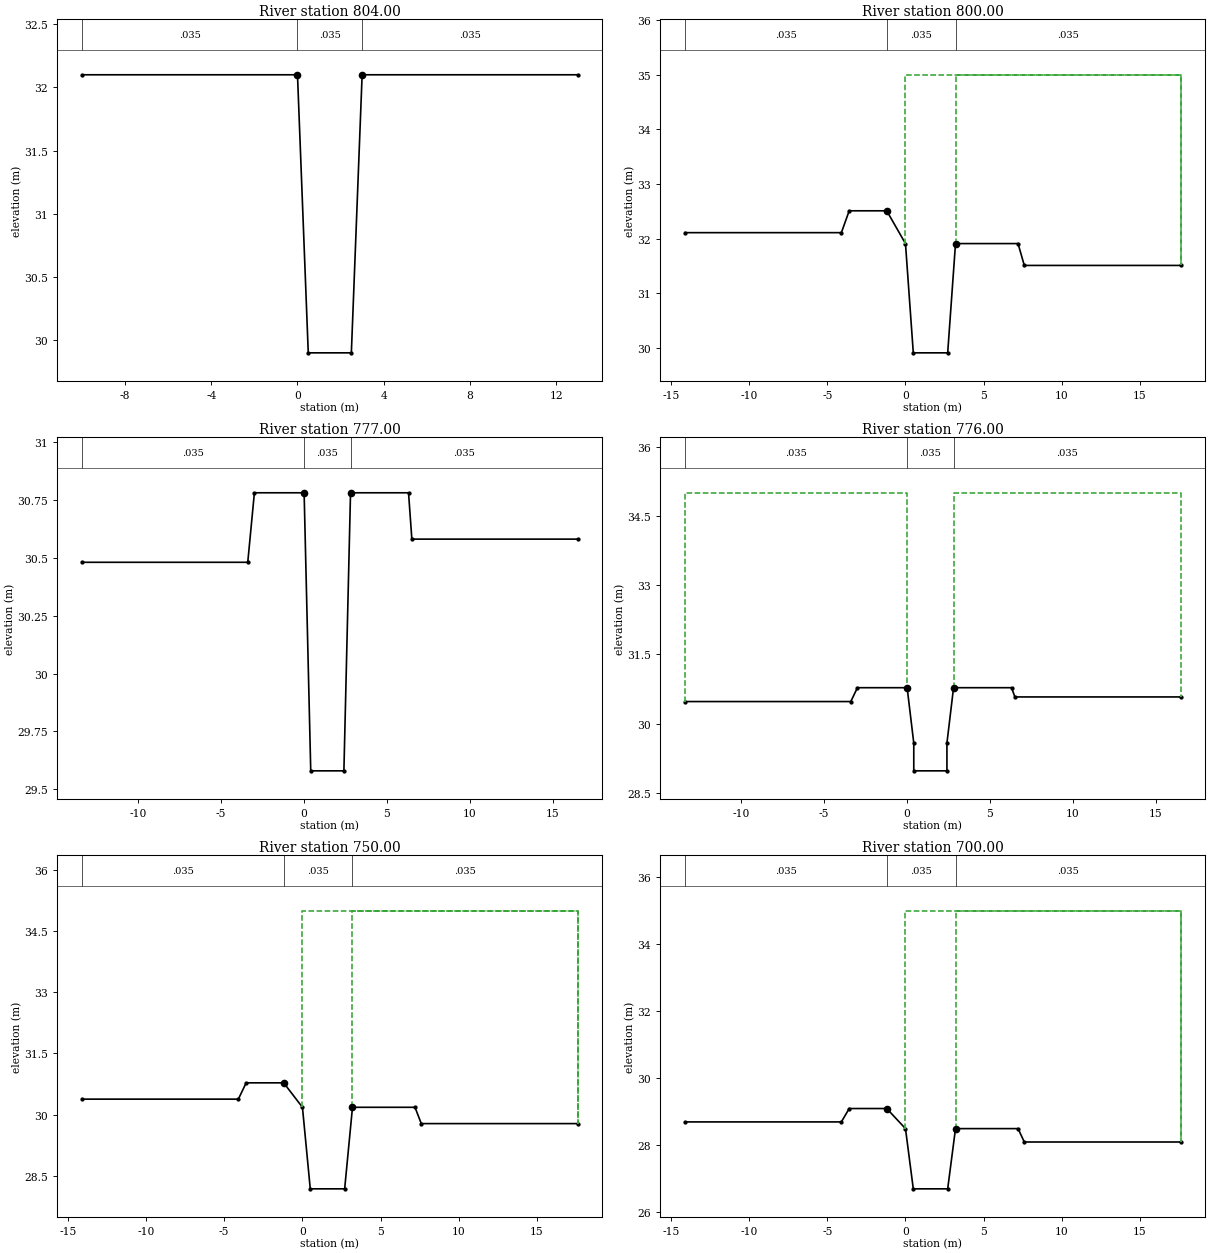
Type RM Length L Ch R = 1 ,804.00  ,4,4,4
BEGIN DESCRIPTION:
17.004
END DESCRIPTION:
#Sta/Elev= 6
     -10    32.1       0    32.1      .5    29.9     2.5    29.9       3    32.1
      13    32.1
#Mann= 3 , 0 , 0
     -10    .035       0       0    .035       0       3    .035       0
#XS Ineff= 2 , 0
               0      40       3              40
Permanent Ineff=
       F       F
#Block Obstruct= 2 , 0
                               3
Bank Sta=0,3
XS Rating Curve= 0
Exp/Cntr=.3,.1

Type RM Length L Ch R = 1 ,800.00  ,23,23,23
BEGIN DESCRIPTION:
17
END DESCRIPTION:
#Sta/Elev= 11
   -14.1   32.11    -4.1   32.11    -3.6   32.51    -1.2   32.51       0   31.91
      .5   29.91     2.7   29.91     3.2   31.91     7.2   31.91     7.6   31.51
    17.6   31.51
#Mann= 3 , 0 , 0
   -14.1    .035       0    -1.2    .035       0     3.2    .035       0
#XS Ineff= 2 , 0
       0    -1.2      35     3.2       0      35
Permanent Ineff=
       F       F
#Block Obstruct= 2 , 0
       0    -1.2             3.2       0
Bank Sta=-1.2,3.2
XS Rating Curve= 0
Exp/Cntr=.3,.1

Type RM Length L Ch R = 1 ,777.00  ,1,1,1
BEGIN DESCRIPTION:
16.027
END DESCRIPTION:
#Sta/Elev= 10
   -13.4   30.48    -3.4   30.48      -3   30.78       0   30.78      .4   29.58
     2.4   29.58     2.8   30.78     6.3   30.78     6.5   30.58    16.5   30.58
#Mann= 3 , 0 , 0
   -13.4    .035       0       0    .035       0     2.8    .035       0
#XS Ineff= 2 , 0
               0      35     2.8              35
Permanent Ineff=
       F       F
#Block Obstruct= 2 , 0
                             2.8
Bank Sta=0,2.8
XS Rating Curve= 0
Exp/Cntr=.3,.1

Type RM Length L Ch R = 1 ,776.00  ,26,26,26
BEGIN DESCRIPTION:
16.026
END DESCRIPTION:
#Sta/Elev= 12
   -13.4   30.48    -3.4   30.48      -3   30.78       0   30.78      .4   29.58
      .4   28.98     2.4   28.98     2.4   29.58     2.8   30.78     6.3   30.78
     6.5   30.58    16.5   30.58
#Mann= 3 , 0 , 0
   -13.4    .035       0       0    .035       0     2.8    .035       0
#XS Ineff= 2 , 0
               0      35     2.8              35
Permanent Ineff=
       F       F
#Block Obstruct= 2 , 0
                             2.8
Bank Sta=0,2.8
XS Rating Curve= 0
Exp/Cntr=.3,.1

Type RM Length L Ch R = 1 ,750.00  ,50,50,50
BEGIN DESCRIPTION:
16
END DESCRIPTION:
#Sta/Elev= 11
   -14.1   30.38    -4.1   30.38    -3.6   30.78    -1.2   30.78       0   30.18
      .5   28.18     2.7   28.18     3.2   30.18     7.2   30.18     7.6   29.78
    17.6   29.78
#Mann= 3 , 0 , 0
   -14.1    .035       0    -1.2    .035       0     3.2    .035       0
#XS Ineff= 2 , 0
       0    -1.2      35     3.2       0      35
Permanent Ineff=
       F       F
#Block Obstruct= 2 , 0
                             3.2
Bank Sta=-1.2,3.2
XS Rating Curve= 0
Exp/Cntr=.3,.1

Type RM Length L Ch R = 1 ,700.00  ,50,50,50
BEGIN DESCRIPTION:
15
END DESCRIPTION:
#Sta/Elev= 11
   -14.1   28.69    -4.1   28.69    -3.6   29.09    -1.2   29.09       0   28.49
      .5   26.69     2.7   26.69     3.2   28.49     7.2   28.49     7.6   28.09
    17.6   28.09
#Mann= 3 , 0 , 0
   -14.1    .035       0    -1.2    .035       0     3.2    .035       0
#XS Ineff= 2 , 0
       0    -1.2      35     3.2       0      35
Permanent Ineff=
       F       F
#Block Obstruct= 2 , 0
                             3.2
Bank Sta=-1.2,3.2
XS Rating Curve= 0
Exp/Cntr=.3,.1

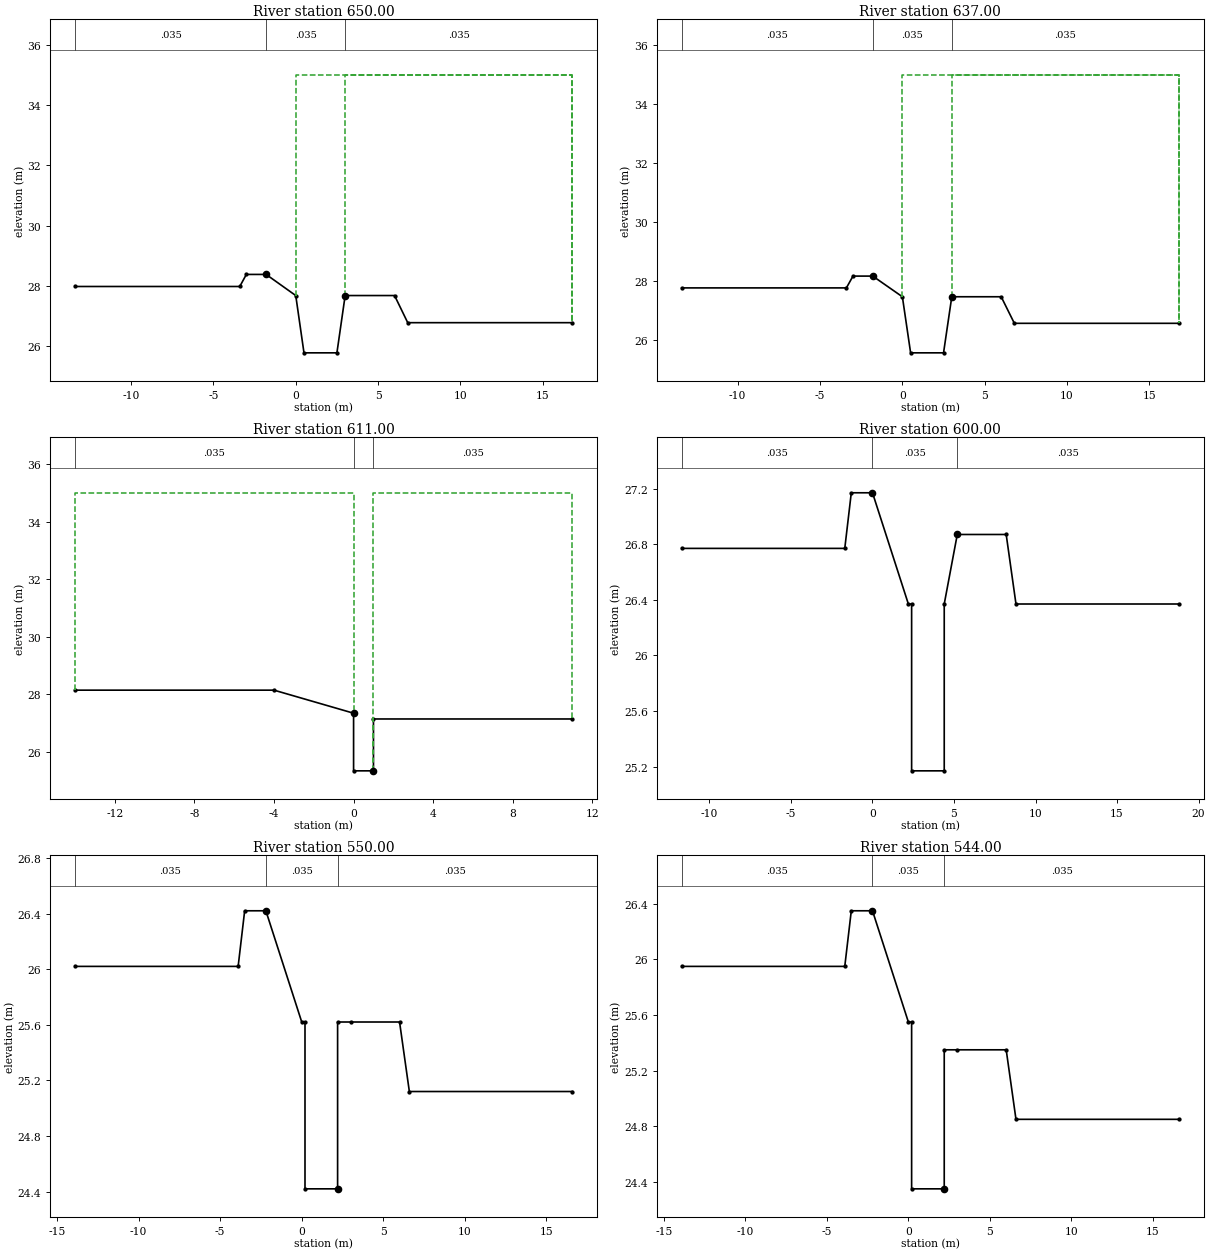
Type RM Length L Ch R = 1 ,650.00  ,13,13,13
BEGIN DESCRIPTION:
14
END DESCRIPTION:
#Sta/Elev= 11
   -13.4   27.98    -3.4   27.98      -3   28.38    -1.8   28.38       0   27.68
      .5   25.78     2.5   25.78       3   27.68       6   27.68     6.8   26.78
    16.8   26.78
#Mann= 3 , 0 , 0
   -13.4    .035       0    -1.8    .035       0       3    .035       0
#XS Ineff= 2 , 0
       0    -1.8      35       3       0      35
Permanent Ineff=
       F       F
#Block Obstruct= 2 , 0
                               3
Bank Sta=-1.8,3
XS Rating Curve= 0
Exp/Cntr=.3,.1

Type RM Length L Ch R = 1 ,637.00  ,26,26,26
BEGIN DESCRIPTION:
13.037
END DESCRIPTION:
#Sta/Elev= 11
   -13.4   27.78    -3.4   27.78      -3   28.18    -1.8   28.18       0   27.48
      .5   25.58     2.5   25.58       3   27.48       6   27.48     6.8   26.58
    16.8   26.58
#Mann= 3 , 0 , 0
   -13.4    .035       0    -1.8    .035       0       3    .035       0
#XS Ineff= 2 , 0
       0    -1.8      35       3       0      35
Permanent Ineff=
       F       F
#Block Obstruct= 2 , 0
                               3
Bank Sta=-1.8,3
XS Rating Curve= 0
Exp/Cntr=.3,.1

Type RM Length L Ch R = 1 ,611.00  ,11,11,11
BEGIN DESCRIPTION:
13.011
END DESCRIPTION:
#Sta/Elev= 7
     -14   28.15      -4   28.15       0   27.35       0   25.35       1   25.35
       1   27.15      11   27.15
#Mann= 3 , 0 , 0
     -14    .035       0       0    .035       0       1    .035       0
#XS Ineff= 2 , 0
               0      35       1              35
Permanent Ineff=
       F       F
#Block Obstruct= 2 , 0
                               1
Bank Sta=0,1
XS Rating Curve= 0
Exp/Cntr=.3,.1

Type RM Length L Ch R = 1 ,600.00  ,50,50,50
BEGIN DESCRIPTION:
13
END DESCRIPTION:
#Sta/Elev= 13
   -11.7   26.77    -1.7   26.77    -1.3   27.17       0   27.17     2.2   26.37
     2.4   26.37     2.4   25.17     4.4   25.17     4.4   26.37     5.2   26.87
     8.2   26.87     8.8   26.37    18.8   26.37
#Mann= 3 , 0 , 0
   -11.7    .035       0       0    .035       0     5.2    .035       0
#XS Ineff= 2 , 0
               0      35     5.2              35
Permanent Ineff=
       F       F
#Block Obstruct= 2 , 0
                             5.2
Bank Sta=0,5.2
XS Rating Curve= 0
Exp/Cntr=.3,.1

Type RM Length L Ch R = 1 ,550.00  ,6,6,6
BEGIN DESCRIPTION:
12
END DESCRIPTION:
#Sta/Elev= 13
   -13.9   26.02    -3.9   26.02    -3.5   26.42    -2.2   26.42       0   25.62
      .2   25.62      .2   24.42     2.2   24.42     2.2   25.62       3   25.62
       6   25.62     6.6   25.12    16.6   25.12
#Mann= 3 , 0 , 0
   -13.9    .035       0    -2.2    .035       0     2.2    .035       0
#XS Ineff= 2 , 0
       0    -2.2      35     2.2       0      35
Permanent Ineff=
       F       F
#Block Obstruct= 2 , 0
                             2.2
Bank Sta=-2.2,2.2
XS Rating Curve= 0
Exp/Cntr=.3,.1

Type RM Length L Ch R = 1 ,544.00  ,1,1,1
BEGIN DESCRIPTION:
11.044
END DESCRIPTION:
#Sta/Elev= 13
   -13.9   25.95    -3.9   25.95    -3.5   26.35    -2.2   26.35       0   25.55
      .2   25.55      .2   24.35     2.2   24.35     2.2   25.35       3   25.35
       6   25.35     6.6   24.85    16.6   24.85
#Mann= 3 , 0 , 0
   -13.9    .035       0    -2.2    .035       0     2.2    .035       0
#XS Ineff= 2 , 0
       0    -2.2      35     2.2       0      35
Permanent Ineff=
       F       F
#Block Obstruct= 2 , 0
                             2.2
Bank Sta=-2.2,2.2
XS Rating Curve= 0
Exp/Cntr=.3,.1