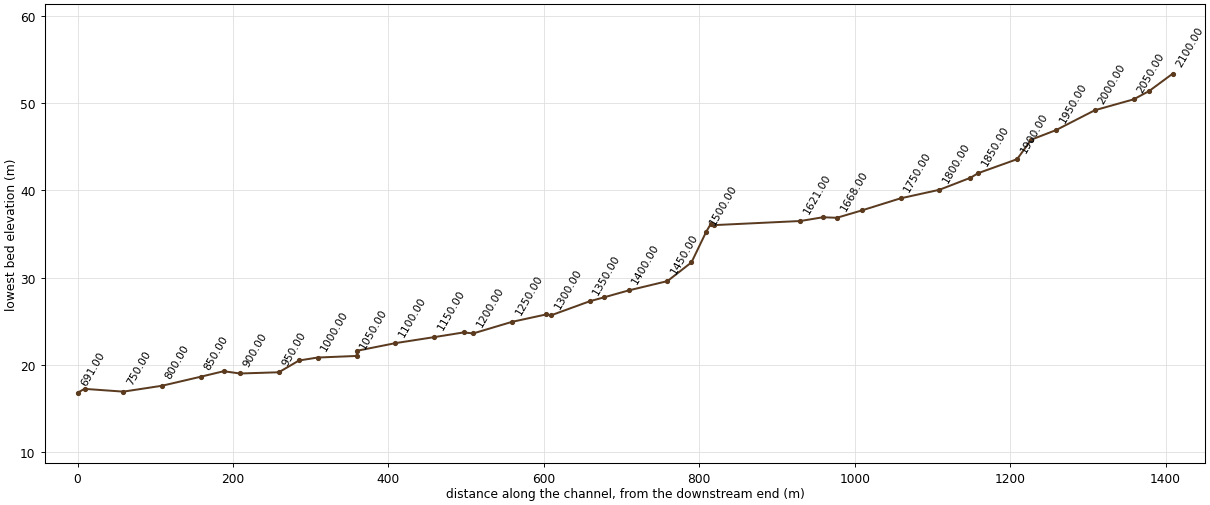
--- TGC.prj (project) ---

Proj Title=TONGGOL
Current Plan=p01
Default Exp/Contr=.3,.1
SI Units
Geom File=g01
Flow File=f01
Plan File=p01
Y Axis Title=Elevation
X Axis Title(PF)=Main Channel Distance
X Axis Title(XS)=Station
BEGIN DESCRIPTION:
           BACK WATER COMPUTATION
      APPLICATION OF HEC-2 BY Samju Construction Engineering
      tonggol-ch: 10,20,30,50,80 yr
END DESCRIPTION:
DSS Export Rating Curves= 0
DSS Export Rating Curve Sorted= 0
DSS Export Volume Flow Curves= 0
DXF OffsetX= 0
DXF OffsetY= 0
DXF ScaleX= 1
DXF ScaleY= 10

--- TGC.p01 (plan) ---

Plan Title=Imported Plan 01
Version=Version 3.0.1  Mar 2001
Short Identifier=Imported Pla
Geom File=g01
Flow File=f01
Subcritical Flow
K Sum by GR= 0
Std Step Tol= 0.003
Critical Tol= 0.003
Num of Std Step Trials= 20
Max Error Tol= 0.1
Flow Tol Ratio= 0.001
Split Flow NTrial= 30
Split Flow Tol= 0.02
Split Flow Ratio= 0.02
Log Output Level= 0
Friction Slope Method= 1
Unsteady Friction Slope Method= 2
Parabolic Critical Depth
Global Vel Dist= 0 , 0 , 0
Global Log Level= 0
CheckData=True
Encroach Param=-1 ,0,0, 0
Computation Interval=1HOUR
Output Interval=1HOUR
Run HTab= 0
Run UNet= 0
Run PostProcess= 0
UNET Theta= 1
UNET ZTol= 0.02
UNET ZSATol= 0.1
UNET MxIter= 20
UNET MaxInSteps= 20
UNET DtIC= 0
UNET DtMin= 0
UNET MaxCRTS= 20
UNET WFStab= 2
UNET SFStab= 1
UNET WFX= 1
UNET SFX= 1
UNET Convert EG Bridges=-1
UNET Use Existing IB Tables=-1
Instantaneous Interval=1HOUR
Write IC File= 0
Write Velocity= 0
Write Detailed= 0

--- TGC.f01 (steady flow) ---

Flow Title=Imported Flow 01
Version=Version 3.0.1  Mar 2001
Number of Profiles= 5
Profile Names=10YR,20YR,30YR,50YR,80YR
River Rch & RM=RIVER-1,Reach-1         ,2100.00
   10.26    11.3   11.91   12.67   13.38
River Rch & RM=RIVER-1,Reach-1         ,1000.00
   15.31   16.87   17.79   18.94      20
Boundary for River Rch & Prof#=RIVER-1,Reach-1         , 1
Up Type= 0
Dn Type= 3
Dn Slope=.022
Boundary for River Rch & Prof#=RIVER-1,Reach-1         , 2
Up Type= 0
Dn Type= 3
Dn Slope=.022
Boundary for River Rch & Prof#=RIVER-1,Reach-1         , 3
Up Type= 0
Dn Type= 3
Dn Slope=.022
Boundary for River Rch & Prof#=RIVER-1,Reach-1         , 4
Up Type= 0
Dn Type= 3
Dn Slope=.022
Boundary for River Rch & Prof#=RIVER-1,Reach-1         , 5
Up Type= 0
Dn Type= 3
Dn Slope=.022
DSS Import GetInterval= 0
DSS Import GetPeak= 0
DSS Import FillOption= 0

--- TGC.g01 (geometry) ---

Geom Title=Imported Geom 01
Version=Version 3.0.1  Mar 2001

River Reach=RIVER-1         ,Reach-1
Reach XY= 2
              .5             .95              .5             .05

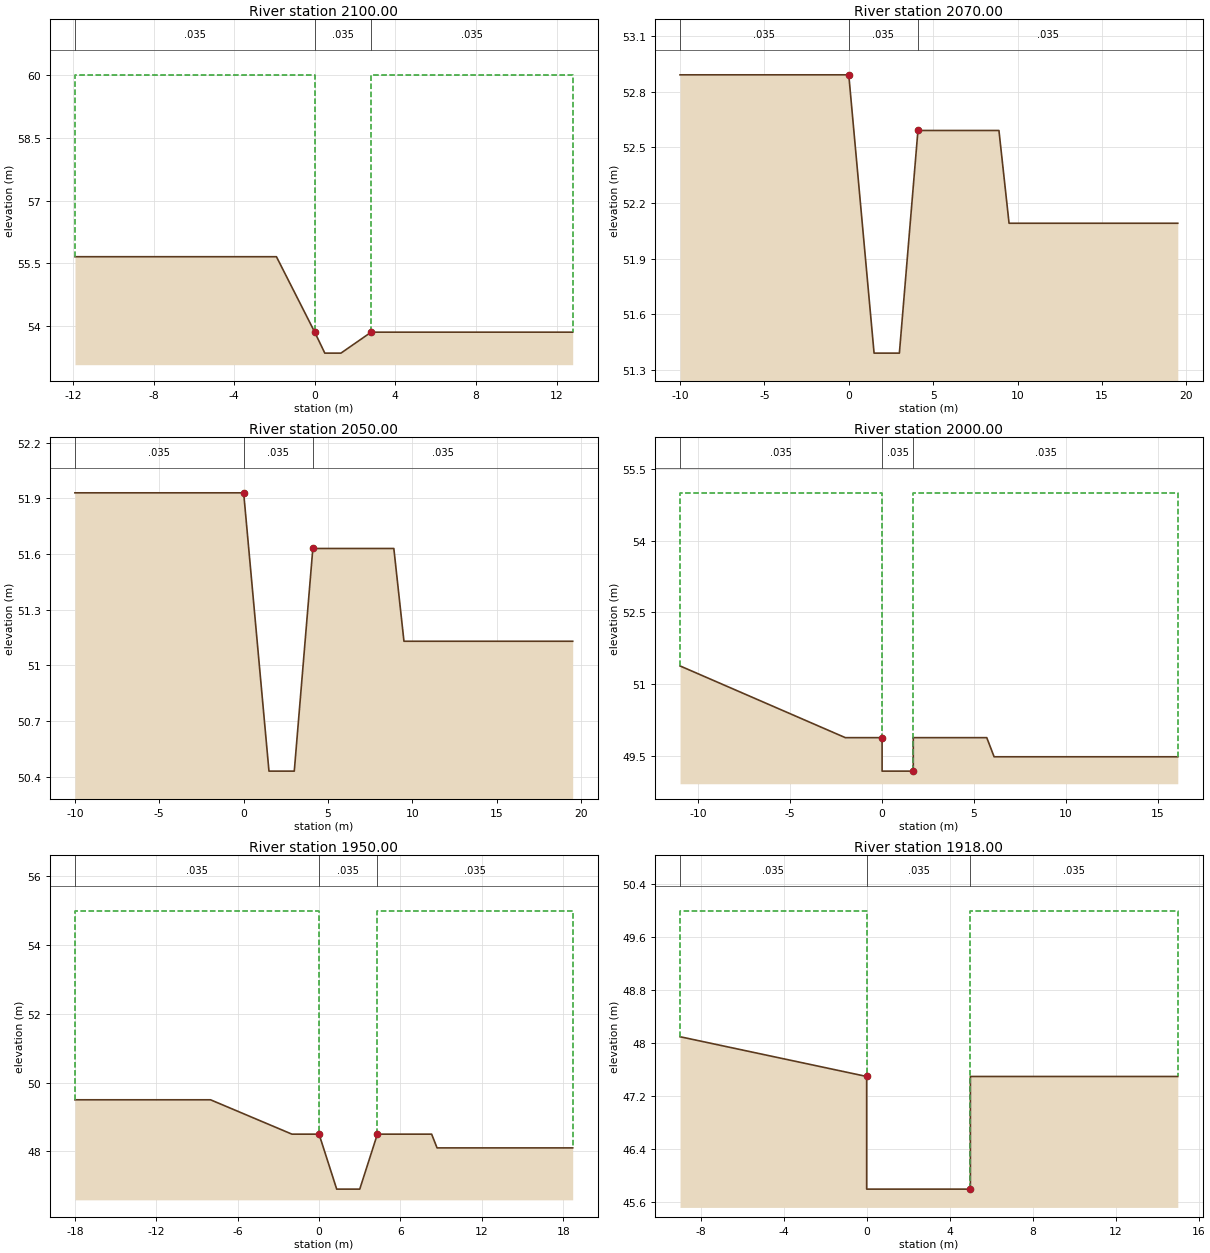
Type RM Length L Ch R = 1 ,2100.00 ,30,30,30
BEGIN DESCRIPTION:
42
END DESCRIPTION:
#Sta/Elev= 7
   -11.9   55.66    -1.9   55.66       0   53.86      .5   53.36     1.3   53.36
     2.8   53.86    12.8   53.86
#Mann= 3 , 0 , 0
   -11.9    .035       0       0    .035       0     2.8    .035       0
#XS Ineff= 2 , 0
               0      60     2.8              60
Permanent Ineff=
       F       F
#Block Obstruct= 2 , 0
                             2.8
Bank Sta=0,2.8
XS Rating Curve= 0
Exp/Cntr=.3,.1

Type RM Length L Ch R = 1 ,2070.00 ,20,20,20
BEGIN DESCRIPTION:
41.02
END DESCRIPTION:
#Sta/Elev= 8
     -10   52.89       0   52.89     1.5   51.39       3   51.39     4.1   52.59
     8.9   52.59     9.5   52.09    19.5   52.09
#Mann= 3 , 0 , 0
     -10    .035       0       0    .035       0     4.1    .035       0
#XS Ineff= 2 , 0
               0      60     4.1              60
Permanent Ineff=
       F       F
#Block Obstruct= 2 , 0
                             4.1
Bank Sta=0,4.1
XS Rating Curve= 0
Exp/Cntr=.3,.1

Type RM Length L Ch R = 1 ,2050.00 ,50,50,50
BEGIN DESCRIPTION:
41
END DESCRIPTION:
#Sta/Elev= 8
     -10   51.93       0   51.93     1.5   50.43       3   50.43     4.1   51.63
     8.9   51.63     9.5   51.13    19.5   51.13
#Mann= 3 , 0 , 0
     -10    .035       0       0    .035       0     4.1    .035       0
#XS Ineff= 2 , 0
               0      60     4.1              60
Permanent Ineff=
       F       F
#Block Obstruct= 2 , 0
                             4.1
Bank Sta=0,4.1
XS Rating Curve= 0
Exp/Cntr=.3,.1

Type RM Length L Ch R = 1 ,2000.00 ,50,50,50
BEGIN DESCRIPTION:
40
END DESCRIPTION:
#Sta/Elev= 11
     -11   51.38      -8   50.88      -5   50.38      -2   49.88       0   49.88
       0   49.18     1.7   49.18     1.7   49.88     5.7   49.88     6.1   49.48
    16.1   49.48
#Mann= 3 , 0 , 0
     -11    .035       0       0    .035       0     1.7    .035       0
#XS Ineff= 2 , 0
               0      55     1.7              55
Permanent Ineff=
       F       F
#Block Obstruct= 2 , 0
                             1.7
Bank Sta=0,1.7
XS Rating Curve= 0
Exp/Cntr=.3,.1

Type RM Length L Ch R = 1 ,1950.00 ,32,32,32
BEGIN DESCRIPTION:
39
END DESCRIPTION:
#Sta/Elev= 11
     -18    49.5      -8    49.5      -5      49      -2    48.5       0    48.5
     1.3    46.9       3    46.9     4.3    48.5     8.3    48.5     8.7    48.1
    18.7    48.1
#Mann= 3 , 0 , 0
     -18    .035       0       0    .035       0     4.3    .035       0
#XS Ineff= 2 , 0
               0      55     4.3              55
Permanent Ineff=
       F       F
#Block Obstruct= 2 , 0
                             4.3
Bank Sta=0,4.3
XS Rating Curve= 0
Exp/Cntr=.3,.1

Type RM Length L Ch R = 1 ,1918.00 ,18,18,18
BEGIN DESCRIPTION:
38.018
END DESCRIPTION:
#Sta/Elev= 8
      -9    48.1      -6    47.9      -3    47.7       0    47.5       0    45.8
       5    45.8       5    47.5      15    47.5
#Mann= 3 , 0 , 0
      -9    .035       0       0    .035       0       5    .035       0
#XS Ineff= 2 , 0
               0      50       5              50
Permanent Ineff=
       F       F
#Block Obstruct= 2 , 0
                               5
Bank Sta=0,5
XS Rating Curve= 0
Exp/Cntr=.3,.1

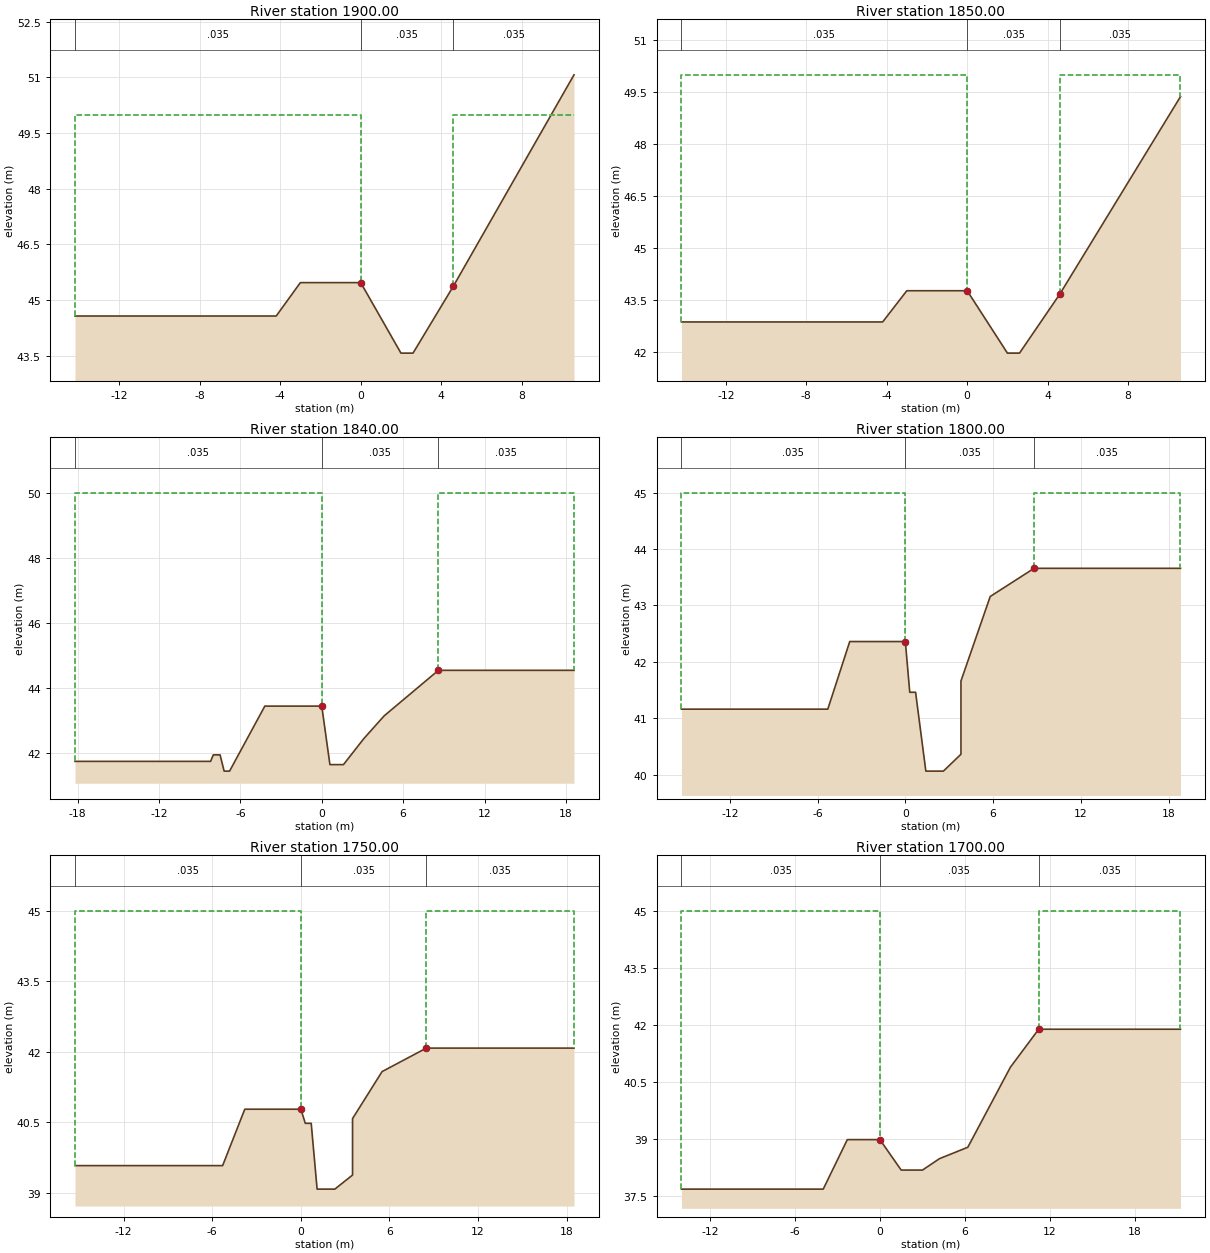
Type RM Length L Ch R = 1 ,1900.00 ,50,50,50
BEGIN DESCRIPTION:
38
END DESCRIPTION:
#Sta/Elev= 10
   -14.2   44.57    -4.2   44.57      -3   45.47       0   45.47       2   43.57
     2.6   43.57     4.6   45.37     6.6   47.27     8.6   49.17    10.6   51.07
#Mann= 3 , 0 , 0
   -14.2    .035       0       0    .035       0     4.6    .035       0
#XS Ineff= 2 , 0
               0      50     4.6              50
Permanent Ineff=
       F       F
#Block Obstruct= 2 , 0
                             4.6
Bank Sta=0,4.6
XS Rating Curve= 0
Exp/Cntr=.3,.1

Type RM Length L Ch R = 1 ,1850.00 ,10,10,10
BEGIN DESCRIPTION:
37
END DESCRIPTION:
#Sta/Elev= 10
   -14.2   42.87    -4.2   42.87      -3   43.77       0   43.77       2   41.97
     2.6   41.97     4.6   43.67     6.6   45.57     8.6   47.47    10.6   49.37
#Mann= 3 , 0 , 0
   -14.2    .035       0       0    .035       0     4.6    .035       0
#XS Ineff= 2 , 0
               0      50     4.6              50
Permanent Ineff=
       F       F
#Block Obstruct= 2 , 0
                             4.6
Bank Sta=0,4.6
XS Rating Curve= 0
Exp/Cntr=.3,.1

Type RM Length L Ch R = 1 ,1840.00 ,40,40,40
BEGIN DESCRIPTION:
36.04
END DESCRIPTION:
#Sta/Elev= 15
   -18.2   41.74    -8.2   41.74      -8   41.94    -7.5   41.94    -7.2   41.44
    -6.8   41.44    -4.2   43.44       0   43.44      .6   41.64     1.6   41.64
     3.1   42.44     4.6   43.14     6.6   43.84     8.6   44.54    18.6   44.54
#Mann= 3 , 0 , 0
   -18.2    .035       0       0    .035       0     8.6    .035       0
#XS Ineff= 2 , 0
               0      50     8.6              50
Permanent Ineff=
       F       F
#Block Obstruct= 2 , 0
                             8.6
Bank Sta=0,8.6
XS Rating Curve= 0
Exp/Cntr=.3,.1

Type RM Length L Ch R = 1 ,1800.00 ,50,50,50
BEGIN DESCRIPTION:
36
END DESCRIPTION:
#Sta/Elev= 13
   -15.3   41.16    -5.3   41.16    -3.8   42.36       0   42.36      .3   41.46
      .7   41.46     1.4   40.06     2.6   40.06     3.8   40.36     3.8   41.66
     5.8   43.16     8.8   43.66    18.8   43.66
#Mann= 3 , 0 , 0
   -15.3    .035       0       0    .035       0     8.8    .035       0
#XS Ineff= 2 , 0
               0      45     8.8              45
Permanent Ineff=
       F       F
#Block Obstruct= 2 , 0
                             8.8
Bank Sta=0,8.8
XS Rating Curve= 0
Exp/Cntr=.3,.1

Type RM Length L Ch R = 1 ,1750.00 ,50,50,50
BEGIN DESCRIPTION:
35
END DESCRIPTION:
#Sta/Elev= 13
   -15.3   39.58    -5.3   39.58    -3.8   40.78       0   40.78      .3   40.48
      .7   40.48     1.1   39.08     2.3   39.08     3.5   39.38     3.5   40.58
     5.5   41.58     8.5   42.08    18.5   42.08
#Mann= 3 , 0 , 0
   -15.3    .035       0       0    .035       0     8.5    .035       0
#XS Ineff= 2 , 0
               0      45     8.5              45
Permanent Ineff=
       F       F
#Block Obstruct= 2 , 0
                             8.5
Bank Sta=0,8.5
XS Rating Curve= 0
Exp/Cntr=.3,.1

Type RM Length L Ch R = 1 ,1700.00 ,32,32,32
BEGIN DESCRIPTION:
34
END DESCRIPTION:
#Sta/Elev= 11
     -14   37.69      -4   37.69    -2.3   38.99       0   38.99     1.5   38.19
       3   38.19     4.2   38.49     6.2   38.79     9.2   40.89    11.2   41.89
    21.2   41.89
#Mann= 3 , 0 , 0
     -14    .035       0       0    .035       0    11.2    .035       0
#XS Ineff= 2 , 0
               0      45    11.2              45
Permanent Ineff=
       F       F
#Block Obstruct= 2 , 0
                            11.2
Bank Sta=0,11.2
XS Rating Curve= 0
Exp/Cntr=.3,.1

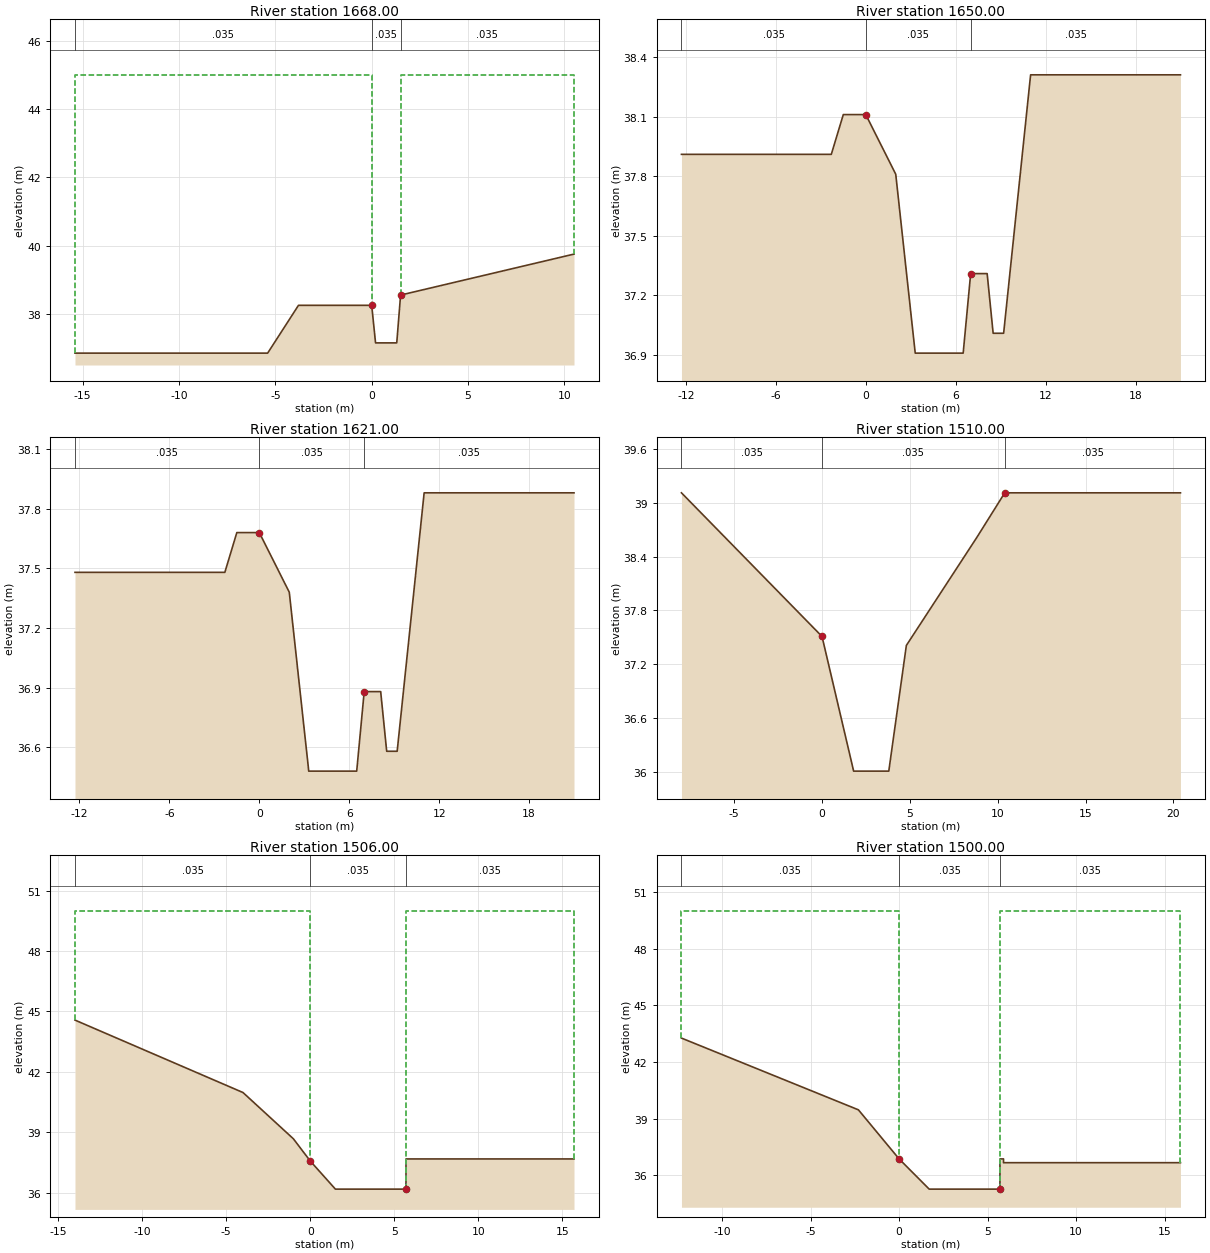
Type RM Length L Ch R = 1 ,1668.00 ,18,18,18
BEGIN DESCRIPTION:
33.018
END DESCRIPTION:
#Sta/Elev= 10
   -15.4   36.85    -5.4   36.85    -3.8   38.25       0   38.25      .2   37.15
     1.3   37.15     1.5   38.55     4.5   38.95     7.5   39.35    10.5   39.75
#Mann= 3 , 0 , 0
   -15.4    .035       0       0    .035       0     1.5    .035       0
#XS Ineff= 2 , 0
               0      45     1.5              45
Permanent Ineff=
       F       F
#Block Obstruct= 2 , 0
                             1.5
Bank Sta=0,1.5
XS Rating Curve= 0
Exp/Cntr=.3,.1

Type RM Length L Ch R = 1 ,1650.00 ,29,29,29
BEGIN DESCRIPTION:
33
END DESCRIPTION:
#Sta/Elev= 13
   -12.3   37.91    -2.3   37.91    -1.5   38.11       0   38.11       2   37.81
     3.3   36.91     6.5   36.91       7   37.31     8.1   37.31     8.5   37.01
     9.2   37.01      11   38.31      21   38.31
#Mann= 3 , 0 , 0
   -12.3    .035       0       0    .035       0       7    .035       0
#XS Ineff= 2 , 0
               0      45       7              45
Permanent Ineff=
       F       F
#Block Obstruct= 2 , 0
                               7
Bank Sta=0,7
XS Rating Curve= 0
Exp/Cntr=.3,.1

Type RM Length L Ch R = 1 ,1621.00 ,111,111,111
BEGIN DESCRIPTION:
32.021
END DESCRIPTION:
#Sta/Elev= 13
   -12.3   37.48    -2.3   37.48    -1.5   37.68       0   37.68       2   37.38
     3.3   36.48     6.5   36.48       7   36.88     8.1   36.88     8.5   36.58
     9.2   36.58      11   37.88      21   37.88
#Mann= 3 , 0 , 0
   -12.3    .035       0       0    .035       0       7    .035       0
#XS Ineff= 2 , 0
               0      45       7              45
Permanent Ineff=
       F       F
#Block Obstruct= 2 , 0
                               7
Bank Sta=0,7
XS Rating Curve= 0
Exp/Cntr=.3,.1

Type RM Length L Ch R = 1 ,1510.00 ,4,4,4
BEGIN DESCRIPTION:
30.01
END DESCRIPTION:
#Sta/Elev= 12
      -8   39.11      -6   38.71      -4   38.31      -2   37.91       0   37.51
     1.8   36.01     3.8   36.01     4.8   37.41     6.8   38.01     8.8   38.61
    10.4   39.11    20.4   39.11
#Mann= 3 , 0 , 0
      -8    .035       0       0    .035       0    10.4    .035       0
#XS Ineff= 2 , 0
               0      50    10.4              50
Permanent Ineff=
       F       F
#Block Obstruct= 2 , 0
                           10.04
Bank Sta=0,10.4
XS Rating Curve= 0
Exp/Cntr=.3,.1

Type RM Length L Ch R = 1 ,1506.00 ,6,6,6
BEGIN DESCRIPTION:
30.006
END DESCRIPTION:
#Sta/Elev= 9
     -14   44.57      -9   42.77      -4   40.97      -1   38.67       0   37.57
     1.5   36.17     5.7   36.17     5.7   37.67    15.7   37.67
#Mann= 3 , 0 , 0
     -14    .035       0       0    .035       0     5.7    .035       0
#XS Ineff= 2 , 0
               0      50     5.7              50
Permanent Ineff=
       F       F
#Block Obstruct= 2 , 0
                             5.7
Bank Sta=0,5.7
XS Rating Curve= 0
Exp/Cntr=.3,.1

Type RM Length L Ch R = 1 ,1500.00 ,19,19,19
BEGIN DESCRIPTION:
30
END DESCRIPTION:
#Sta/Elev= 10
   -12.3   43.26    -7.3   41.36    -2.3   39.46       0   36.86     1.7   35.26
     5.7   35.26     5.7   36.86     5.9   36.86     5.9   36.66    15.9   36.66
#Mann= 3 , 0 , 0
   -12.3    .035       0       0    .035       0     5.7    .035       0
#XS Ineff= 2 , 0
               0      50     5.7              50
Permanent Ineff=
       F       F
#Block Obstruct= 2 , 0
                             5.7
Bank Sta=0,5.7
XS Rating Curve= 0
Exp/Cntr=.3,.1

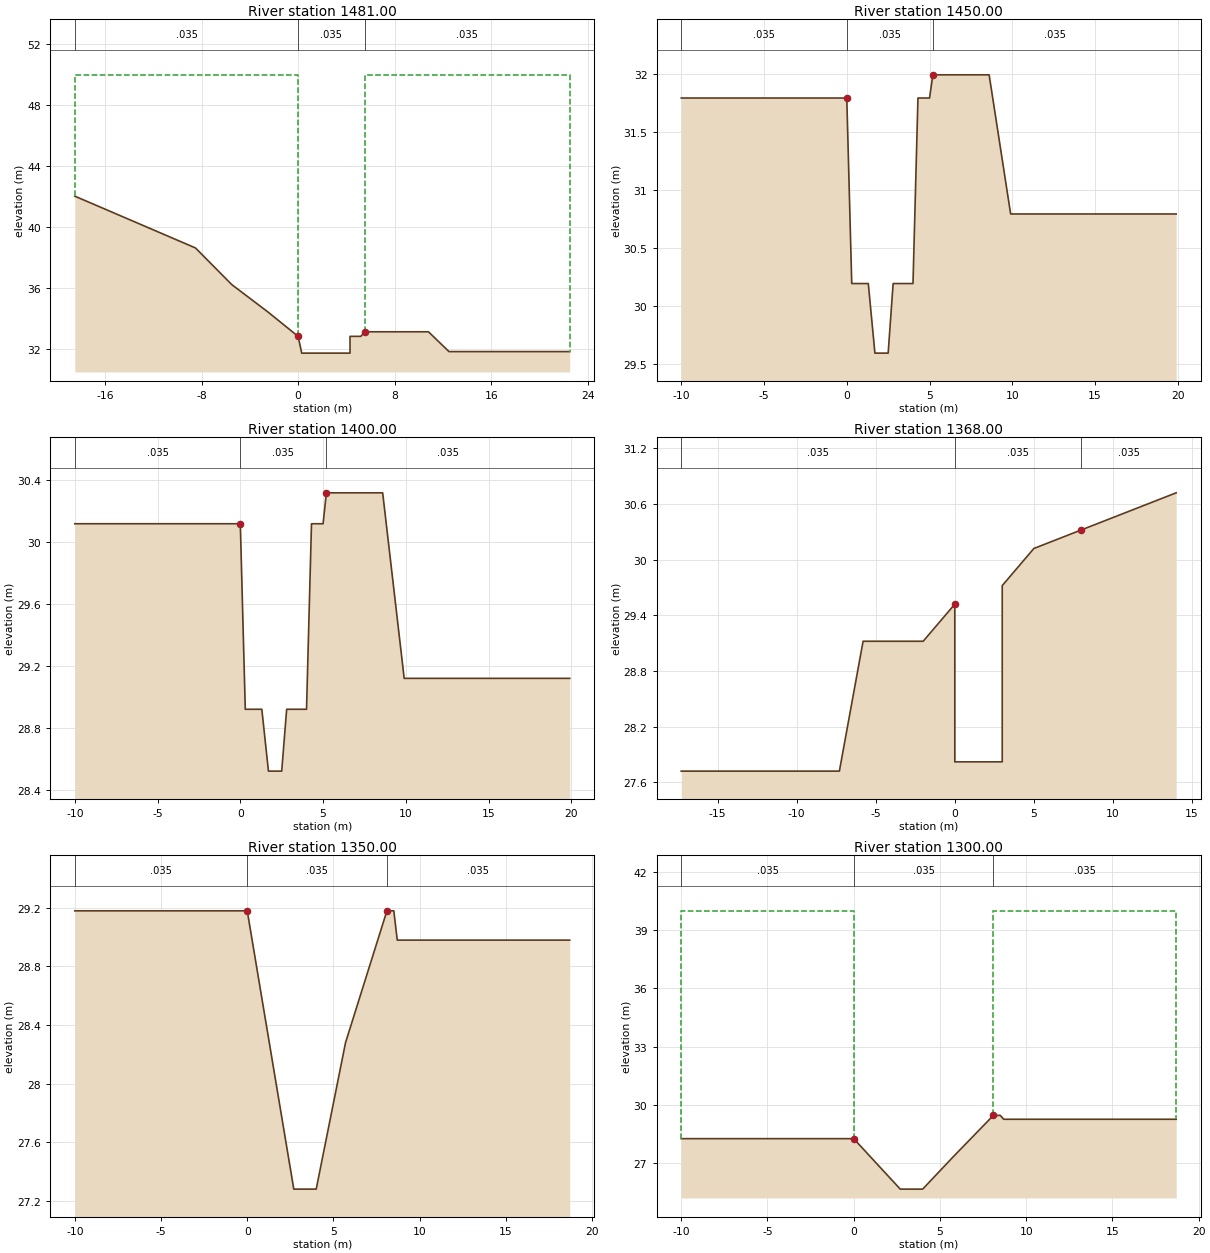
Type RM Length L Ch R = 1 ,1481.00 ,31,31,31
BEGIN DESCRIPTION:
29.031
END DESCRIPTION:
#Sta/Elev= 14
   -18.5   42.04   -13.5   40.34    -8.5   38.64    -5.5   36.24    -2.5   34.44
       0   32.84      .3   31.74     4.3   31.74     4.3   32.84     5.2   32.84
     5.5   33.14    10.8   33.14    12.5   31.84    22.5   31.84
#Mann= 3 , 0 , 0
   -18.5    .035       0       0    .035       0     5.5    .035       0
#XS Ineff= 2 , 0
               0      50     5.5              50
Permanent Ineff=
       F       F
#Block Obstruct= 2 , 0
                             5.5
Bank Sta=0,5.5
XS Rating Curve= 0
Exp/Cntr=.3,.1

Type RM Length L Ch R = 1 ,1450.00 ,50,50,50
BEGIN DESCRIPTION:
29
END DESCRIPTION:
#Sta/Elev= 14
     -10   31.79       0   31.79      .3   30.19     1.3   30.19     1.7   29.59
     2.5   29.59     2.8   30.19       4   30.19     4.3   31.79       5   31.79
     5.2   31.99     8.6   31.99     9.9   30.79    19.9   30.79
#Mann= 3 , 0 , 0
     -10    .035       0       0    .035       0     5.2    .035       0
#XS Ineff= 2 , 0
               0      40     5.2              40
Permanent Ineff=
       F       F
#Block Obstruct= 2 , 0
                             5.2
Bank Sta=0,5.2
XS Rating Curve= 0
Exp/Cntr=.3,.1

Type RM Length L Ch R = 1 ,1400.00 ,32,32,32
BEGIN DESCRIPTION:
28
END DESCRIPTION:
#Sta/Elev= 14
     -10   30.12       0   30.12      .3   28.92     1.3   28.92     1.7   28.52
     2.5   28.52     2.8   28.92       4   28.92     4.3   30.12       5   30.12
     5.2   30.32     8.6   30.32     9.9   29.12    19.9   29.12
#Mann= 3 , 0 , 0
     -10    .035       0       0    .035       0     5.2    .035       0
#XS Ineff= 2 , 0
               0      40     5.2              40
Permanent Ineff=
       F       F
#Block Obstruct= 2 , 0
                             5.2
Bank Sta=0,5.2
XS Rating Curve= 0
Exp/Cntr=.3,.1

Type RM Length L Ch R = 1 ,1368.00 ,18,18,18
BEGIN DESCRIPTION:
27.018
END DESCRIPTION:
#Sta/Elev= 12
   -17.3   27.72    -7.3   27.72    -5.8   29.12      -2   29.12       0   29.52
       0   27.82       3   27.82       3   29.72       5   30.12       8   30.32
      11   30.52      14   30.72
#Mann= 3 , 0 , 0
   -17.3    .035       0       0    .035       0       8    .035       0
#XS Ineff= 2 , 0
               0      40       8              40
Permanent Ineff=
       F       F
#Block Obstruct= 2 , 0
                               8
Bank Sta=0,8
XS Rating Curve= 0
Exp/Cntr=.3,.1

Type RM Length L Ch R = 1 ,1350.00 ,50,50,50
BEGIN DESCRIPTION:
27
END DESCRIPTION:
#Sta/Elev= 9
     -10   29.18       0   29.18     2.7   27.28       4   27.28     5.7   28.28
     8.1   29.18     8.5   29.18     8.7   28.98    18.7   28.98
#Mann= 3 , 0 , 0
     -10    .035       0       0    .035       0     8.1    .035       0
#XS Ineff= 2 , 0
               0      40     8.1              40
Permanent Ineff=
       F       F
#Block Obstruct= 2 , 0
                             8.1
Bank Sta=0,8.1
XS Rating Curve= 0
Exp/Cntr=.3,.1

Type RM Length L Ch R = 1 ,1300.00 ,6,6,6
BEGIN DESCRIPTION:
26
END DESCRIPTION:
#Sta/Elev= 9
     -10   28.26       0   28.26     2.7   25.66       4   25.66     5.7   27.26
     8.1   29.46     8.5   29.46     8.7   29.26    18.7   29.26
#Mann= 3 , 0 , 0
     -10    .035       0       0    .035       0     8.1    .035       0
#XS Ineff= 2 , 0
               0      40     8.1              40
Permanent Ineff=
       F       F
#Block Obstruct= 2 , 0
                             8.1
Bank Sta=0,8.1
XS Rating Curve= 0
Exp/Cntr=.3,.1

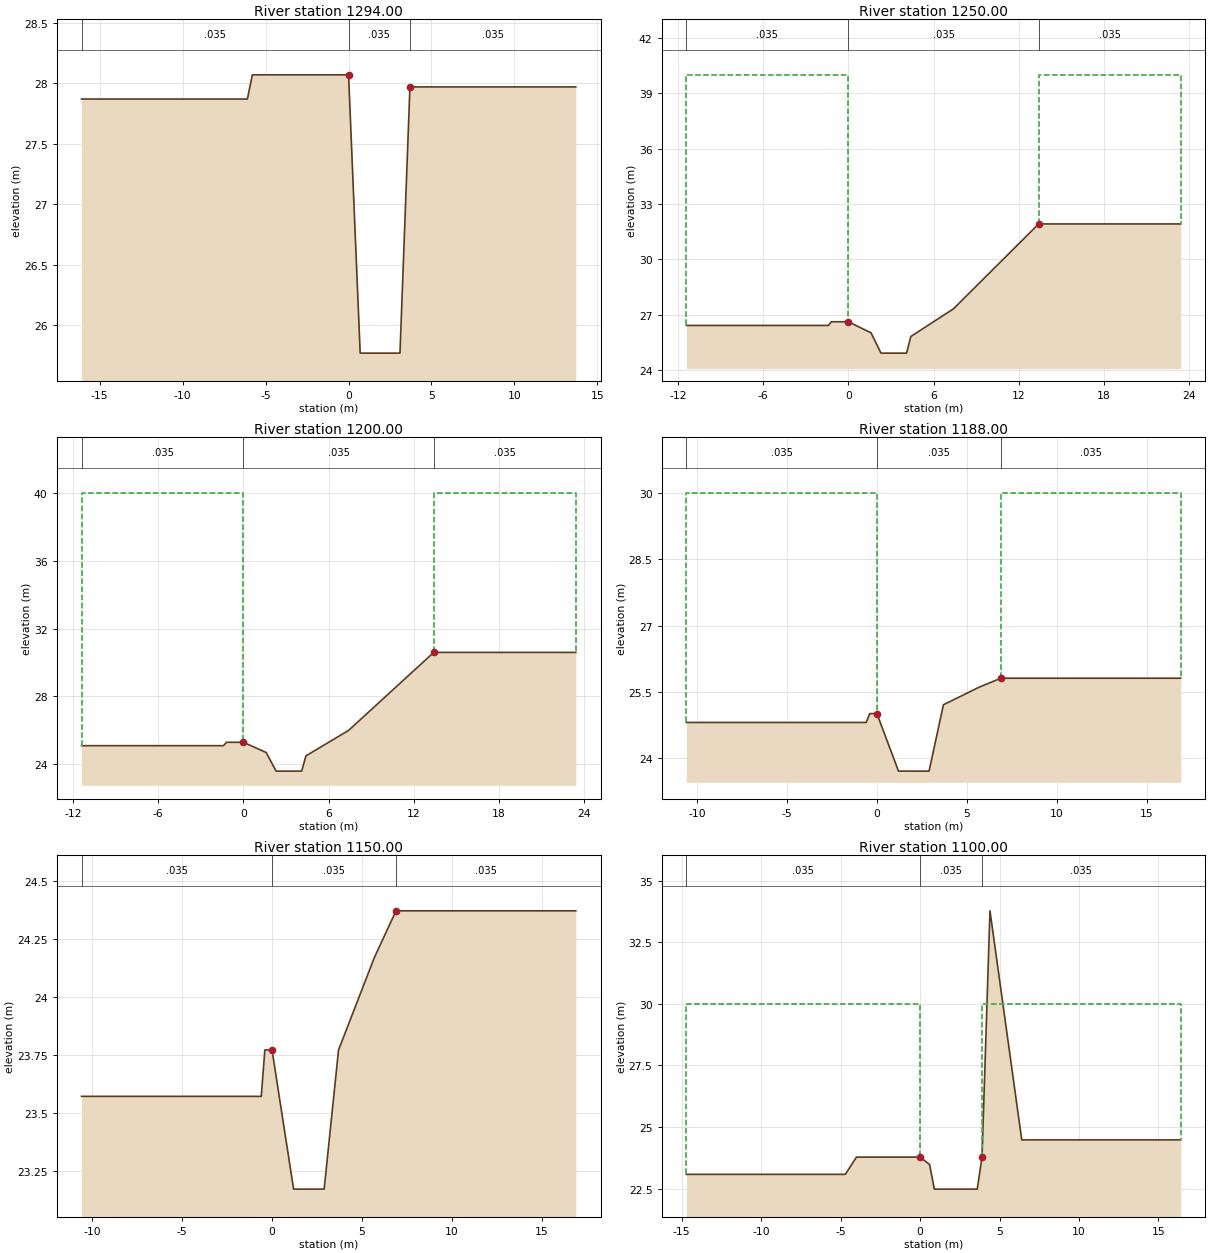
Type RM Length L Ch R = 1 ,1294.00 ,44,44,44
BEGIN DESCRIPTION:
25.044
END DESCRIPTION:
#Sta/Elev= 8
   -16.1   27.87    -6.1   27.87    -5.8   28.07       0   28.07      .7   25.77
     3.1   25.77     3.7   27.97    13.7   27.97
#Mann= 3 , 0 , 0
   -16.1    .035       0       0    .035       0     3.7    .035       0
#XS Ineff= 2 , 0
               0      40     3.7              40
Permanent Ineff=
       F       F
#Block Obstruct= 2 , 0
                             3.7
Bank Sta=0,3.7
XS Rating Curve= 0
Exp/Cntr=.3,.1

Type RM Length L Ch R = 1 ,1250.00 ,50,50,50
BEGIN DESCRIPTION:
25
END DESCRIPTION:
#Sta/Elev= 12
   -11.4   26.42    -1.4   26.42    -1.2   26.62       0   26.62     1.6   26.02
     2.3   24.92     4.1   24.92     4.4   25.82     7.4   27.32    10.4   29.62
    13.4   31.92    23.4   31.92
#Mann= 3 , 0 , 0
   -11.4    .035       0       0    .035       0    13.4    .035       0
#XS Ineff= 2 , 0
               0      40    13.4              40
Permanent Ineff=
       F       F
#Block Obstruct= 2 , 0
                            13.4
Bank Sta=0,13.4
XS Rating Curve= 0
Exp/Cntr=.3,.1

Type RM Length L Ch R = 1 ,1200.00 ,12,12,12
BEGIN DESCRIPTION:
24
END DESCRIPTION:
#Sta/Elev= 12
   -11.4   25.09    -1.4   25.09    -1.2   25.29       0   25.29     1.6   24.69
     2.3   23.59     4.1   23.59     4.4   24.49     7.4   25.99    10.4   28.29
    13.4   30.59    23.4   30.59
#Mann= 3 , 0 , 0
   -11.4    .035       0       0    .035       0    13.4    .035       0
#XS Ineff= 2 , 0
               0      40    13.4              40
Permanent Ineff=
       F       F
#Block Obstruct= 2 , 0
                            13.4
Bank Sta=0,13.4
XS Rating Curve= 0
Exp/Cntr=.3,.1

Type RM Length L Ch R = 1 ,1188.00 ,38,38,38
BEGIN DESCRIPTION:
23.038
END DESCRIPTION:
#Sta/Elev= 10
   -10.6   24.81     -.6   24.81     -.4   25.01       0   25.01     1.2   23.71
     2.9   23.71     3.7   25.21     5.7   25.61     6.9   25.81    16.9   25.81
#Mann= 3 , 0 , 0
   -10.6    .035       0       0    .035       0     6.9    .035       0
#XS Ineff= 2 , 0
               0      30     6.9              30
Permanent Ineff=
       F       F
#Block Obstruct= 2 , 0
                             6.9
Bank Sta=0,6.9
XS Rating Curve= 0
Exp/Cntr=.3,.1

Type RM Length L Ch R = 1 ,1150.00 ,50,50,50
BEGIN DESCRIPTION:
23
END DESCRIPTION:
#Sta/Elev= 10
   -10.6   23.57     -.6   23.57     -.4   23.77       0   23.77     1.2   23.17
     2.9   23.17     3.7   23.77     5.7   24.17     6.9   24.37    16.9   24.37
#Mann= 3 , 0 , 0
   -10.6    .035       0       0    .035       0     6.9    .035       0
#XS Ineff= 2 , 0
               0      30     6.9              30
Permanent Ineff=
       F       F
#Block Obstruct= 2 , 0
                             6.9
Bank Sta=0,6.9
XS Rating Curve= 0
Exp/Cntr=.3,.1

Type RM Length L Ch R = 1 ,1100.00 ,49,49,49
BEGIN DESCRIPTION:
22
END DESCRIPTION:
#Sta/Elev= 11
   -14.7   23.08    -4.7   23.08      -4   23.78       0   23.78      .6   23.48
      .9   22.48     3.6   22.48     3.9   23.78     4.4   33.78     6.4   24.48
    16.4   24.48
#Mann= 3 , 0 , 0
   -14.7    .035       0       0    .035       0     3.9    .035       0
#XS Ineff= 2 , 0
               0      30     3.9              30
Permanent Ineff=
       F       F
#Block Obstruct= 2 , 0
                             3.9
Bank Sta=0,3.9
XS Rating Curve= 0
Exp/Cntr=.3,.1

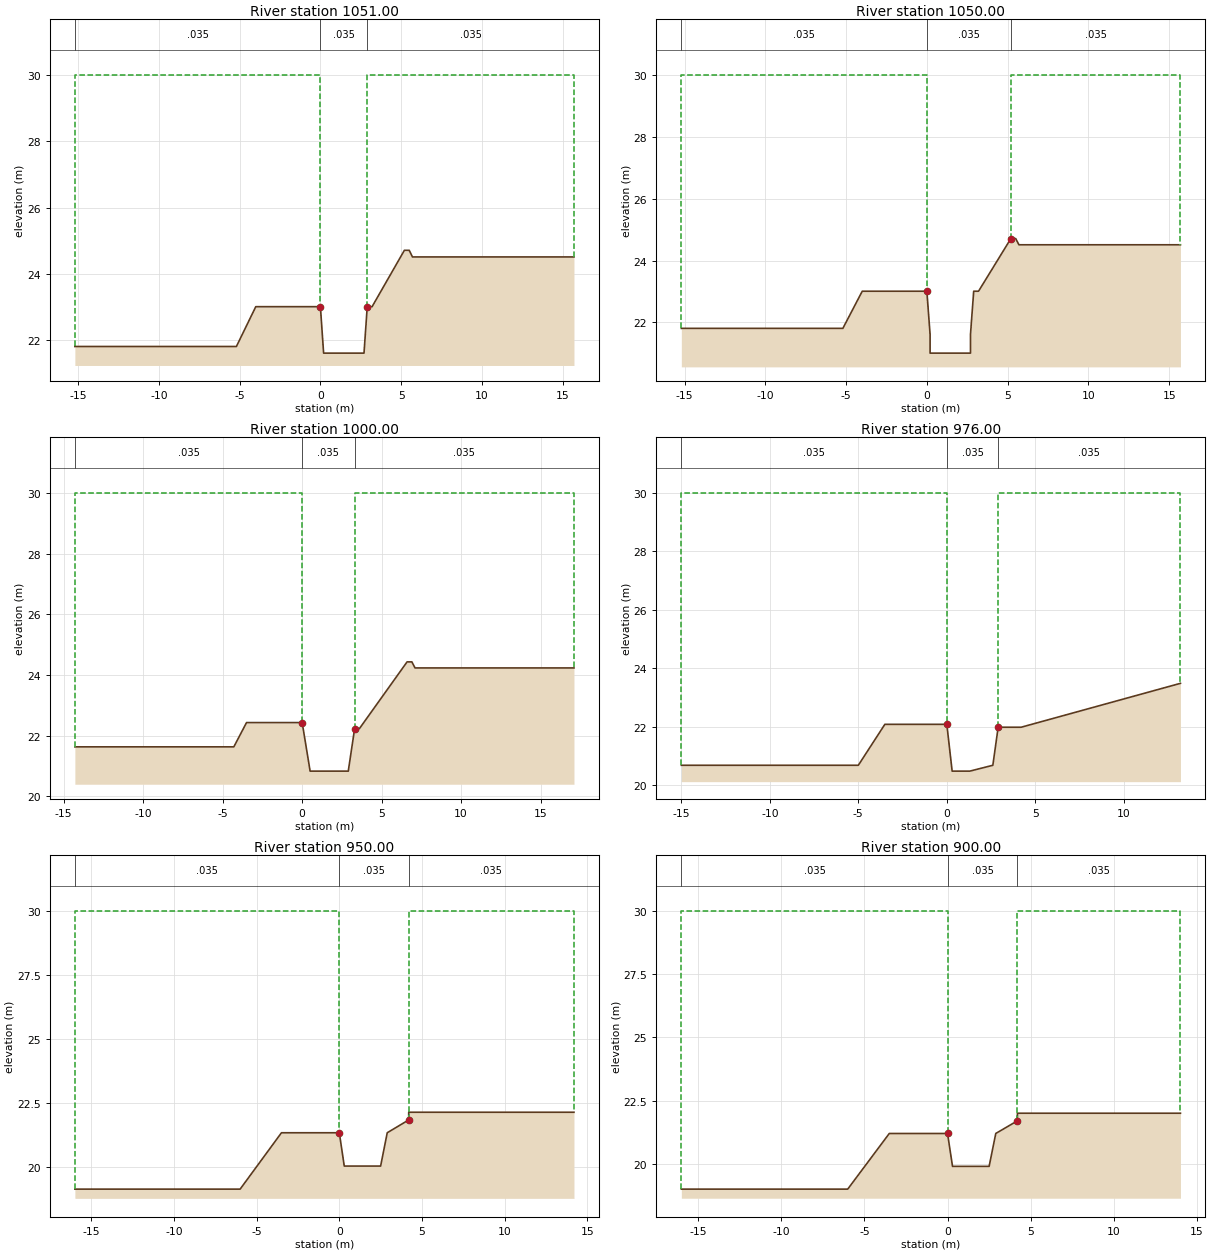
Type RM Length L Ch R = 1 ,1051.00 ,1,1,1
BEGIN DESCRIPTION:
21.001
END DESCRIPTION:
#Sta/Elev= 12
   -15.2   21.81    -5.2   21.81      -4   23.01       0   23.01      .2   21.61
     2.7   21.61     2.9   23.01     3.2   23.01     5.2   24.71     5.5   24.71
     5.7   24.51    15.7   24.51
#Mann= 3 , 0 , 0
   -15.2    .035       0       0    .035       0     2.9    .035       0
#XS Ineff= 2 , 0
               0      30     2.9              30
Permanent Ineff=
       F       F
#Block Obstruct= 2 , 0
                             2.9
Bank Sta=0,2.9
XS Rating Curve= 0
Exp/Cntr=.3,.1

Type RM Length L Ch R = 1 ,1050.00 ,50,50,50
BEGIN DESCRIPTION:
21
END DESCRIPTION:
#Sta/Elev= 14
   -15.2   21.81    -5.2   21.81      -4   23.01       0   23.01      .2   21.61
      .2   21.01     2.7   21.01     2.7   21.61     2.9   23.01     3.2   23.01
     5.2   24.71     5.5   24.71     5.7   24.51    15.7   24.51
#Mann= 3 , 0 , 0
   -15.2    .035       0       0    .035       0     5.2    .035       0
#XS Ineff= 2 , 0
               0      30     5.2              30
Permanent Ineff=
       F       F
#Block Obstruct= 2 , 0
                             5.2
Bank Sta=0,5.2
XS Rating Curve= 0
Exp/Cntr=.3,.1

Type RM Length L Ch R = 1 ,1000.00 ,24,24,24
BEGIN DESCRIPTION:
20
END DESCRIPTION:
#Sta/Elev= 12
   -14.3   21.63    -4.3   21.63    -3.5   22.43       0   22.43      .5   20.83
     2.9   20.83     3.3   22.23     3.6   22.23     6.6   24.43     6.9   24.43
     7.1   24.23    17.1   24.23
#Mann= 3 , 0 , 0
   -14.3    .035       0       0    .035       0     3.3    .035       0
#XS Ineff= 2 , 0
               0      30     3.3              30
Permanent Ineff=
       F       F
#Block Obstruct= 2 , 0
                               3
Bank Sta=0,3.3
XS Rating Curve= 0
Exp/Cntr=.3,.1

Type RM Length L Ch R = 1 ,976.00  ,26,26,26
BEGIN DESCRIPTION:
19.026
END DESCRIPTION:
#Sta/Elev= 12
     -15   20.69      -5   20.69    -3.5   22.09       0   22.09      .3   20.49
     1.3   20.49     2.6   20.69     2.9   21.99     4.2   21.99     7.2   22.49
    10.2   22.99    13.2   23.49
#Mann= 3 , 0 , 0
     -15    .035       0       0    .035       0     2.9    .035       0
#XS Ineff= 2 , 0
               0      30     2.9              30
Permanent Ineff=
       F       F
#Block Obstruct= 2 , 0
                             2.9
Bank Sta=0,2.9
XS Rating Curve= 0
Exp/Cntr=.3,.1

Type RM Length L Ch R = 1 ,950.00  ,50,50,50
BEGIN DESCRIPTION:
19
END DESCRIPTION:
#Sta/Elev= 10
     -16   19.14      -6   19.14    -3.5   21.34       0   21.34      .3   20.04
     2.5   20.04     2.9   21.34     4.2   21.84     4.2   22.14    14.2   22.14
#Mann= 3 , 0 , 0
     -16    .035       0       0    .035       0     4.2    .035       0
#XS Ineff= 2 , 0
               0      30     4.2              30
Permanent Ineff=
       F       F
#Block Obstruct= 2 , 0
                             4.2
Bank Sta=0,4.2
XS Rating Curve= 0
Exp/Cntr=.3,.1

Type RM Length L Ch R = 1 ,900.00  ,21,21,21
BEGIN DESCRIPTION:
18
END DESCRIPTION:
#Sta/Elev= 10
     -16      19      -6      19    -3.5    21.2       0    21.2      .3    19.9
     2.5    19.9     2.9    21.2     4.2    21.7     4.2      22      14      22
#Mann= 3 , 0 , 0
     -16    .035       0       0    .035       0     4.2    .035       0
#XS Ineff= 2 , 0
               0      30     4.2              30
Permanent Ineff=
       F       F
#Block Obstruct= 2 , 0
                             4.2
Bank Sta=0,4.2
XS Rating Curve= 0
Exp/Cntr=.3,.1

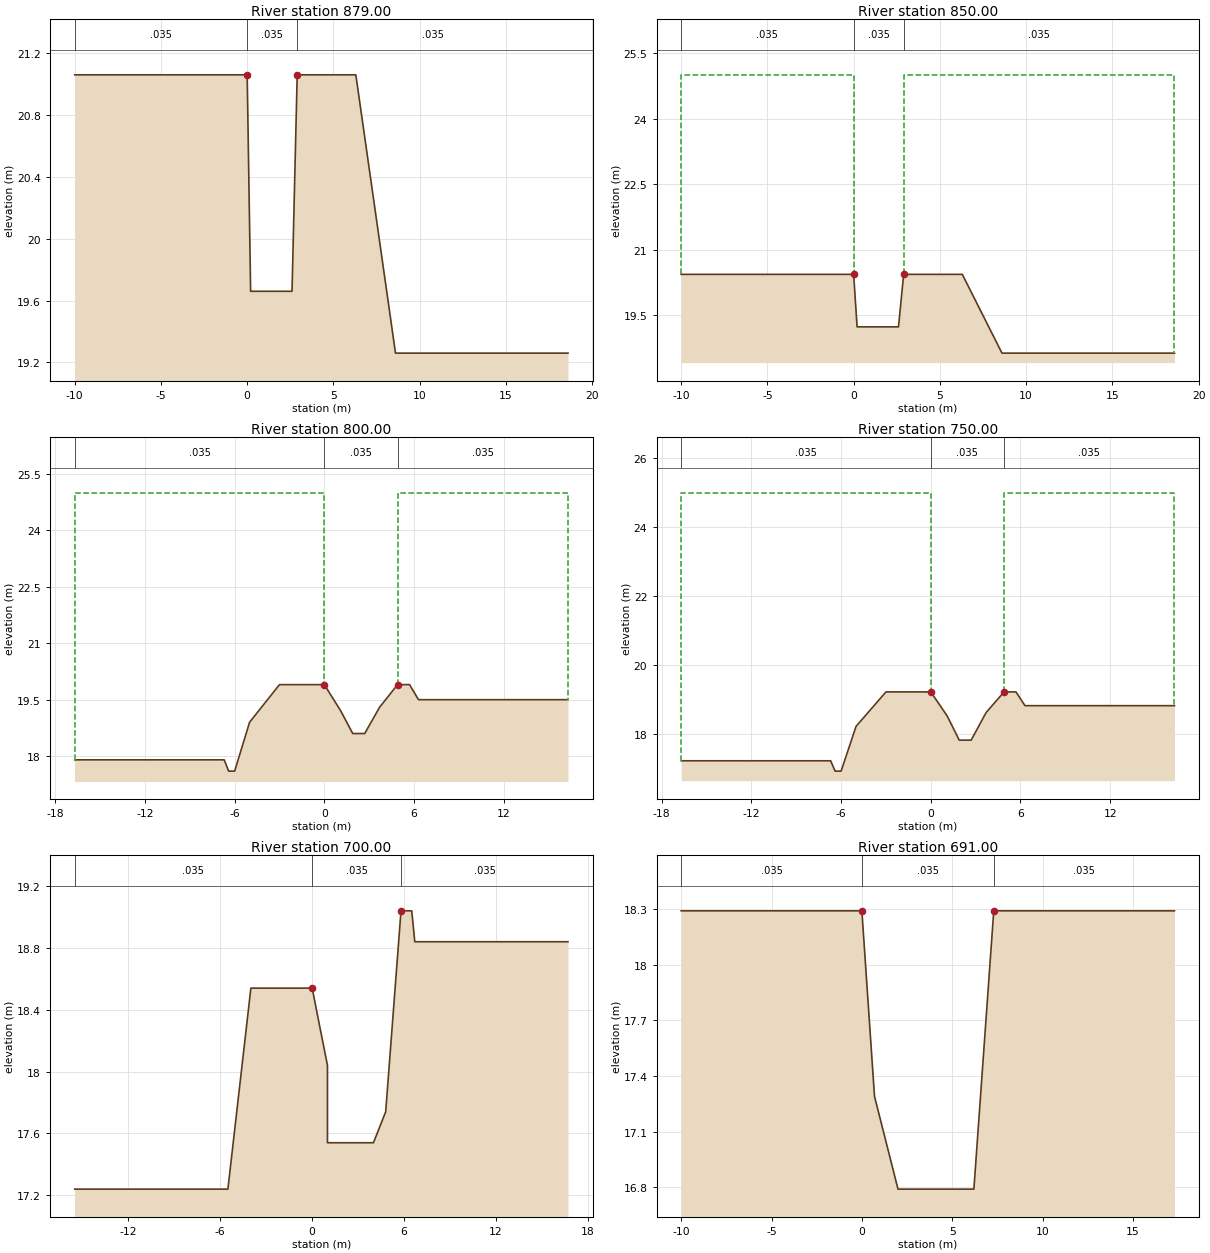
Type RM Length L Ch R = 1 ,879.00  ,29,29,29
BEGIN DESCRIPTION:
17.029
END DESCRIPTION:
#Sta/Elev= 8
     -10   21.06       0   21.06      .2   19.66     2.6   19.66     2.9   21.06
     6.3   21.06     8.6   19.26    18.6   19.26
#Mann= 3 , 0 , 0
     -10    .035       0       0    .035       0     2.9    .035       0
#XS Ineff= 2 , 0
               0      30     2.9              30
Permanent Ineff=
       F       F
#Block Obstruct= 2 , 0
                             2.9
Bank Sta=0,2.9
XS Rating Curve= 0
Exp/Cntr=.3,.1

Type RM Length L Ch R = 1 ,850.00  ,50,50,50
BEGIN DESCRIPTION:
17
END DESCRIPTION:
#Sta/Elev= 8
     -10   20.44       0   20.44      .2   19.24     2.6   19.24     2.9   20.44
     6.3   20.44     8.6   18.64    18.6   18.64
#Mann= 3 , 0 , 0
     -10    .035       0       0    .035       0     2.9    .035       0
#XS Ineff= 2 , 0
               0      25     2.9              25
Permanent Ineff=
       F       F
#Block Obstruct= 2 , 0
                             2.9
Bank Sta=0,2.9
XS Rating Curve= 0
Exp/Cntr=.3,.1

Type RM Length L Ch R = 1 ,800.00  ,50,50,50
BEGIN DESCRIPTION:
16
END DESCRIPTION:
#Sta/Elev= 15
   -16.7    17.9    -6.7    17.9    -6.4    17.6      -6    17.6      -5    18.9
      -3    19.9       0    19.9     1.1    19.2     1.9    18.6     2.7    18.6
     3.7    19.3     4.9    19.9     5.7    19.9     6.3    19.5    16.3    19.5
#Mann= 3 , 0 , 0
   -16.7    .035       0       0    .035       0     4.9    .035       0
#XS Ineff= 2 , 0
               0      25     4.9              25
Permanent Ineff=
       F       F
#Block Obstruct= 2 , 0
                             4.9
Bank Sta=0,4.9
XS Rating Curve= 0
Exp/Cntr=.3,.1

Type RM Length L Ch R = 1 ,750.00  ,50,50,50
BEGIN DESCRIPTION:
15
END DESCRIPTION:
#Sta/Elev= 15
   -16.7   17.22    -6.7   17.22    -6.4   16.92      -6   16.92      -5   18.22
      -3   19.22       0   19.22     1.1   18.52     1.9   17.82     2.7   17.82
     3.7   18.62     4.9   19.22     5.7   19.22     6.3   18.82    16.3   18.82
#Mann= 3 , 0 , 0
   -16.7    .035       0       0    .035       0     4.9    .035       0
#XS Ineff= 2 , 0
               0      25     4.9              25
Permanent Ineff=
       F       F
#Block Obstruct= 2 , 0
                             4.9
Bank Sta=0,4.9
XS Rating Curve= 0
Exp/Cntr=.3,.1

Type RM Length L Ch R = 1 ,700.00  ,9,9,9
BEGIN DESCRIPTION:
14
END DESCRIPTION:
#Sta/Elev= 12
   -15.5   17.24    -5.5   17.24      -4   18.54       0   18.54       1   18.04
       1   17.54       4   17.54     4.8   17.74     5.8   19.04     6.5   19.04
     6.7   18.84    16.7   18.84
#Mann= 3 , 0 , 0
   -15.5    .035       0       0    .035       0     5.8    .035       0
#XS Ineff= 2 , 0
               0      25     5.8              25
Permanent Ineff=
       F       F
#Block Obstruct= 2 , 0
                             5.8
Bank Sta=0,5.8
XS Rating Curve= 0
Exp/Cntr=.3,.1

Type RM Length L Ch R = 1 ,691.00  ,41,41,41
BEGIN DESCRIPTION:
13.041
END DESCRIPTION:
#Sta/Elev= 7
     -10   18.29       0   18.29      .7   17.29       2   16.79     6.2   16.79
     7.3   18.29    17.3   18.29
#Mann= 3 , 0 , 0
     -10    .035       0       0    .035       0     7.3    .035       0
#XS Ineff= 2 , 0
               0      25     7.3              25
Permanent Ineff=
       F       F
#Block Obstruct= 2 , 0
                             7.3
Bank Sta=0,7.3
XS Rating Curve= 0
Exp/Cntr=.3,.1