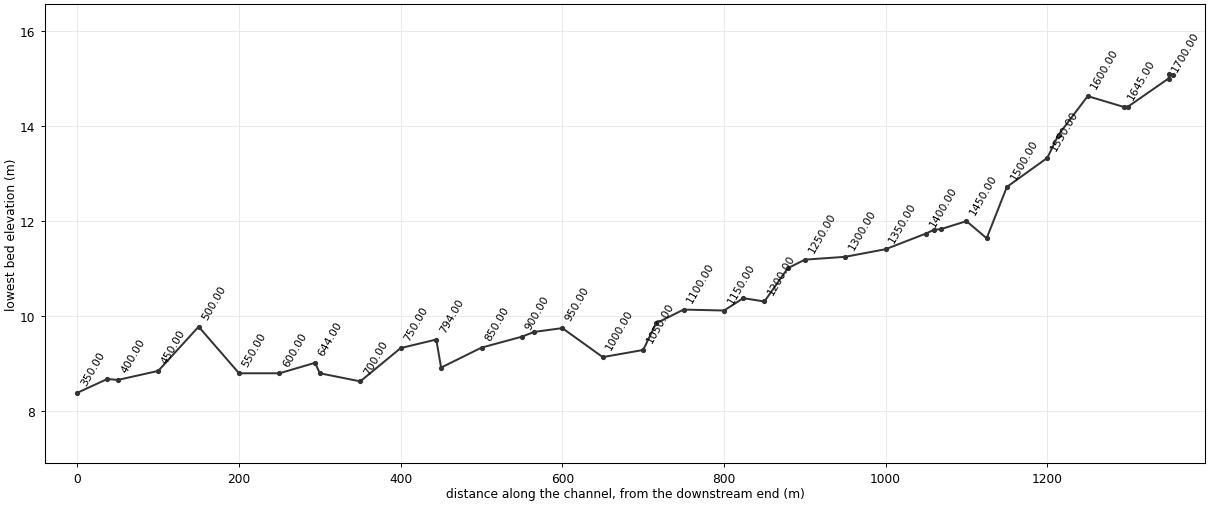
--- MSC.prj (project) ---

Proj Title=MANGSANG
Current Plan=p01
Default Exp/Contr=.3,.1
SI Units
Geom File=g01
Flow File=f01
Plan File=p01
Y Axis Title=Elevation
X Axis Title(PF)=Main Channel Distance
X Axis Title(XS)=Station
BEGIN DESCRIPTION:
           BACK WATER COMPUTATION
      APPLICATION OF HEC-2 BY Samju Construction Engineering
      mangsang-ch: 10,20,30,50,80 yr
END DESCRIPTION:
DSS Export Rating Curves= 0
DSS Export Rating Curve Sorted= 0
DSS Export Volume Flow Curves= 0
DXF OffsetX= 0
DXF OffsetY= 0
DXF ScaleX= 1
DXF ScaleY= 10

--- MSC.p01 (plan) ---

Plan Title=Imported Plan 01
Version=Version 3.0.1  Mar 2001
Short Identifier=Imported Pla
Geom File=g01
Flow File=f01
Subcritical Flow
K Sum by GR= 0
Std Step Tol= 0.003
Critical Tol= 0.003
Num of Std Step Trials= 20
Max Error Tol= 0.1
Flow Tol Ratio= 0.001
Split Flow NTrial= 30
Split Flow Tol= 0.02
Split Flow Ratio= 0.02
Log Output Level= 0
Friction Slope Method= 1
Unsteady Friction Slope Method= 2
Parabolic Critical Depth
Global Vel Dist= 0 , 0 , 0
Global Log Level= 0
CheckData=True
Encroach Param=-1 ,0,0, 0
Computation Interval=1HOUR
Output Interval=1HOUR
Run HTab= 0
Run UNet= 0
Run PostProcess= 0
UNET Theta= 1
UNET ZTol= 0.02
UNET ZSATol= 0.1
UNET MxIter= 20
UNET MaxInSteps= 20
UNET DtIC= 0
UNET DtMin= 0
UNET MaxCRTS= 20
UNET WFStab= 2
UNET SFStab= 1
UNET WFX= 1
UNET SFX= 1
UNET Convert EG Bridges=-1
UNET Use Existing IB Tables=-1
Instantaneous Interval=1HOUR
Write IC File= 0
Write Velocity= 0
Write Detailed= 0

--- MSC.f01 (steady flow) ---

Flow Title=Imported Flow 01
Version=Version 3.0.1  Mar 2001
Number of Profiles= 5
Profile Names=10YR,20YR,30YR,50YR,80YR
River Rch & RM=RIVER-1,Reach-1         ,1705.00
    8.36    9.21     9.7   10.33    10.9
River Rch & RM=RIVER-1,Reach-1         ,1000.00
   16.67   18.37   19.37   20.62   21.78
Boundary for River Rch & Prof#=RIVER-1,Reach-1         , 1
Up Type= 0
Dn Type= 3
Dn Slope=.004
Boundary for River Rch & Prof#=RIVER-1,Reach-1         , 2
Up Type= 0
Dn Type= 3
Dn Slope=.004
Boundary for River Rch & Prof#=RIVER-1,Reach-1         , 3
Up Type= 0
Dn Type= 3
Dn Slope=.004
Boundary for River Rch & Prof#=RIVER-1,Reach-1         , 4
Up Type= 0
Dn Type= 3
Dn Slope=.004
Boundary for River Rch & Prof#=RIVER-1,Reach-1         , 5
Up Type= 0
Dn Type= 3
Dn Slope=.004
DSS Import GetInterval= 0
DSS Import GetPeak= 0
DSS Import FillOption= 0

--- MSC.g01 (geometry) ---

Geom Title=Imported Geom 01
Version=Version 3.0.1  Mar 2001

River Reach=RIVER-1         ,Reach-1
Reach XY= 2
              .5             .95              .5             .05

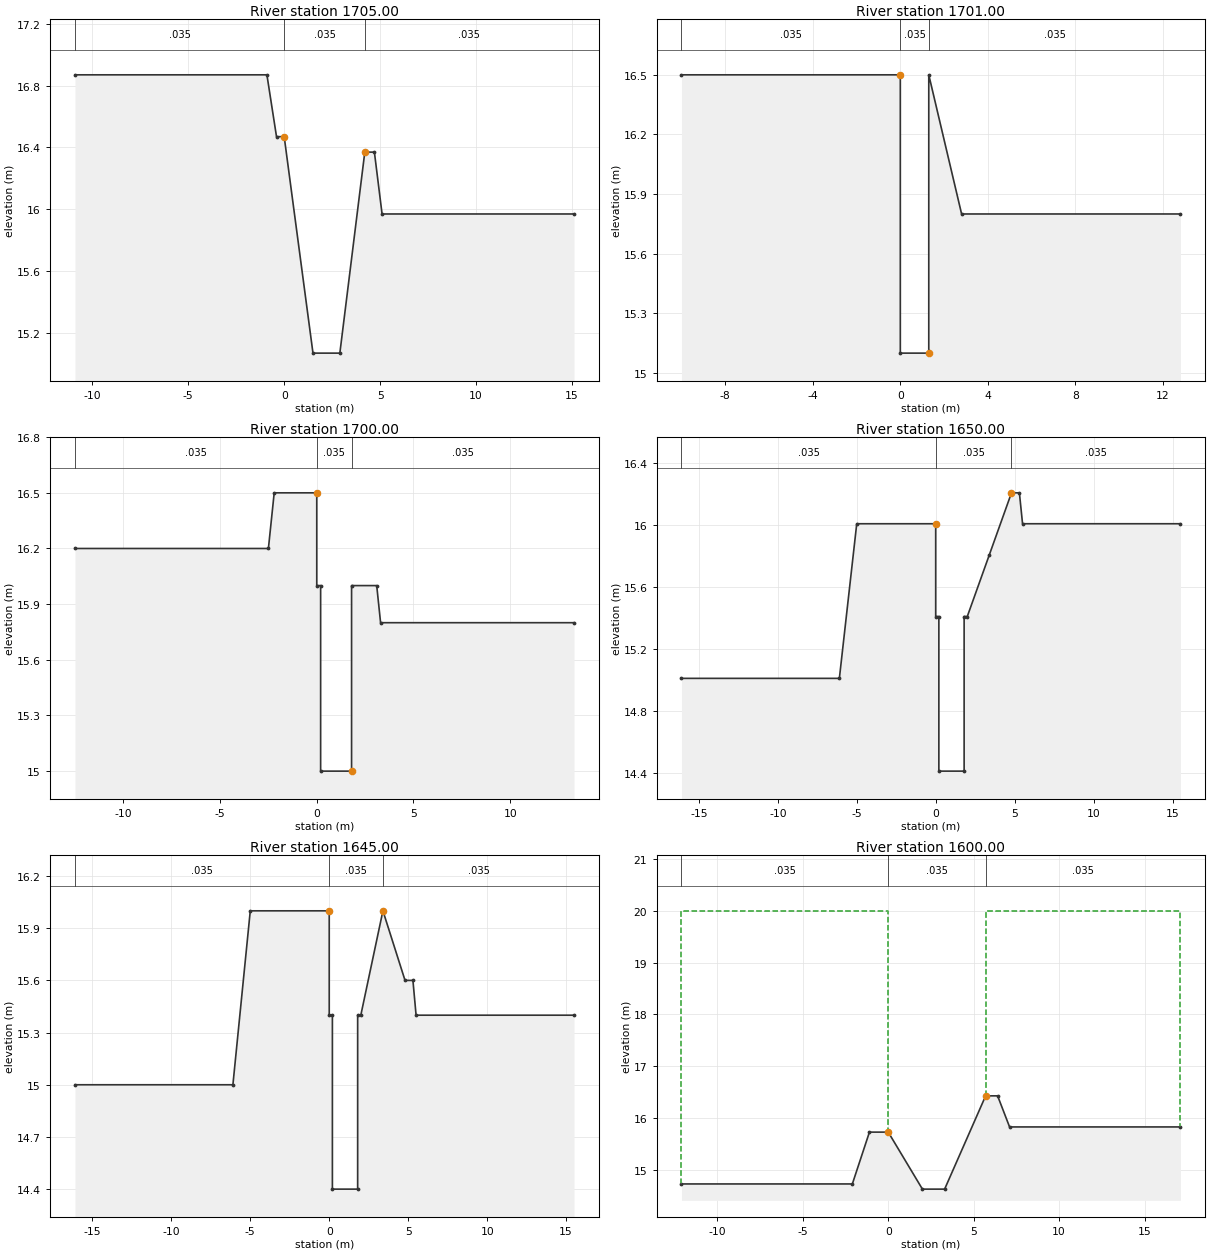
Type RM Length L Ch R = 1 ,1705.00 ,4,4,4
BEGIN DESCRIPTION:
34.005
END DESCRIPTION:
#Sta/Elev= 10
   -10.9   16.87     -.9   16.87     -.4   16.47       0   16.47     1.5   15.07
     2.9   15.07     4.2   16.37     4.7   16.37     5.1   15.97    15.1   15.97
#Mann= 3 , 0 , 0
   -10.9    .035       0       0    .035       0     4.2    .035       0
#XS Ineff= 2 , 0
               0      25     4.2              25
Permanent Ineff=
       F       F
#Block Obstruct= 2 , 0
                             4.2
Bank Sta=0,4.2
XS Rating Curve= 0
Exp/Cntr=.3,.1

Type RM Length L Ch R = 1 ,1701.00 ,1,1,1
BEGIN DESCRIPTION:
34.001
END DESCRIPTION:
#Sta/Elev= 7
     -10    16.5       0    16.5       0    15.1     1.3    15.1     1.3    16.5
     2.8    15.8    12.8    15.8
#Mann= 3 , 0 , 0
     -10    .035       0       0    .035       0     1.3    .035       0
#XS Ineff= 2 , 0
               0      25     1.3              25
Permanent Ineff=
       F       F
#Block Obstruct= 2 , 0
                             1.3
Bank Sta=0,1.3
XS Rating Curve= 0
Exp/Cntr=.3,.1

Type RM Length L Ch R = 1 ,1700.00 ,50,50,50
BEGIN DESCRIPTION:
34
END DESCRIPTION:
#Sta/Elev= 12
   -12.5    16.2    -2.5    16.2    -2.2    16.5       0    16.5       0      16
      .2      16      .2      15     1.8      15     1.8      16     3.1      16
     3.3    15.8    13.3    15.8
#Mann= 3 , 0 , 0
   -12.5    .035       0       0    .035       0     1.8    .035       0
#XS Ineff= 2 , 0
               0      25     1.8              25
Permanent Ineff=
       F       F
#Block Obstruct= 2 , 0
                             1.8
Bank Sta=0,1.8
XS Rating Curve= 0
Exp/Cntr=.3,.1

Type RM Length L Ch R = 1 ,1650.00 ,5,5,5
BEGIN DESCRIPTION:
33
END DESCRIPTION:
#Sta/Elev= 15
   -16.1   15.01    -6.1   15.01      -5   16.01       0   16.01       0   15.41
      .2   15.41      .2   14.41     1.8   14.41     1.8   15.41       2   15.41
     3.4   15.81     4.8   16.21     5.3   16.21     5.5   16.01    15.5   16.01
#Mann= 3 , 0 , 0
   -16.1    .035       0       0    .035       0     4.8    .035       0
#XS Ineff= 2 , 0
               0      25     4.8              25
Permanent Ineff=
       F       F
#Block Obstruct= 2 , 0
                             4.8
Bank Sta=0,4.8
XS Rating Curve= 0
Exp/Cntr=.3,.1

Type RM Length L Ch R = 1 ,1645.00 ,45,45,45
BEGIN DESCRIPTION:
32.045
END DESCRIPTION:
#Sta/Elev= 15
   -16.1      15    -6.1      15      -5      16       0      16       0    15.4
      .2    15.4      .2    14.4     1.8    14.4     1.8    15.4       2    15.4
     3.4      16     4.8    15.6     5.3    15.6     5.5    15.4    15.5    15.4
#Mann= 3 , 0 , 0
   -16.1    .035       0       0    .035       0     3.4    .035       0
#XS Ineff= 2 , 0
               0      25     3.4              25
Permanent Ineff=
       F       F
#Block Obstruct= 2 , 0
                             3.4
Bank Sta=0,3.4
XS Rating Curve= 0
Exp/Cntr=.3,.1

Type RM Length L Ch R = 1 ,1600.00 ,36,36,36
BEGIN DESCRIPTION:
32
END DESCRIPTION:
#Sta/Elev= 10
   -12.1   14.73    -2.1   14.73    -1.1   15.73       0   15.73       2   14.63
     3.3   14.63     5.7   16.43     6.4   16.43     7.1   15.83    17.1   15.83
#Mann= 3 , 0 , 0
   -12.1    .035       0       0    .035       0     5.7    .035       0
#XS Ineff= 2 , 0
               0      20     5.7              20
Permanent Ineff=
       F       F
#Block Obstruct= 2 , 0
                             5.7
Bank Sta=0,5.7
XS Rating Curve= 0
Exp/Cntr=.3,.1

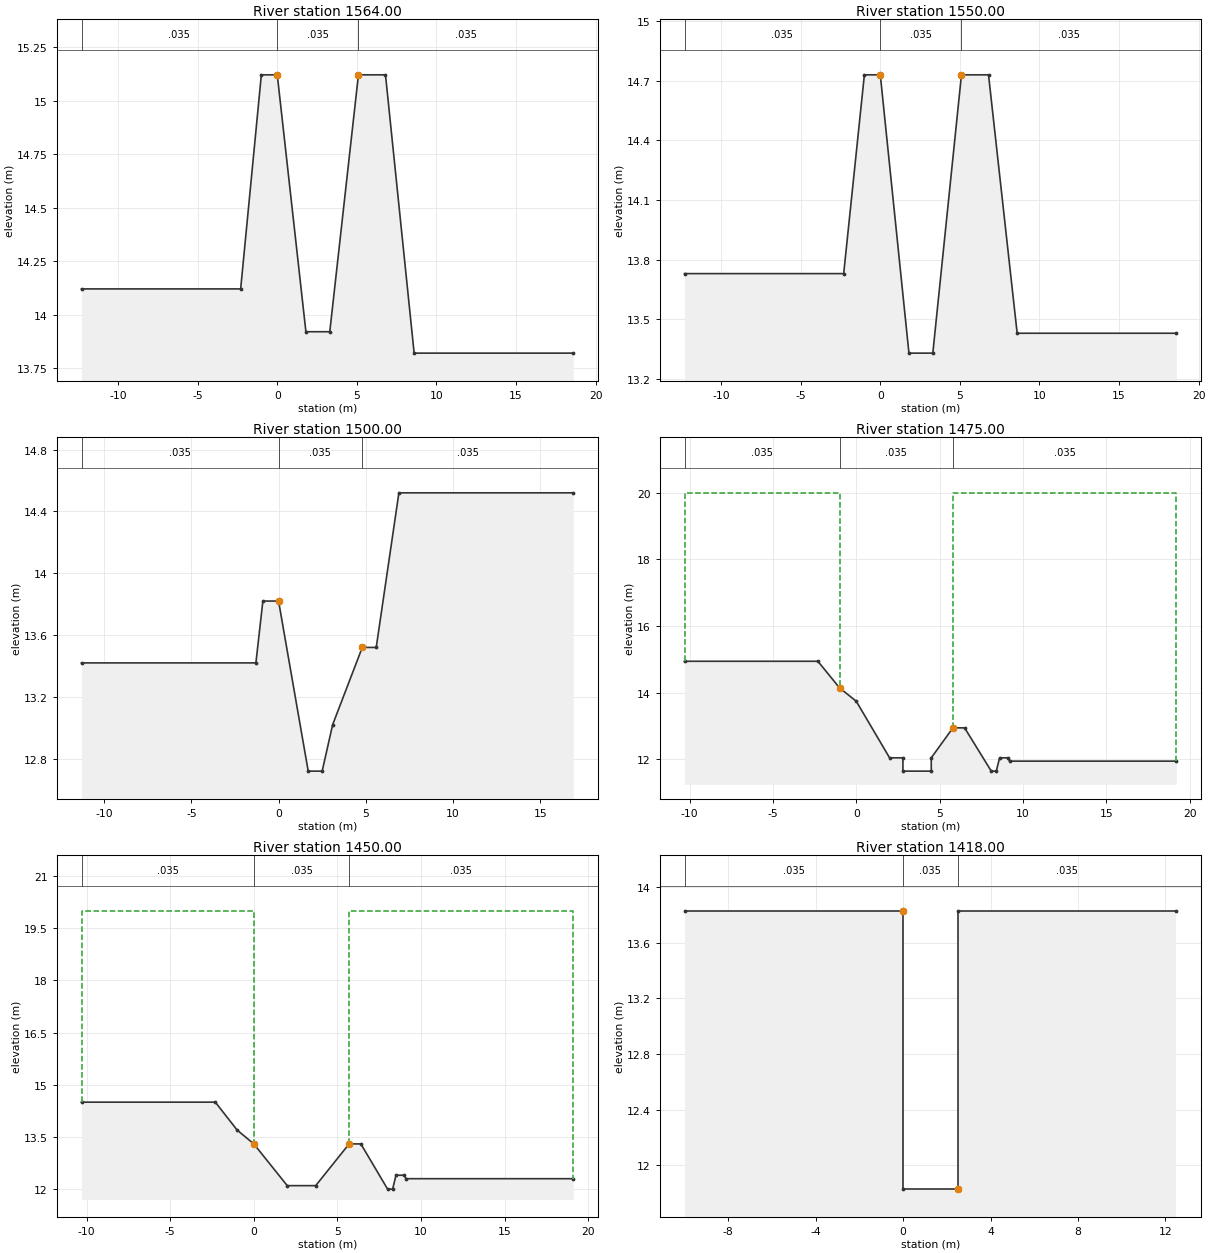
Type RM Length L Ch R = 1 ,1564.00 ,14,14,14
BEGIN DESCRIPTION:
31.014
END DESCRIPTION:
#Sta/Elev= 10
   -12.3   14.12    -2.3   14.12      -1   15.12       0   15.12     1.8   13.92
     3.3   13.92     5.1   15.12     6.8   15.12     8.6   13.82    18.6   13.82
#Mann= 3 , 0 , 0
   -12.3    .035       0       0    .035       0     5.1    .035       0
#XS Ineff= 2 , 0
               0      20     5.1              20
Permanent Ineff=
       F       F
#Block Obstruct= 2 , 0
                             5.1
Bank Sta=0,5.1
XS Rating Curve= 0
Exp/Cntr=.3,.1

Type RM Length L Ch R = 1 ,1550.00 ,50,50,50
BEGIN DESCRIPTION:
31
END DESCRIPTION:
#Sta/Elev= 10
   -12.3   13.73    -2.3   13.73      -1   14.73       0   14.73     1.8   13.33
     3.3   13.33     5.1   14.73     6.8   14.73     8.6   13.43    18.6   13.43
#Mann= 3 , 0 , 0
   -12.3    .035       0       0    .035       0     5.1    .035       0
#XS Ineff= 2 , 0
               0      20     5.1              20
Permanent Ineff=
       F       F
#Block Obstruct= 2 , 0
                             5.1
Bank Sta=0,5.1
XS Rating Curve= 0
Exp/Cntr=.3,.1

Type RM Length L Ch R = 1 ,1500.00 ,25,25,25
BEGIN DESCRIPTION:
30
END DESCRIPTION:
#Sta/Elev= 11
   -11.3   13.42    -1.3   13.42     -.9   13.82       0   13.82     1.7   12.72
     2.5   12.72     3.1   13.02     4.8   13.52     5.6   13.52     6.9   14.52
    16.9   14.52
#Mann= 3 , 0 , 0
   -11.3    .035       0       0    .035       0     4.8    .035       0
#XS Ineff= 2 , 0
               0      20     4.8              20
Permanent Ineff=
       F       F
#Block Obstruct= 2 , 0
                             4.8
Bank Sta=0,4.8
XS Rating Curve= 0
Exp/Cntr=.3,.1

Type RM Length L Ch R = 1 ,1475.00 ,25,25,25
BEGIN DESCRIPTION:
29.025
END DESCRIPTION:
#Sta/Elev= 17
   -10.3   14.94    -2.3   14.94      -1   14.14       0   13.74       2   12.04
     2.8   12.04     2.8   11.64     4.5   11.64     4.5   12.04     5.8   12.94
     6.5   12.94     8.1   11.64     8.4   11.64     8.6   12.04     9.1   12.04
     9.2   11.94    19.2   11.94
#Mann= 3 , 0 , 0
   -10.3    .035       0      -1    .035       0     5.8    .035       0
#XS Ineff= 2 , 0
              -1      20     5.8              20
Permanent Ineff=
       F       F
#Block Obstruct= 2 , 0
                             5.8
Bank Sta=-1,5.8
XS Rating Curve= 0
Exp/Cntr=.3,.1

Type RM Length L Ch R = 1 ,1450.00 ,32,32,32
BEGIN DESCRIPTION:
29
END DESCRIPTION:
#Sta/Elev= 14
   -10.3    14.5    -2.3    14.5      -1    13.7       0    13.3       2    12.1
     3.7    12.1     5.7    13.3     6.4    13.3       8      12     8.3      12
     8.5    12.4       9    12.4     9.1    12.3    19.1    12.3
#Mann= 3 , 0 , 0
   -10.3    .035       0       0    .035       0     5.7    .035       0
#XS Ineff= 2 , 0
               0      20     5.7              20
Permanent Ineff=
       F       F
#Block Obstruct= 2 , 0
                             5.7
Bank Sta=0,5.7
XS Rating Curve= 0
Exp/Cntr=.3,.1

Type RM Length L Ch R = 1 ,1418.00 ,8,8,8
BEGIN DESCRIPTION:
28.018
END DESCRIPTION:
#Sta/Elev= 6
     -10   13.83       0   13.83       0   11.83     2.5   11.83     2.5   13.83
    12.5   13.83
#Mann= 3 , 0 , 0
     -10    .035       0       0    .035       0     2.5    .035       0
#XS Ineff= 2 , 0
               0      20     2.5              20
Permanent Ineff=
       F       F
#Block Obstruct= 2 , 0
                             2.5
Bank Sta=0,2.5
XS Rating Curve= 0
Exp/Cntr=.3,.1

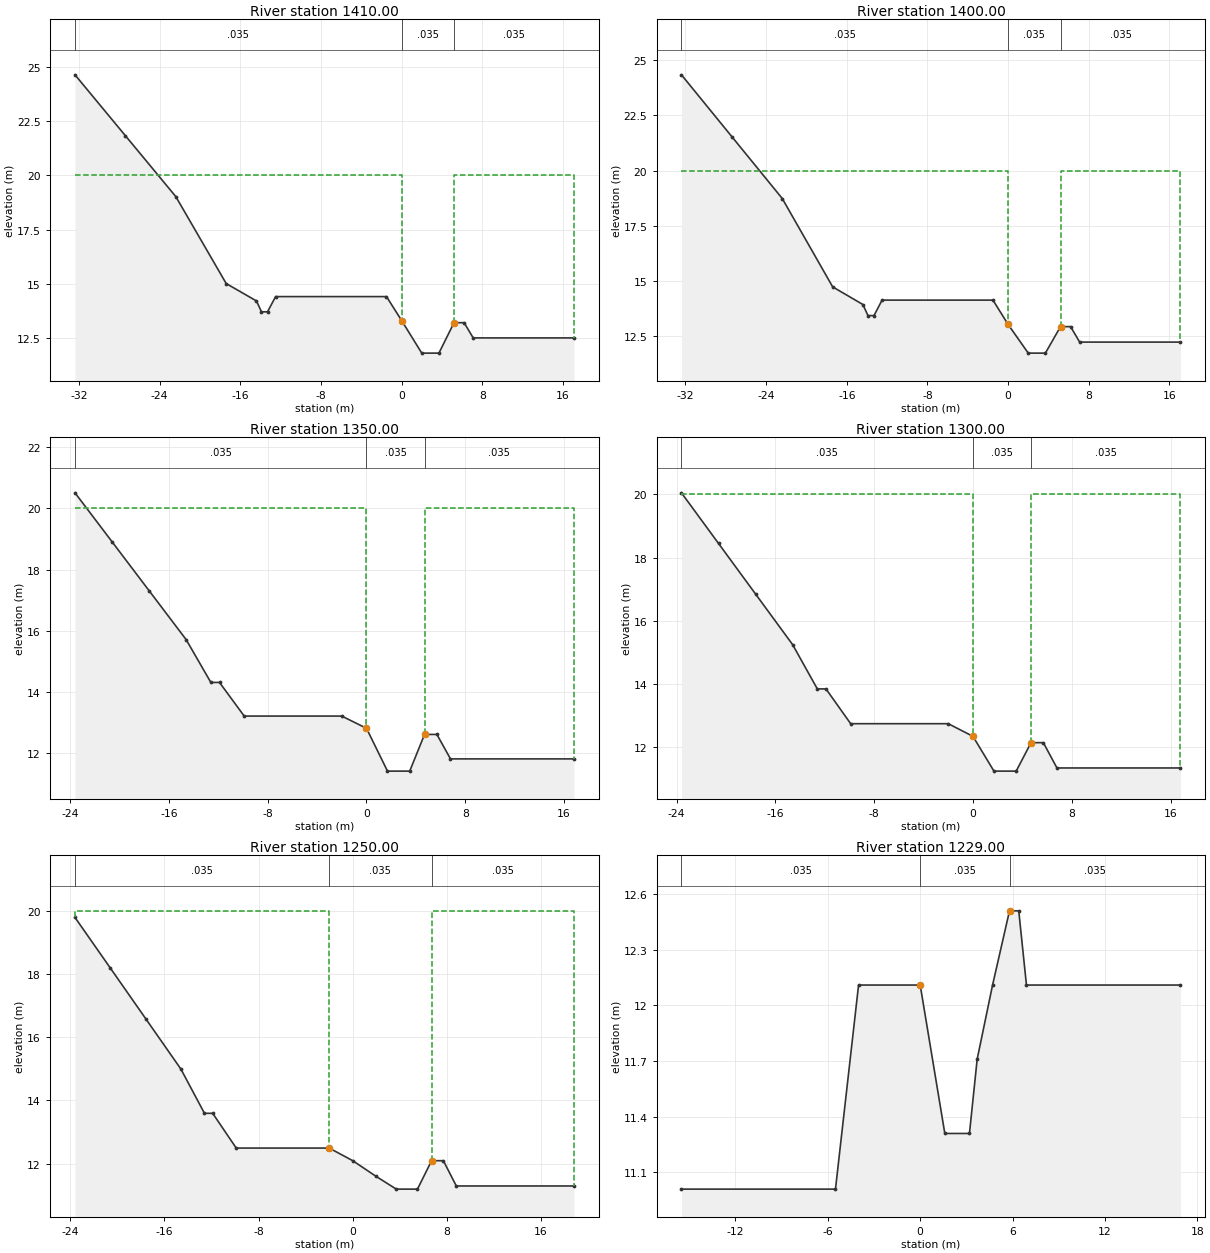
Type RM Length L Ch R = 1 ,1410.00 ,10,10,10
BEGIN DESCRIPTION:
28.01
END DESCRIPTION:
#Sta/Elev= 16
   -32.4   24.62   -27.4   21.82   -22.4   19.02   -17.4   15.02   -14.4   14.22
   -13.9   13.72   -13.3   13.72   -12.5   14.42    -1.5   14.42       0   13.32
       2   11.82     3.7   11.82     5.2   13.22     6.2   13.22     7.1   12.52
    17.1   12.52
#Mann= 3 , 0 , 0
   -32.4    .035       0       0    .035       0     5.2    .035       0
#XS Ineff= 2 , 0
               0      20     5.2              20
Permanent Ineff=
       F       F
#Block Obstruct= 2 , 0
                             5.2
Bank Sta=0,5.2
XS Rating Curve= 0
Exp/Cntr=.3,.1

Type RM Length L Ch R = 1 ,1400.00 ,50,50,50
BEGIN DESCRIPTION:
28
END DESCRIPTION:
#Sta/Elev= 16
   -32.4   24.34   -27.4   21.54   -22.4   18.74   -17.4   14.74   -14.4   13.94
   -13.9   13.44   -13.3   13.44   -12.5   14.14    -1.5   14.14       0   13.04
       2   11.74     3.7   11.74     5.2   12.94     6.2   12.94     7.1   12.24
    17.1   12.24
#Mann= 3 , 0 , 0
   -32.4    .035       0       0    .035       0     5.2    .035       0
#XS Ineff= 2 , 0
               0      20     5.2              20
Permanent Ineff=
       F       F
#Block Obstruct= 2 , 0
                             5.2
Bank Sta=0,5.2
XS Rating Curve= 0
Exp/Cntr=.3,.1

Type RM Length L Ch R = 1 ,1350.00 ,50,50,50
BEGIN DESCRIPTION:
27
END DESCRIPTION:
#Sta/Elev= 15
   -23.6   20.51   -20.6   18.91   -17.6   17.31   -14.6   15.71   -12.6   14.31
   -11.9   14.31    -9.9   13.21      -2   13.21       0   12.81     1.7   11.41
     3.5   11.41     4.7   12.61     5.7   12.61     6.8   11.81    16.8   11.81
#Mann= 3 , 0 , 0
   -23.6    .035       0       0    .035       0     4.7    .035       0
#XS Ineff= 2 , 0
               0      20     4.7              20
Permanent Ineff=
       F       F
#Block Obstruct= 2 , 0
                             4.7
Bank Sta=0,4.7
XS Rating Curve= 0
Exp/Cntr=.3,.1

Type RM Length L Ch R = 1 ,1300.00 ,50,50,50
BEGIN DESCRIPTION:
26
END DESCRIPTION:
#Sta/Elev= 15
   -23.6   20.05   -20.6   18.45   -17.6   16.85   -14.6   15.25   -12.6   13.85
   -11.9   13.85    -9.9   12.75      -2   12.75       0   12.35     1.7   11.25
     3.5   11.25     4.7   12.15     5.7   12.15     6.8   11.35    16.8   11.35
#Mann= 3 , 0 , 0
   -23.6    .035       0       0    .035       0     4.7    .035       0
#XS Ineff= 2 , 0
               0      20     4.7              20
Permanent Ineff=
       F       F
#Block Obstruct= 2 , 0
                             4.7
Bank Sta=0,4.7
XS Rating Curve= 0
Exp/Cntr=.3,.1

Type RM Length L Ch R = 1 ,1250.00 ,21,21,21
BEGIN DESCRIPTION:
25
END DESCRIPTION:
#Sta/Elev= 16
   -23.6   19.79   -20.6   18.19   -17.6   16.59   -14.6   14.99   -12.6   13.59
   -11.9   13.59    -9.9   12.49      -2   12.49       0   12.09       2   11.59
     3.7   11.19     5.5   11.19     6.7   12.09     7.7   12.09     8.8   11.29
    18.8   11.29
#Mann= 3 , 0 , 0
   -23.6    .035       0      -2    .035       0     6.7    .035       0
#XS Ineff= 2 , 0
              -2      20     6.7              20
Permanent Ineff=
       F       F
#Block Obstruct= 2 , 0
              -2             6.7
Bank Sta=-2,6.7
XS Rating Curve= 0
Exp/Cntr=.3,.1

Type RM Length L Ch R = 1 ,1229.00 ,29,29,29
BEGIN DESCRIPTION:
24.029
END DESCRIPTION:
#Sta/Elev= 12
   -15.5   11.01    -5.5   11.01      -4   12.11       0   12.11     1.6   11.31
     3.2   11.31     3.7   11.71     4.7   12.11     5.8   12.51     6.4   12.51
     6.9   12.11    16.9   12.11
#Mann= 3 , 0 , 0
   -15.5    .035       0       0    .035       0     5.8    .035       0
#XS Ineff= 2 , 0
               0      20     5.8              20
Permanent Ineff=
       F       F
#Block Obstruct= 2 , 0
                             5.8
Bank Sta=0,5.8
XS Rating Curve= 0
Exp/Cntr=.3,.1

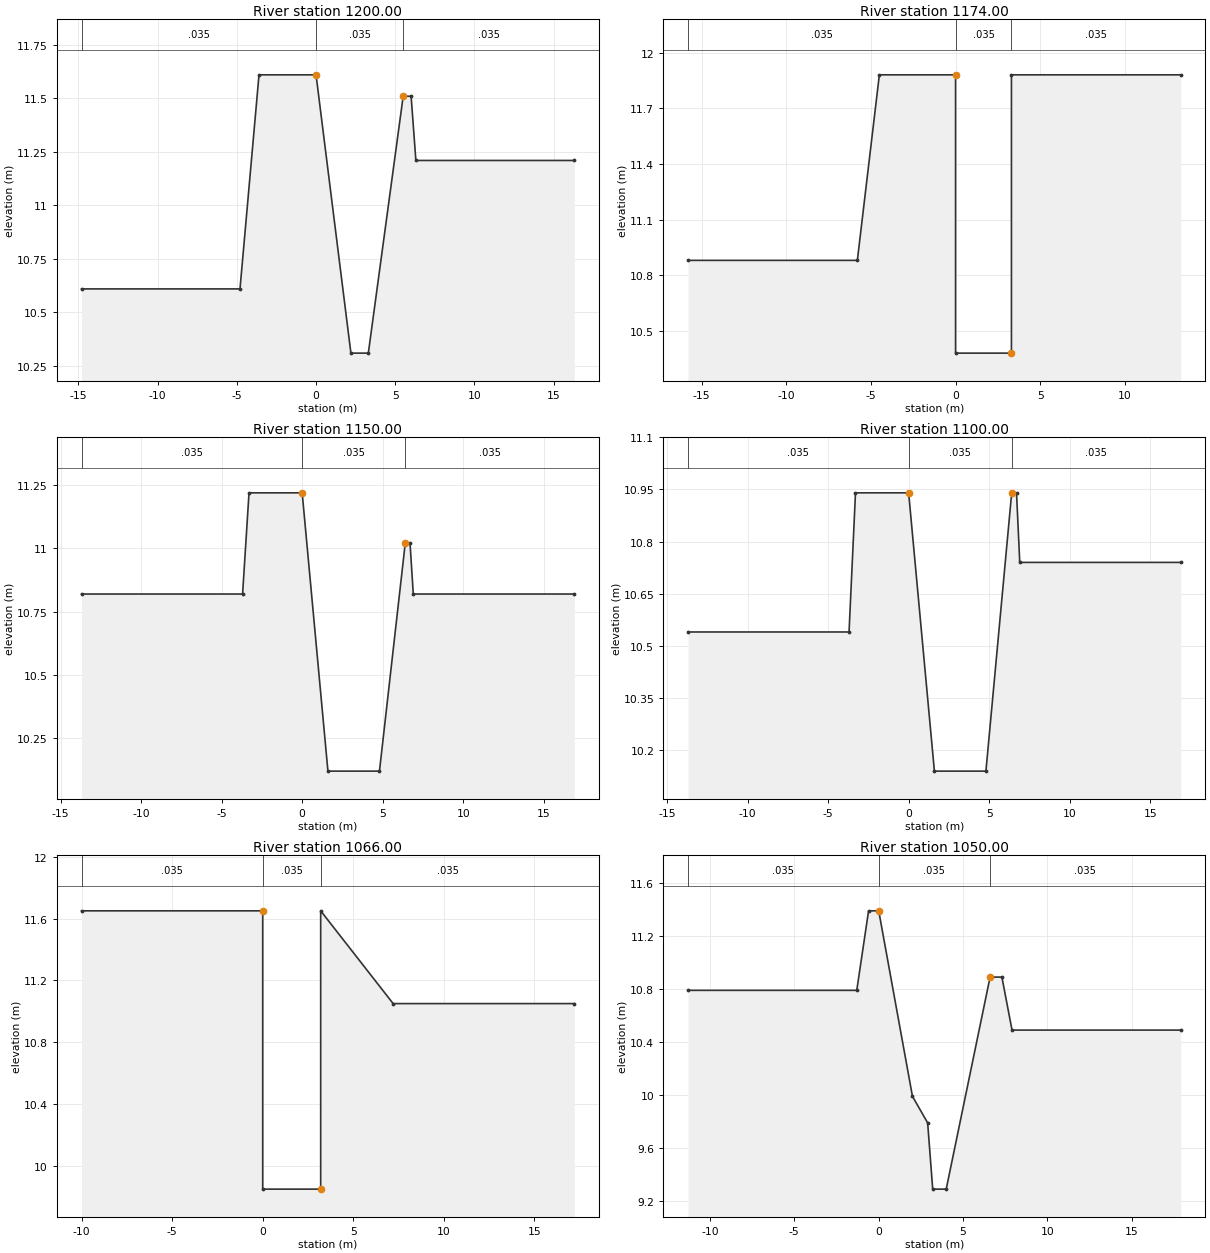
Type RM Length L Ch R = 1 ,1200.00 ,26,26,26
BEGIN DESCRIPTION:
24
END DESCRIPTION:
#Sta/Elev= 10
   -14.8   10.61    -4.8   10.61    -3.6   11.61       0   11.61     2.2   10.31
     3.3   10.31     5.5   11.51       6   11.51     6.3   11.21    16.3   11.21
#Mann= 3 , 0 , 0
   -14.8    .035       0       0    .035       0     5.5    .035       0
#XS Ineff= 2 , 0
               0      20     5.5              20
Permanent Ineff=
       F       F
#Block Obstruct= 2 , 0
                             5.5
Bank Sta=0,5.5
XS Rating Curve= 0
Exp/Cntr=.3,.1

Type RM Length L Ch R = 1 ,1174.00 ,24,24,24
BEGIN DESCRIPTION:
23.024
END DESCRIPTION:
#Sta/Elev= 8
   -15.8   10.88    -5.8   10.88    -4.5   11.88       0   11.88       0   10.38
     3.3   10.38     3.3   11.88    13.3   11.88
#Mann= 3 , 0 , 0
   -15.8    .035       0       0    .035       0     3.3    .035       0
#XS Ineff= 2 , 0
               0      20     3.3              20
Permanent Ineff=
       F       F
#Block Obstruct= 2 , 0
                             3.3
Bank Sta=0,3.3
XS Rating Curve= 0
Exp/Cntr=.3,.1

Type RM Length L Ch R = 1 ,1150.00 ,50,50,50
BEGIN DESCRIPTION:
23
END DESCRIPTION:
#Sta/Elev= 10
   -13.7   10.82    -3.7   10.82    -3.3   11.22       0   11.22     1.6   10.12
     4.8   10.12     6.4   11.02     6.7   11.02     6.9   10.82    16.9   10.82
#Mann= 3 , 0 , 0
   -13.7    .035       0       0    .035       0     6.4    .035       0
#XS Ineff= 2 , 0
               0      20     6.4              20
Permanent Ineff=
       F       F
#Block Obstruct= 2 , 0
                             6.4
Bank Sta=0,6.4
XS Rating Curve= 0
Exp/Cntr=.3,.1

Type RM Length L Ch R = 1 ,1100.00 ,34,34,34
BEGIN DESCRIPTION:
22
END DESCRIPTION:
#Sta/Elev= 10
   -13.7   10.54    -3.7   10.54    -3.3   10.94       0   10.94     1.6   10.14
     4.8   10.14     6.4   10.94     6.7   10.94     6.9   10.74    16.9   10.74
#Mann= 3 , 0 , 0
   -13.7    .035       0       0    .035       0     6.4    .035       0
#XS Ineff= 2 , 0
               0      20     6.4              20
Permanent Ineff=
       F       F
#Block Obstruct= 2 , 0
                             6.4
Bank Sta=0,6.4
XS Rating Curve= 0
Exp/Cntr=.3,.1

Type RM Length L Ch R = 1 ,1066.00 ,16,16,16
BEGIN DESCRIPTION:
21.016
END DESCRIPTION:
#Sta/Elev= 7
     -10   11.65       0   11.65       0    9.85     3.2    9.85     3.2   11.65
     7.2   11.05    17.2   11.05
#Mann= 3 , 0 , 0
     -10    .035       0       0    .035       0     3.2    .035       0
#XS Ineff= 2 , 0
               0      20     3.2              20
Permanent Ineff=
       F       F
#Block Obstruct= 2 , 0
                             3.2
Bank Sta=0,3.2
XS Rating Curve= 0
Exp/Cntr=.3,.1

Type RM Length L Ch R = 1 ,1050.00 ,50,50,50
BEGIN DESCRIPTION:
21
END DESCRIPTION:
#Sta/Elev= 12
   -11.3   10.79    -1.3   10.79     -.6   11.39       0   11.39       2    9.99
     2.9    9.79     3.2    9.29       4    9.29     6.6   10.89     7.3   10.89
     7.9   10.49    17.9   10.49
#Mann= 3 , 0 , 0
   -11.3    .035       0       0    .035       0     6.6    .035       0
#XS Ineff= 2 , 0
               0      20     6.6              20
Permanent Ineff=
       F       F
#Block Obstruct= 2 , 0
                             6.6
Bank Sta=0,6.6
XS Rating Curve= 0
Exp/Cntr=.3,.1

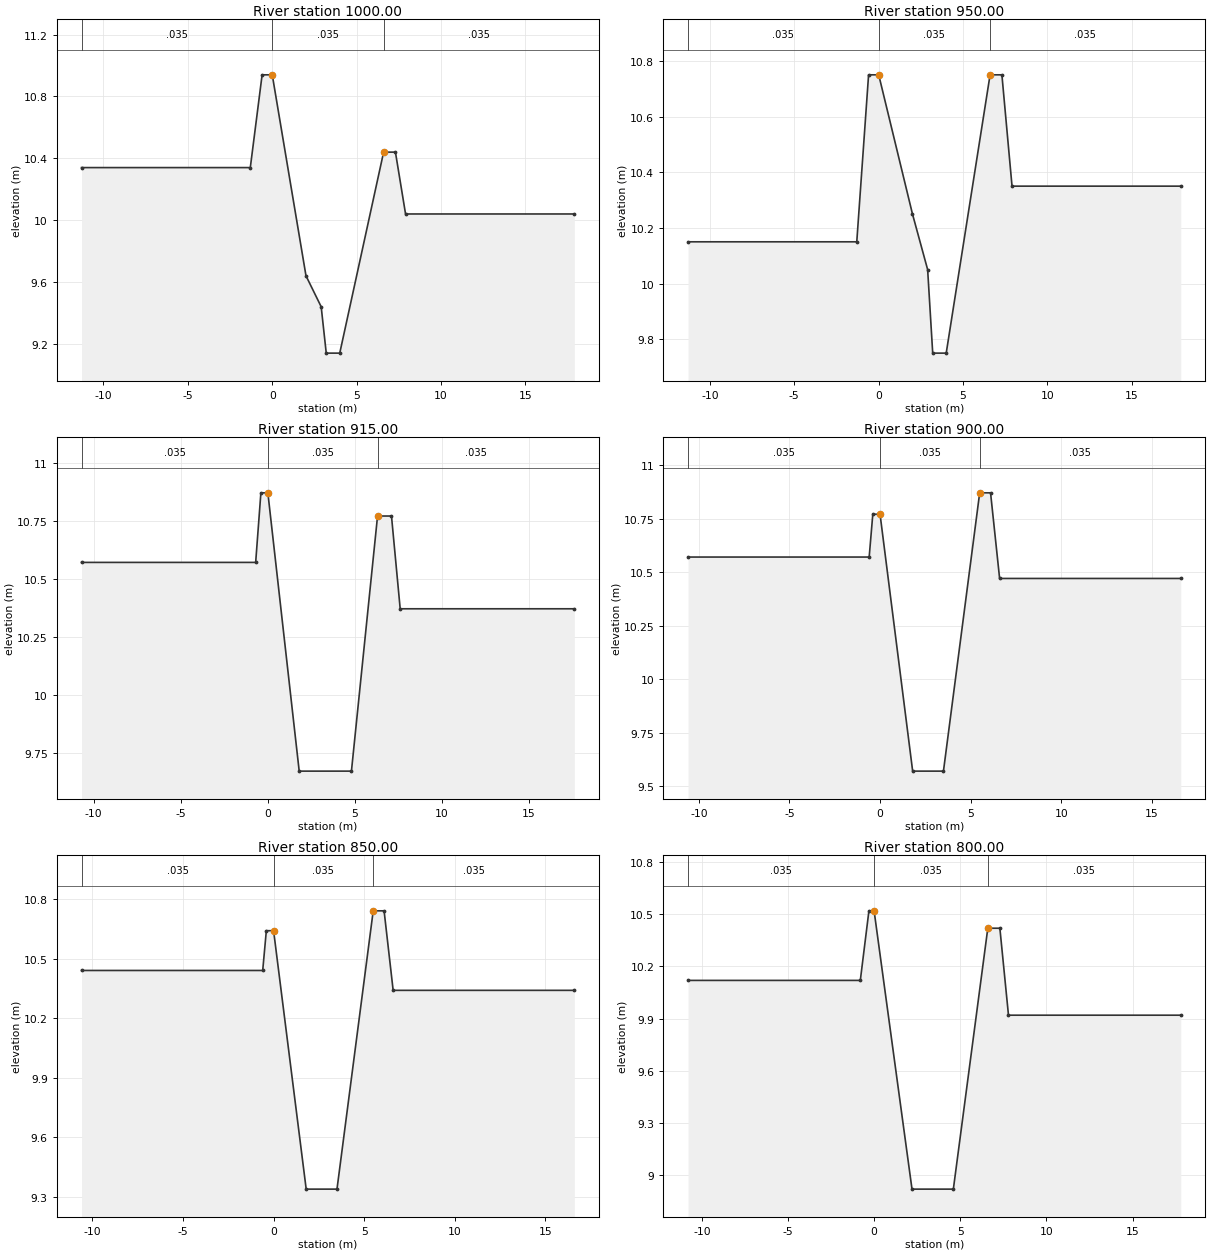
Type RM Length L Ch R = 1 ,1000.00 ,50,50,50
BEGIN DESCRIPTION:
20
END DESCRIPTION:
#Sta/Elev= 12
   -11.3   10.34    -1.3   10.34     -.6   10.94       0   10.94       2    9.64
     2.9    9.44     3.2    9.14       4    9.14     6.6   10.44     7.3   10.44
     7.9   10.04    17.9   10.04
#Mann= 3 , 0 , 0
   -11.3    .035       0       0    .035       0     6.6    .035       0
#XS Ineff= 2 , 0
               0      20     6.6              20
Permanent Ineff=
       F       F
#Block Obstruct= 2 , 0
                             6.6
Bank Sta=0,6.6
XS Rating Curve= 0
Exp/Cntr=.3,.1

Type RM Length L Ch R = 1 ,950.00  ,35,35,35
BEGIN DESCRIPTION:
19
END DESCRIPTION:
#Sta/Elev= 12
   -11.3   10.15    -1.3   10.15     -.6   10.75       0   10.75       2   10.25
     2.9   10.05     3.2    9.75       4    9.75     6.6   10.75     7.3   10.75
     7.9   10.35    17.9   10.35
#Mann= 3 , 0 , 0
   -11.3    .035       0       0    .035       0     6.6    .035       0
#XS Ineff= 2 , 0
               0      20     6.6              20
Permanent Ineff=
       F       F
#Block Obstruct= 2 , 0
                             6.6
Bank Sta=0,6.6
XS Rating Curve= 0
Exp/Cntr=.3,.1

Type RM Length L Ch R = 1 ,915.00  ,15,15,15
BEGIN DESCRIPTION:
18.015
END DESCRIPTION:
#Sta/Elev= 10
   -10.7   10.57     -.7   10.57     -.4   10.87       0   10.87     1.8    9.67
     4.8    9.67     6.3   10.77     7.1   10.77     7.6   10.37    17.6   10.37
#Mann= 3 , 0 , 0
   -10.7    .035       0       0    .035       0     6.3    .035       0
#XS Ineff= 2 , 0
               0      20     6.3              20
Permanent Ineff=
       F       F
#Block Obstruct= 2 , 0
                             6.3
Bank Sta=0,6.3
XS Rating Curve= 0
Exp/Cntr=.3,.1

Type RM Length L Ch R = 1 ,900.00  ,50,50,50
BEGIN DESCRIPTION:
18
END DESCRIPTION:
#Sta/Elev= 10
   -10.6   10.57     -.6   10.57     -.4   10.77       0   10.77     1.8    9.57
     3.5    9.57     5.5   10.87     6.1   10.87     6.6   10.47    16.6   10.47
#Mann= 3 , 0 , 0
   -10.6    .035       0       0    .035       0     5.5    .035       0
#XS Ineff= 2 , 0
               0      20     5.5              20
Permanent Ineff=
       F       F
#Block Obstruct= 2 , 0
                             5.5
Bank Sta=0,5.5
XS Rating Curve= 0
Exp/Cntr=.3,.1

Type RM Length L Ch R = 1 ,850.00  ,50,50,50
BEGIN DESCRIPTION:
17
END DESCRIPTION:
#Sta/Elev= 10
   -10.6   10.44     -.6   10.44     -.4   10.64       0   10.64     1.8    9.34
     3.5    9.34     5.5   10.74     6.1   10.74     6.6   10.34    16.6   10.34
#Mann= 3 , 0 , 0
   -10.6    .035       0       0    .035       0     5.5    .035       0
#XS Ineff= 2 , 0
               0      20     5.5              20
Permanent Ineff=
       F       F
#Block Obstruct= 2 , 0
                             5.5
Bank Sta=0,5.5
XS Rating Curve= 0
Exp/Cntr=.3,.1

Type RM Length L Ch R = 1 ,800.00  ,6,6,6
BEGIN DESCRIPTION:
16
END DESCRIPTION:
#Sta/Elev= 10
   -10.8   10.12     -.8   10.12     -.3   10.52       0   10.52     2.2    8.92
     4.6    8.92     6.6   10.42     7.3   10.42     7.8    9.92    17.8    9.92
#Mann= 3 , 0 , 0
   -10.8    .035       0       0    .035       0     6.6    .035       0
#XS Ineff= 2 , 0
               0      20     6.6              20
Permanent Ineff=
       F       F
#Block Obstruct= 2 , 0
                             6.6
Bank Sta=0,6.6
XS Rating Curve= 0
Exp/Cntr=.3,.1

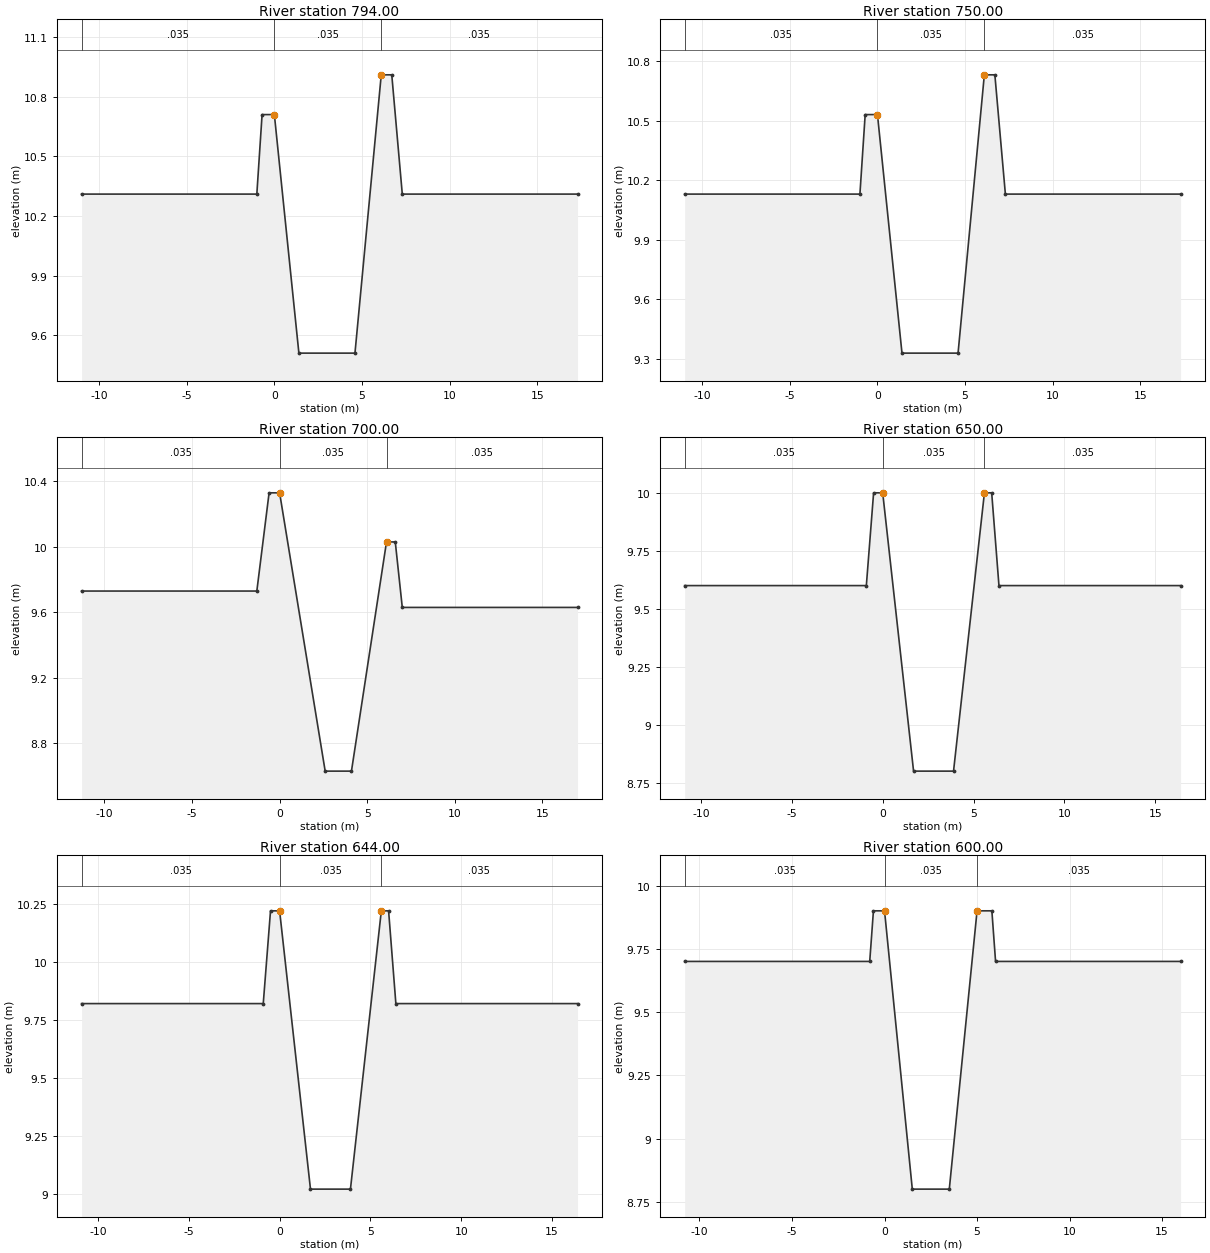
Type RM Length L Ch R = 1 ,794.00  ,44,44,44
BEGIN DESCRIPTION:
15.044
END DESCRIPTION:
#Sta/Elev= 10
     -11   10.31      -1   10.31     -.7   10.71       0   10.71     1.4    9.51
     4.6    9.51     6.1   10.91     6.7   10.91     7.3   10.31    17.3   10.31
#Mann= 3 , 0 , 0
     -11    .035       0       0    .035       0     6.1    .035       0
#XS Ineff= 2 , 0
               0      20     6.1              20
Permanent Ineff=
       F       F
#Block Obstruct= 2 , 0
                             6.1
Bank Sta=0,6.1
XS Rating Curve= 0
Exp/Cntr=.3,.1

Type RM Length L Ch R = 1 ,750.00  ,50,50,50
BEGIN DESCRIPTION:
15
END DESCRIPTION:
#Sta/Elev= 10
     -11   10.13      -1   10.13     -.7   10.53       0   10.53     1.4    9.33
     4.6    9.33     6.1   10.73     6.7   10.73     7.3   10.13    17.3   10.13
#Mann= 3 , 0 , 0
     -11    .035       0       0    .035       0     6.1    .035       0
#XS Ineff= 2 , 0
               0      20     6.1              20
Permanent Ineff=
       F       F
#Block Obstruct= 2 , 0
                             6.1
Bank Sta=0,6.1
XS Rating Curve= 0
Exp/Cntr=.3,.1

Type RM Length L Ch R = 1 ,700.00  ,50,50,50
BEGIN DESCRIPTION:
14
END DESCRIPTION:
#Sta/Elev= 10
   -11.3    9.73    -1.3    9.73     -.6   10.33       0   10.33     2.6    8.63
     4.1    8.63     6.1   10.03     6.6   10.03       7    9.63      17    9.63
#Mann= 3 , 0 , 0
   -11.3    .035       0       0    .035       0     6.1    .035       0
#XS Ineff= 2 , 0
               0      20     6.1              20
Permanent Ineff=
       F       F
#Block Obstruct= 2 , 0
                             6.1
Bank Sta=0,6.1
XS Rating Curve= 0
Exp/Cntr=.3,.1

Type RM Length L Ch R = 1 ,650.00  ,6,6,6
BEGIN DESCRIPTION:
13
END DESCRIPTION:
#Sta/Elev= 10
   -10.9     9.6     -.9     9.6     -.5      10       0      10     1.7     8.8
     3.9     8.8     5.6      10       6      10     6.4     9.6    16.4     9.6
#Mann= 3 , 0 , 0
   -10.9    .035       0       0    .035       0     5.6    .035       0
#XS Ineff= 2 , 0
               0      20     5.6              20
Permanent Ineff=
       F       F
#Block Obstruct= 2 , 0
                             5.6
Bank Sta=0,5.6
XS Rating Curve= 0
Exp/Cntr=.3,.1

Type RM Length L Ch R = 1 ,644.00  ,44,44,44
BEGIN DESCRIPTION:
12.044
END DESCRIPTION:
#Sta/Elev= 10
   -10.9    9.82     -.9    9.82     -.5   10.22       0   10.22     1.7    9.02
     3.9    9.02     5.6   10.22       6   10.22     6.4    9.82    16.4    9.82
#Mann= 3 , 0 , 0
   -10.9    .035       0       0    .035       0     5.6    .035       0
#XS Ineff= 2 , 0
               0      20     5.6              20
Permanent Ineff=
       F       F
#Block Obstruct= 2 , 0
                             5.6
Bank Sta=0,5.6
XS Rating Curve= 0
Exp/Cntr=.3,.1

Type RM Length L Ch R = 1 ,600.00  ,50,50,50
BEGIN DESCRIPTION:
12
END DESCRIPTION:
#Sta/Elev= 10
   -10.8     9.7     -.8     9.7     -.6     9.9       0     9.9     1.5     8.8
     3.5     8.8       5     9.9     5.8     9.9       6     9.7      16     9.7
#Mann= 3 , 0 , 0
   -10.8    .035       0       0    .035       0       5    .035       0
#XS Ineff= 2 , 0
               0      20       5              20
Permanent Ineff=
       F       F
#Block Obstruct= 2 , 0
                               5
Bank Sta=0,5
XS Rating Curve= 0
Exp/Cntr=.3,.1

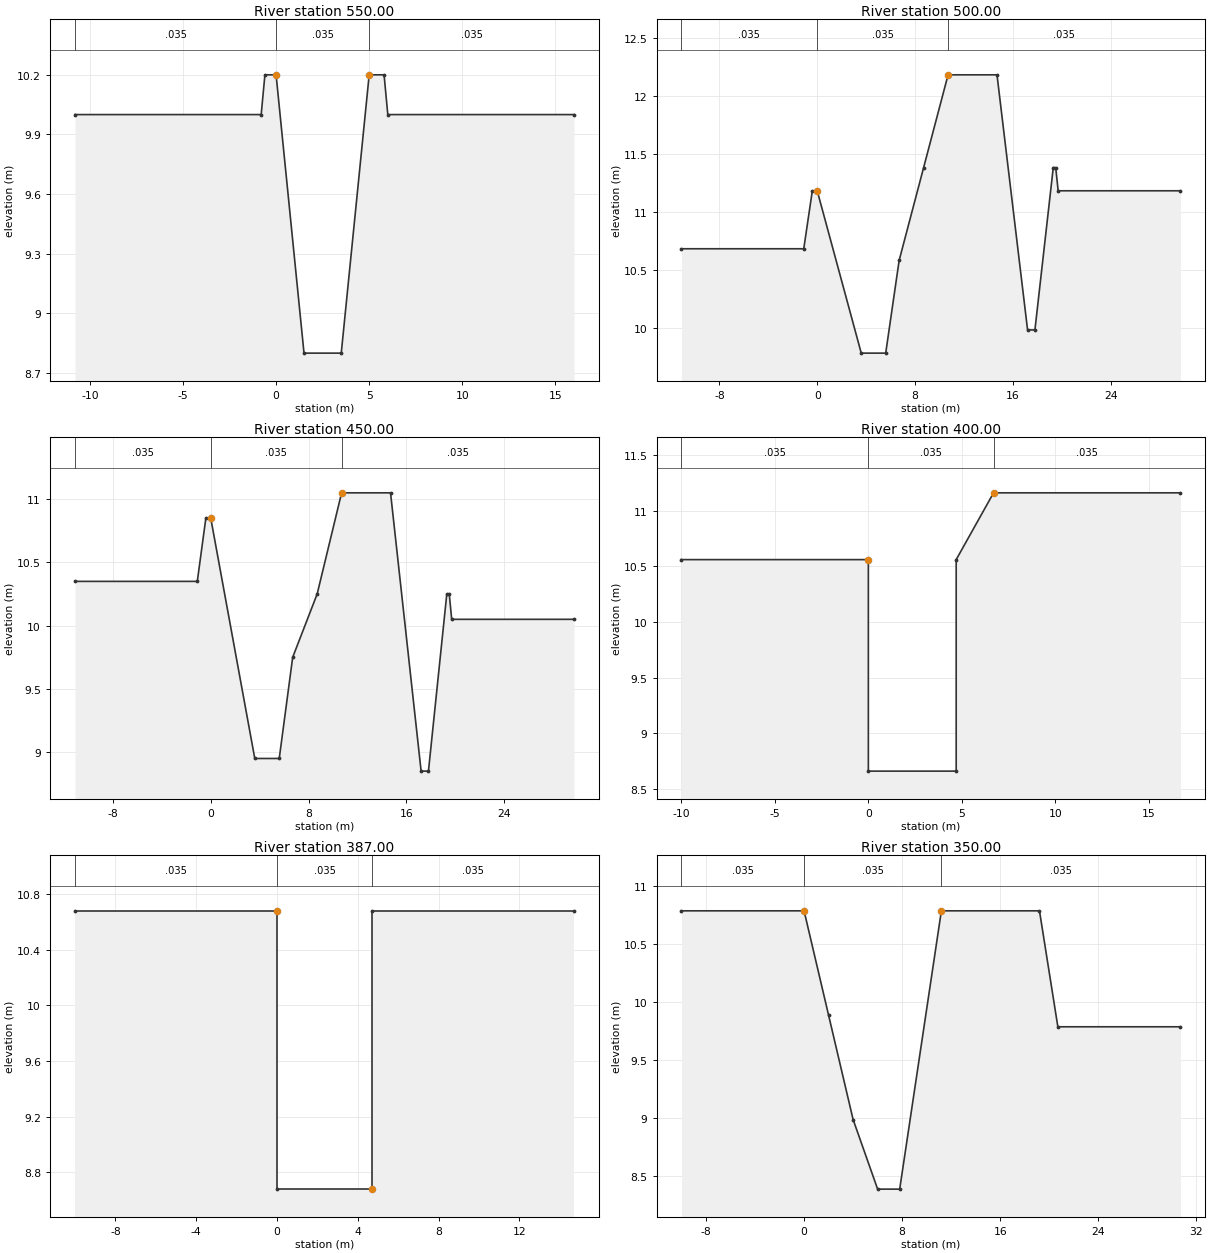
Type RM Length L Ch R = 1 ,550.00  ,50,50,50
BEGIN DESCRIPTION:
11
END DESCRIPTION:
#Sta/Elev= 10
   -10.8      10     -.8      10     -.6    10.2       0    10.2     1.5     8.8
     3.5     8.8       5    10.2     5.8    10.2       6      10      16      10
#Mann= 3 , 0 , 0
   -10.8    .035       0       0    .035       0       5    .035       0
#XS Ineff= 2 , 0
               0      20       5              20
Permanent Ineff=
       F       F
#Block Obstruct= 2 , 0
                               5
Bank Sta=0,5
XS Rating Curve= 0
Exp/Cntr=.3,.1

Type RM Length L Ch R = 1 ,500.00  ,50,50,50
BEGIN DESCRIPTION:
10
END DESCRIPTION:
#Sta/Elev= 16
   -11.1   10.68    -1.1   10.68     -.4   11.18       0   11.18     3.6    9.78
     5.6    9.78     6.7   10.58     8.7   11.38    10.7   12.18    14.7   12.18
    17.2    9.98    17.8    9.98    19.3   11.38    19.5   11.38    19.7   11.18
    29.7   11.18
#Mann= 3 , 0 , 0
   -11.1    .035       0       0    .035       0    10.7    .035       0
#XS Ineff= 2 , 0
               0      20    10.7              20
Permanent Ineff=
       F       F
#Block Obstruct= 2 , 0
                            10.7
Bank Sta=0,10.7
XS Rating Curve= 0
Exp/Cntr=.3,.1

Type RM Length L Ch R = 1 ,450.00  ,50,50,50
BEGIN DESCRIPTION:
9
END DESCRIPTION:
#Sta/Elev= 16
   -11.1   10.35    -1.1   10.35     -.4   10.85       0   10.85     3.6    8.95
     5.6    8.95     6.7    9.75     8.7   10.25    10.7   11.05    14.7   11.05
    17.2    8.85    17.8    8.85    19.3   10.25    19.5   10.25    19.7   10.05
    29.7   10.05
#Mann= 3 , 0 , 0
   -11.1    .035       0       0    .035       0    10.7    .035       0
#XS Ineff= 2 , 0
               0      20    10.7              20
Permanent Ineff=
       F       F
#Block Obstruct= 2 , 0
                            10.7
Bank Sta=0,10.7
XS Rating Curve= 0
Exp/Cntr=.3,.1

Type RM Length L Ch R = 1 ,400.00  ,13,13,13
BEGIN DESCRIPTION:
8
END DESCRIPTION:
#Sta/Elev= 7
     -10   10.56       0   10.56       0    8.66     4.7    8.66     4.7   10.56
     6.7   11.16    16.7   11.16
#Mann= 3 , 0 , 0
     -10    .035       0       0    .035       0     6.7    .035       0
#XS Ineff= 2 , 0
               0      20     6.7              20
Permanent Ineff=
       F       F
#Block Obstruct= 2 , 0
                             6.7
Bank Sta=0,6.7
XS Rating Curve= 0
Exp/Cntr=.3,.1

Type RM Length L Ch R = 1 ,387.00  ,37,37,37
BEGIN DESCRIPTION:
7.037
END DESCRIPTION:
#Sta/Elev= 6
     -10   10.68       0   10.68       0    8.68     4.7    8.68     4.7   10.68
    14.7   10.68
#Mann= 3 , 0 , 0
     -10    .035       0       0    .035       0     4.7    .035       0
#XS Ineff= 2 , 0
               0      20     4.7              20
Permanent Ineff=
       F       F
#Block Obstruct= 2 , 0
                             4.7
Bank Sta=0,4.7
XS Rating Curve= 0
Exp/Cntr=.3,.1

Type RM Length L Ch R = 1 ,350.00  ,50,50,50
BEGIN DESCRIPTION:
7
END DESCRIPTION:
#Sta/Elev= 10
     -10   10.79       0   10.79       2    9.89       4    8.99       6    8.39
     7.8    8.39    11.2   10.79    19.2   10.79    20.7    9.79    30.7    9.79
#Mann= 3 , 0 , 0
     -10    .035       0       0    .035       0    11.2    .035       0
#XS Ineff= 2 , 0
               0      20    11.2              20
Permanent Ineff=
       F       F
#Block Obstruct= 2 , 0
                            11.2
Bank Sta=0,11.2
XS Rating Curve= 0
Exp/Cntr=.3,.1