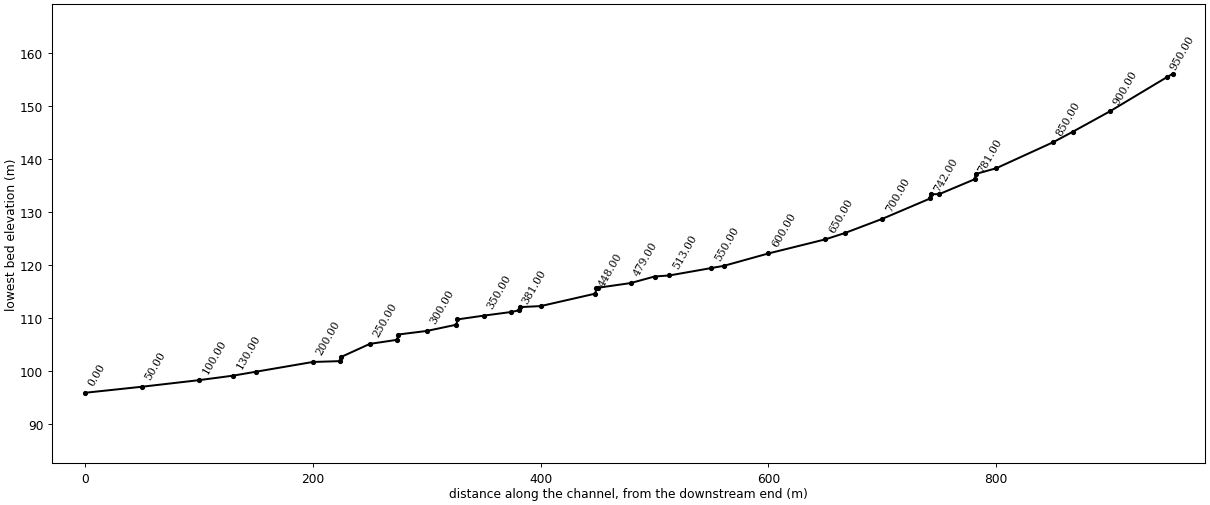
--- WIN.prj (project) ---

Proj Title=WIN
Current Plan=p01
Default Exp/Contr=.3,.1
SI Units
Geom File=g01
Flow File=f01
Plan File=p01
Y Axis Title=Elevation
X Axis Title(PF)=Main Channel Distance
X Axis Title(XS)=Station
BEGIN DESCRIPTION:
           BACK WATER COMPUTATION
      APPLICATION OF HEC-2 BY Samju Construction Engineering
      weengnang-ch: 10,20,30,50,80 yr
END DESCRIPTION:
DSS Export Rating Curves= 0
DSS Export Rating Curve Sorted= 0
DSS Export Volume Flow Curves= 0
DXF OffsetX= 0
DXF OffsetY= 0
DXF ScaleX= 1
DXF ScaleY= 10

--- WIN.p01 (plan) ---

Plan Title=Imported Plan 01
Version=Version 3.0.1  Mar 2001
Short Identifier=Imported Pla
Geom File=g01
Flow File=f01
Subcritical Flow
K Sum by GR= 0
Std Step Tol= 0.003
Critical Tol= 0.003
Num of Std Step Trials= 20
Max Error Tol= 0.1
Flow Tol Ratio= 0.001
Split Flow NTrial= 30
Split Flow Tol= 0.02
Split Flow Ratio= 0.02
Log Output Level= 0
Friction Slope Method= 1
Unsteady Friction Slope Method= 2
Parabolic Critical Depth
Global Vel Dist= 0 , 0 , 0
Global Log Level= 0
CheckData=True
Encroach Param=-1 ,0,0, 0
Computation Interval=1HOUR
Output Interval=1HOUR
Run HTab= 0
Run UNet= 0
Run PostProcess= 0
UNET Theta= 1
UNET ZTol= 0.02
UNET ZSATol= 0.1
UNET MxIter= 20
UNET MaxInSteps= 20
UNET DtIC= 0
UNET DtMin= 0
UNET MaxCRTS= 20
UNET WFStab= 2
UNET SFStab= 1
UNET WFX= 1
UNET SFX= 1
UNET Convert EG Bridges=-1
UNET Use Existing IB Tables=-1
Instantaneous Interval=1HOUR
Write IC File= 0
Write Velocity= 0
Write Detailed= 0

--- WIN.f01 (steady flow) ---

Flow Title=Imported Flow 01
Version=Version 3.0.1  Mar 2001
Number of Profiles= 5
Profile Names=10YR,20YR,30YR,50YR,80YR
River Rch & RM=RIVER-1,Reach-1         ,955.00
    9.08   10.01   10.55   11.23   11.86
Boundary for River Rch & Prof#=RIVER-1,Reach-1         , 1
Up Type= 0
Dn Type= 3
Dn Slope=.13
Boundary for River Rch & Prof#=RIVER-1,Reach-1         , 2
Up Type= 0
Dn Type= 3
Dn Slope=.13
Boundary for River Rch & Prof#=RIVER-1,Reach-1         , 3
Up Type= 0
Dn Type= 3
Dn Slope=.13
Boundary for River Rch & Prof#=RIVER-1,Reach-1         , 4
Up Type= 0
Dn Type= 3
Dn Slope=.13
Boundary for River Rch & Prof#=RIVER-1,Reach-1         , 5
Up Type= 0
Dn Type= 3
Dn Slope=.13
DSS Import GetInterval= 0
DSS Import GetPeak= 0
DSS Import FillOption= 0

--- WIN.g01 (geometry) ---

Geom Title=Imported Geom 01
Version=Version 3.0.1  Mar 2001

River Reach=RIVER-1         ,Reach-1
Reach XY= 2
              .5             .95              .5             .05

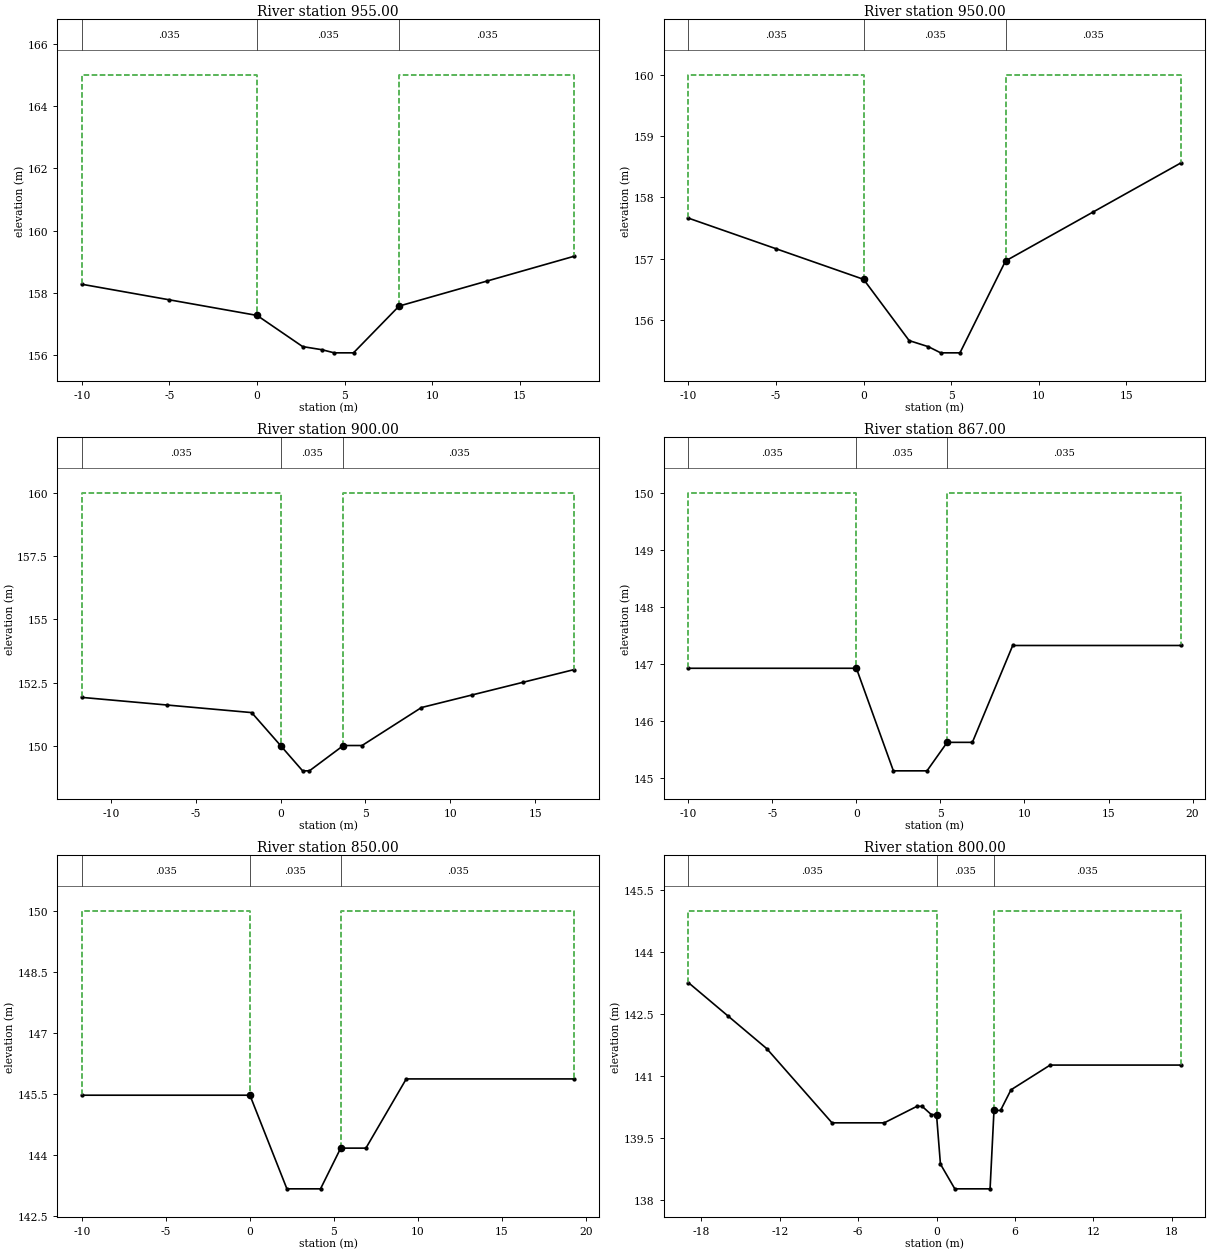
Type RM Length L Ch R = 1 ,955.00  ,5,5,5
BEGIN DESCRIPTION:
19.005
END DESCRIPTION:
#Sta/Elev= 10
     -10  158.28      -5  157.78       0  157.28     2.6  156.28     3.7  156.18
     4.4  156.08     5.5  156.08     8.1  157.58    13.1  158.38    18.1  159.18
#Mann= 3 , 0 , 0
     -10    .035       0       0    .035       0     8.1    .035       0
#XS Ineff= 2 , 0
               0     165     8.1             165
Permanent Ineff=
       F       F
#Block Obstruct= 2 , 0
                             8.1
Bank Sta=0,8.1
XS Rating Curve= 0
Exp/Cntr=.3,.1

Type RM Length L Ch R = 1 ,950.00  ,50,50,50
BEGIN DESCRIPTION:
19
END DESCRIPTION:
#Sta/Elev= 10
     -10  157.66      -5  157.16       0  156.66     2.6  155.66     3.7  155.56
     4.4  155.46     5.5  155.46     8.1  156.96    13.1  157.76    18.1  158.56
#Mann= 3 , 0 , 0
     -10    .035       0       0    .035       0     8.1    .035       0
#XS Ineff= 2 , 0
               0     160     8.1             160
Permanent Ineff=
       F       F
#Block Obstruct= 2 , 0
                             8.1
Bank Sta=0,8.1
XS Rating Curve= 0
Exp/Cntr=.3,.1

Type RM Length L Ch R = 1 ,900.00  ,33,33,33
BEGIN DESCRIPTION:
18
END DESCRIPTION:
#Sta/Elev= 12
   -11.7  151.92    -6.7  151.62    -1.7  151.32       0  150.02     1.3  149.02
     1.7  149.02     3.7  150.02     4.8  150.02     8.3  151.52    11.3  152.02
    14.3  152.52    17.3  153.02
#Mann= 3 , 0 , 0
   -11.7    .035       0       0    .035       0     3.7    .035       0
#XS Ineff= 2 , 0
               0     160     3.7             160
Permanent Ineff=
       F       F
#Block Obstruct= 2 , 0
                             3.7
Bank Sta=0,3.7
XS Rating Curve= 0
Exp/Cntr=.3,.1

Type RM Length L Ch R = 1 ,867.00  ,17,17,17
BEGIN DESCRIPTION:
17.017
END DESCRIPTION:
#Sta/Elev= 8
     -10  146.92       0  146.92     2.2  145.12     4.2  145.12     5.4  145.62
     6.9  145.62     9.3  147.32    19.3  147.32
#Mann= 3 , 0 , 0
     -10    .035       0       0    .035       0     5.4    .035       0
#XS Ineff= 2 , 0
               0     150     5.4             150
Permanent Ineff=
       F       F
#Block Obstruct= 2 , 0
                             5.4
Bank Sta=0,5.4
XS Rating Curve= 0
Exp/Cntr=.3,.1

Type RM Length L Ch R = 1 ,850.00  ,50,50,50
BEGIN DESCRIPTION:
17
END DESCRIPTION:
#Sta/Elev= 8
     -10  145.47       0  145.47     2.2  143.17     4.2  143.17     5.4  144.17
     6.9  144.17     9.3  145.87    19.3  145.87
#Mann= 3 , 0 , 0
     -10    .035       0       0    .035       0     5.4    .035       0
#XS Ineff= 2 , 0
               0     150     5.4             150
Permanent Ineff=
       F       F
#Block Obstruct= 2 , 0
                             5.4
Bank Sta=0,5.4
XS Rating Curve= 0
Exp/Cntr=.3,.1

Type RM Length L Ch R = 1 ,800.00  ,18,18,18
BEGIN DESCRIPTION:
16
END DESCRIPTION:
#Sta/Elev= 17
     -19  143.26     -16  142.46     -13  141.66      -8  139.86      -4  139.86
    -1.5  140.26    -1.1  140.26     -.4  140.06       0  140.06      .3  138.86
     1.4  138.26     4.1  138.26     4.4  140.16     4.9  140.16     5.7  140.66
     8.7  141.26    18.7  141.26
#Mann= 3 , 0 , 0
     -19    .035       0       0    .035       0     4.4    .035       0
#XS Ineff= 2 , 0
               0     145     4.4             145
Permanent Ineff=
       F       F
#Block Obstruct= 2 , 0
                             4.4
Bank Sta=0,4.4
XS Rating Curve= 0
Exp/Cntr=.3,.1

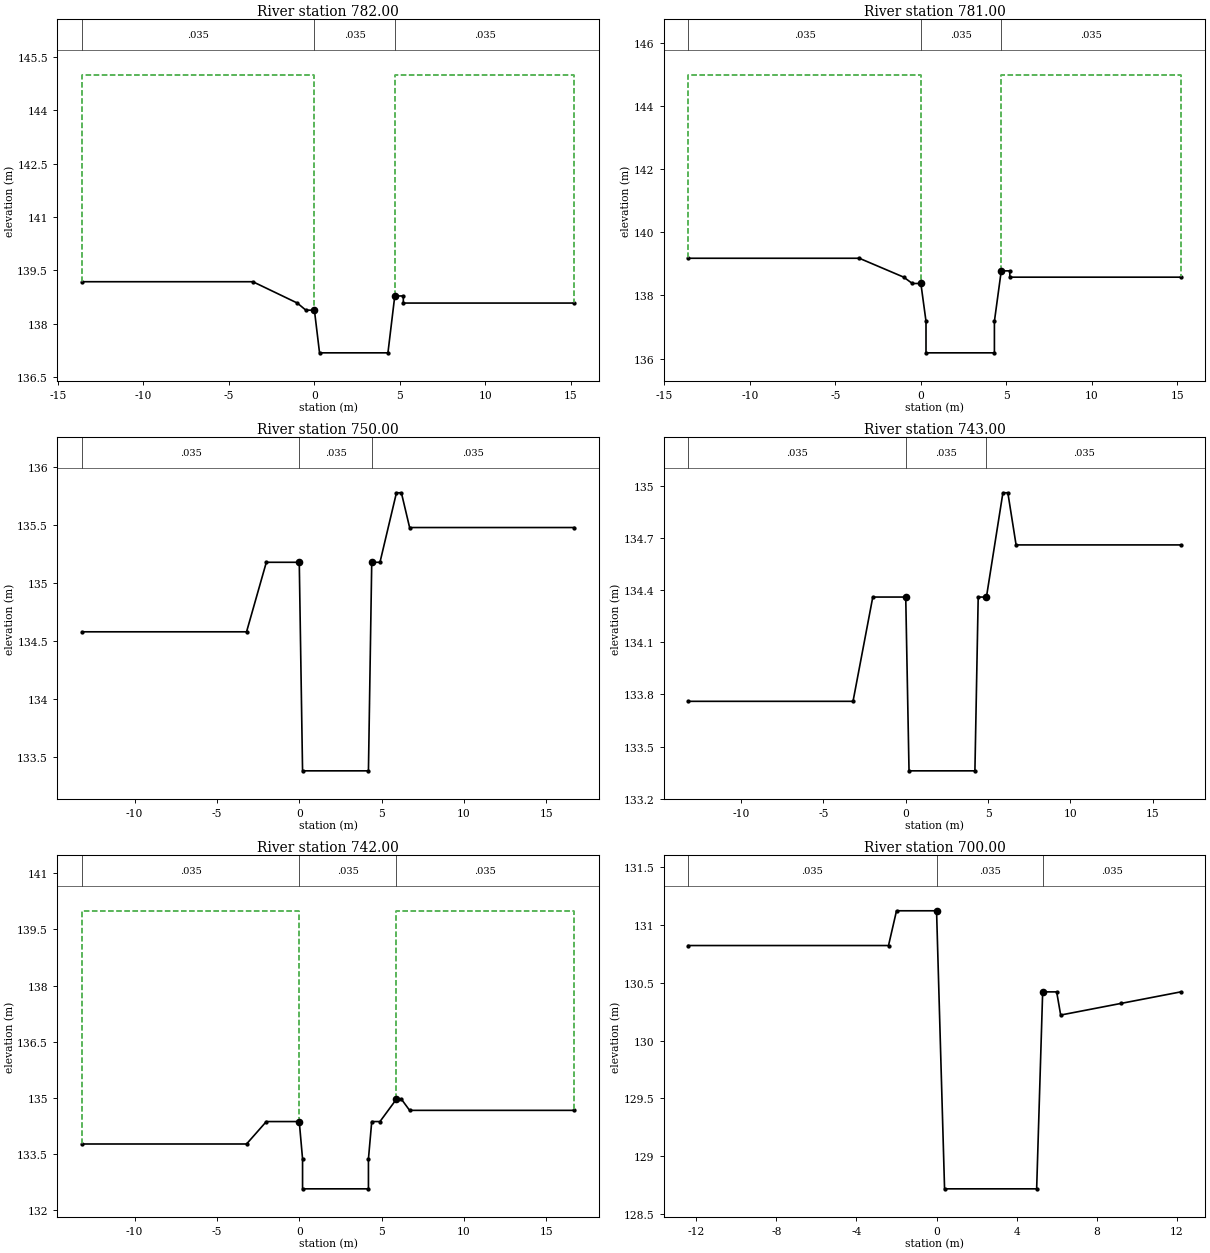
Type RM Length L Ch R = 1 ,782.00  ,1,1,1
BEGIN DESCRIPTION:
15.032
END DESCRIPTION:
#Sta/Elev= 11
   -13.6  139.18    -3.6  139.18      -1  138.58     -.5  138.38       0  138.38
      .3  137.18     4.3  137.18     4.7  138.78     5.2  138.78     5.2  138.58
    15.2  138.58
#Mann= 3 , 0 , 0
   -13.6    .035       0       0    .035       0     4.7    .035       0
#XS Ineff= 2 , 0
               0     145     4.7             145
Permanent Ineff=
       F       F
#Block Obstruct= 2 , 0
                             4.7
Bank Sta=0,4.7
XS Rating Curve= 0
Exp/Cntr=.3,.1

Type RM Length L Ch R = 1 ,781.00  ,31,31,31
BEGIN DESCRIPTION:
15.031
END DESCRIPTION:
#Sta/Elev= 13
   -13.6  139.18    -3.6  139.18      -1  138.58     -.5  138.38       0  138.38
      .3  137.18      .3  136.18     4.3  136.18     4.3  137.18     4.7  138.78
     5.2  138.78     5.2  138.58    15.2  138.58
#Mann= 3 , 0 , 0
   -13.6    .035       0       0    .035       0     4.7    .035       0
#XS Ineff= 2 , 0
               0     145     4.7             145
Permanent Ineff=
       F       F
#Block Obstruct= 2 , 0
                             4.7
Bank Sta=0,4.7
XS Rating Curve= 0
Exp/Cntr=.3,.1

Type RM Length L Ch R = 1 ,750.00  ,7,7,7
BEGIN DESCRIPTION:
15
END DESCRIPTION:
#Sta/Elev= 12
   -13.2  134.58    -3.2  134.58      -2  135.18       0  135.18      .2  133.38
     4.2  133.38     4.4  135.18     4.9  135.18     5.9  135.78     6.2  135.78
     6.7  135.48    16.7  135.48
#Mann= 3 , 0 , 0
   -13.2    .035       0       0    .035       0     4.4    .035       0
#XS Ineff= 2 , 0
               0     145     4.4             145
Permanent Ineff=
       F       F
#Block Obstruct= 2 , 0
                             4.4
Bank Sta=0,4.4
XS Rating Curve= 0
Exp/Cntr=.3,.1

Type RM Length L Ch R = 1 ,743.00  ,1,1,1
BEGIN DESCRIPTION:
14.043
END DESCRIPTION:
#Sta/Elev= 12
   -13.2  133.76    -3.2  133.76      -2  134.36       0  134.36      .2  133.36
     4.2  133.36     4.4  134.36     4.9  134.36     5.9  134.96     6.2  134.96
     6.7  134.66    16.7  134.66
#Mann= 3 , 0 , 0
   -13.2    .035       0       0    .035       0     4.9    .035       0
#XS Ineff= 2 , 0
               0     140     4.9             140
Permanent Ineff=
       F       F
#Block Obstruct= 2 , 0
                             4.9
Bank Sta=0,4.9
XS Rating Curve= 0
Exp/Cntr=.3,.1

Type RM Length L Ch R = 1 ,742.00  ,42,42,42
BEGIN DESCRIPTION:
14.042
END DESCRIPTION:
#Sta/Elev= 14
   -13.2  133.76    -3.2  133.76      -2  134.36       0  134.36      .2  133.36
      .2  132.56     4.2  132.56     4.2  133.36     4.4  134.36     4.9  134.36
     5.9  134.96     6.2  134.96     6.7  134.66    16.7  134.66
#Mann= 3 , 0 , 0
   -13.2    .035       0       0    .035       0     5.9    .035       0
#XS Ineff= 2 , 0
               0     140     5.9             140
Permanent Ineff=
       F       F
#Block Obstruct= 2 , 0
                             5.9
Bank Sta=0,5.9
XS Rating Curve= 0
Exp/Cntr=.3,.1

Type RM Length L Ch R = 1 ,700.00  ,33,33,33
BEGIN DESCRIPTION:
14
END DESCRIPTION:
#Sta/Elev= 11
   -12.4  130.82    -2.4  130.82      -2  131.12       0  131.12      .4  128.72
       5  128.72     5.3  130.42       6  130.42     6.2  130.22     9.2  130.32
    12.2  130.42
#Mann= 3 , 0 , 0
   -12.4    .035       0       0    .035       0     5.3    .035       0
#XS Ineff= 2 , 0
               0     140     5.3             140
Permanent Ineff=
       F       F
#Block Obstruct= 2 , 0
                             5.3
Bank Sta=0,5.3
XS Rating Curve= 0
Exp/Cntr=.3,.1

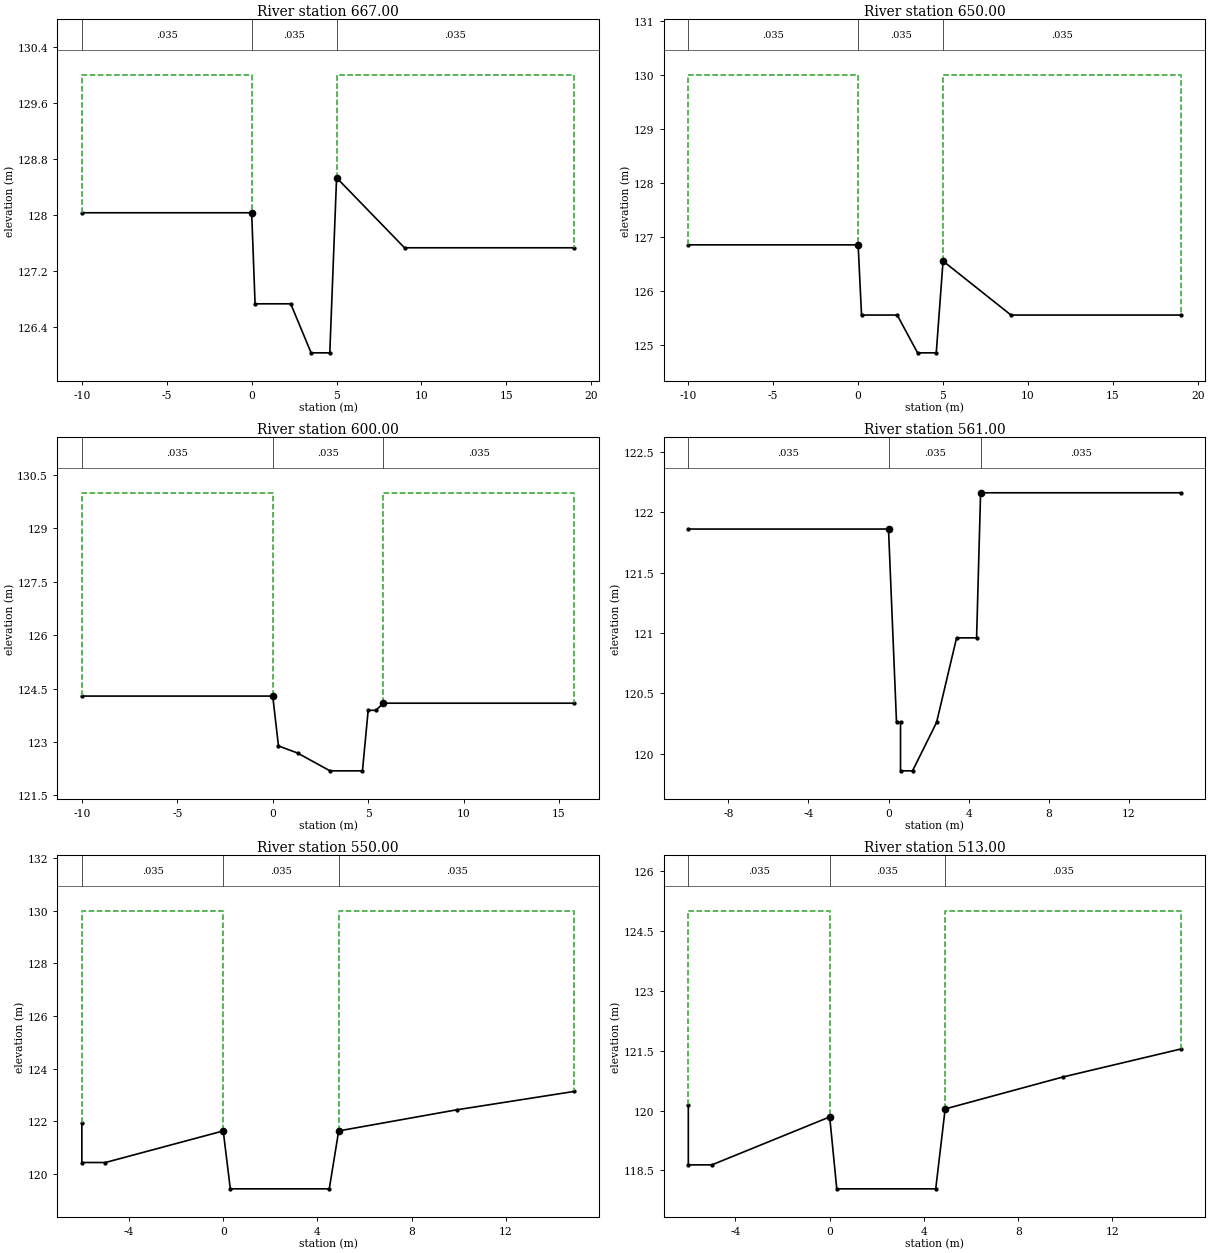
Type RM Length L Ch R = 1 ,667.00  ,17,17,17
BEGIN DESCRIPTION:
13.017
END DESCRIPTION:
#Sta/Elev= 9
     -10  128.03       0  128.03      .2  126.73     2.3  126.73     3.5  126.03
     4.6  126.03       5  128.53       9  127.53      19  127.53
#Mann= 3 , 0 , 0
     -10    .035       0       0    .035       0       5    .035       0
#XS Ineff= 2 , 0
               0     130       5             130
Permanent Ineff=
       F       F
#Block Obstruct= 2 , 0
                               5
Bank Sta=0,5
XS Rating Curve= 0
Exp/Cntr=.3,.1

Type RM Length L Ch R = 1 ,650.00  ,50,50,50
BEGIN DESCRIPTION:
13
END DESCRIPTION:
#Sta/Elev= 9
     -10  126.85       0  126.85      .2  125.55     2.3  125.55     3.5  124.85
     4.6  124.85       5  126.55       9  125.55      19  125.55
#Mann= 3 , 0 , 0
     -10    .035       0       0    .035       0       5    .035       0
#XS Ineff= 2 , 0
               0     130       5             130
Permanent Ineff=
       F       F
#Block Obstruct= 2 , 0
                               5
Bank Sta=0,5
XS Rating Curve= 0
Exp/Cntr=.3,.1

Type RM Length L Ch R = 1 ,600.00  ,39,39,39
BEGIN DESCRIPTION:
12
END DESCRIPTION:
#Sta/Elev= 10
     -10  124.29       0  124.29      .3  122.89     1.3  122.69       3  122.19
     4.7  122.19       5  123.89     5.4  123.89     5.8  124.09    15.8  124.09
#Mann= 3 , 0 , 0
     -10    .035       0       0    .035       0     5.8    .035       0
#XS Ineff= 2 , 0
               0     130     5.8             130
Permanent Ineff=
       F       F
#Block Obstruct= 2 , 0
                             5.8
Bank Sta=0,5.8
XS Rating Curve= 0
Exp/Cntr=.3,.1

Type RM Length L Ch R = 1 ,561.00  ,11,11,11
BEGIN DESCRIPTION:
11.011
END DESCRIPTION:
#Sta/Elev= 11
     -10  121.86       0  121.86      .4  120.26      .6  120.26      .6  119.86
     1.2  119.86     2.4  120.26     3.4  120.96     4.4  120.96     4.6  122.16
    14.6  122.16
#Mann= 3 , 0 , 0
     -10    .035       0       0    .035       0     4.6    .035       0
#XS Ineff= 2 , 0
               0     130     4.6             130
Permanent Ineff=
       F       F
#Block Obstruct= 2 , 0
                             4.6
Bank Sta=0,4.6
XS Rating Curve= 0
Exp/Cntr=.3,.1

Type RM Length L Ch R = 1 ,550.00  ,37,37,37
BEGIN DESCRIPTION:
11
END DESCRIPTION:
#Sta/Elev= 9
      -6  121.94      -6  120.44      -5  120.44       0  121.64      .3  119.44
     4.5  119.44     4.9  121.64     9.9  122.44    14.9  123.14
#Mann= 3 , 0 , 0
      -6    .035       0       0    .035       0     4.9    .035       0
#XS Ineff= 2 , 0
               0     130     4.9             130
Permanent Ineff=
       F       F
#Block Obstruct= 2 , 0
                             4.9
Bank Sta=0,4.9
XS Rating Curve= 0
Exp/Cntr=.3,.1

Type RM Length L Ch R = 1 ,513.00  ,13,13,13
BEGIN DESCRIPTION:
10.013
END DESCRIPTION:
#Sta/Elev= 9
      -6  120.14      -6  118.64      -5  118.64       0  119.84      .3  118.04
     4.5  118.04     4.9  120.04     9.9  120.84    14.9  121.54
#Mann= 3 , 0 , 0
      -6    .035       0       0    .035       0     4.9    .035       0
#XS Ineff= 2 , 0
               0     125     4.9             125
Permanent Ineff=
       F       F
#Block Obstruct= 2 , 0
                             4.9
Bank Sta=0,4.9
XS Rating Curve= 0
Exp/Cntr=.3,.1

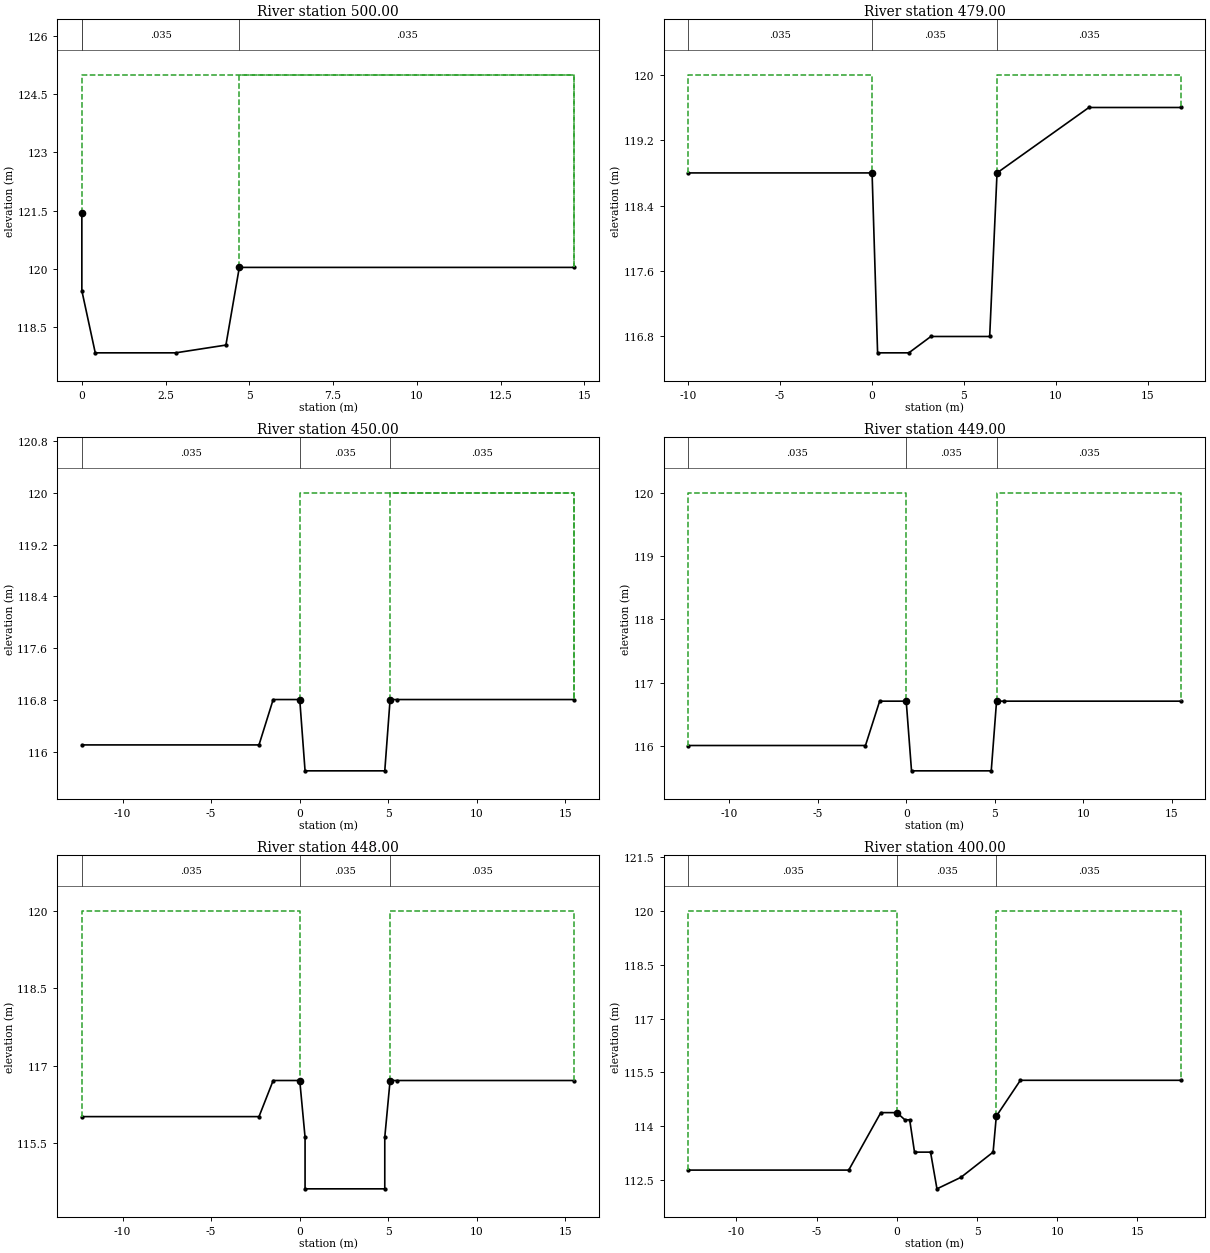
Type RM Length L Ch R = 1 ,500.00  ,21,21,21
BEGIN DESCRIPTION:
10
END DESCRIPTION:
#Sta/Elev= 7
       0  121.44       0  119.44      .4  117.84     2.8  117.84     4.3  118.04
     4.7  120.04    14.7  120.04
#Mann= 3 , 0 , 0
       0    .035       0       0    .035       0     4.7    .035       0
#XS Ineff= 2 , 0
               0     125     4.7             125
Permanent Ineff=
       F       F
#Block Obstruct= 2 , 0
                             4.7
Bank Sta=0,4.7
XS Rating Curve= 0
Exp/Cntr=.3,.1

Type RM Length L Ch R = 1 ,479.00  ,29,29,29
BEGIN DESCRIPTION:
9.029
END DESCRIPTION:
#Sta/Elev= 9
     -10   118.8       0   118.8      .3   116.6       2   116.6     3.2   116.8
     6.4   116.8     6.8   118.8    11.8   119.6    16.8   119.6
#Mann= 3 , 0 , 0
     -10    .035       0       0    .035       0     6.8    .035       0
#XS Ineff= 2 , 0
               0     120     6.8             120
Permanent Ineff=
       F       F
#Block Obstruct= 2 , 0
                             6.8
Bank Sta=0,6.8
XS Rating Curve= 0
Exp/Cntr=.3,.1

Type RM Length L Ch R = 1 ,450.00  ,1,1,1
BEGIN DESCRIPTION:
9
END DESCRIPTION:
#Sta/Elev= 9
   -12.3  116.11    -2.3  116.11    -1.5  116.81       0  116.81      .3  115.71
     4.8  115.71     5.1  116.81     5.5  116.81    15.5  116.81
#Mann= 3 , 0 , 0
   -12.3    .035       0       0    .035       0     5.1    .035       0
#XS Ineff= 2 , 0
       0       0     120     5.1       0     120
Permanent Ineff=
       F       F
#Block Obstruct= 2 , 0
                             5.1
Bank Sta=0,5.1
XS Rating Curve= 0
Exp/Cntr=.3,.1

Type RM Length L Ch R = 1 ,449.00  ,1,1,1
BEGIN DESCRIPTION:
8.049
END DESCRIPTION:
#Sta/Elev= 9
   -12.3  116.01    -2.3  116.01    -1.5  116.71       0  116.71      .3  115.61
     4.8  115.61     5.1  116.71     5.5  116.71    15.5  116.71
#Mann= 3 , 0 , 0
   -12.3    .035       0       0    .035       0     5.1    .035       0
#XS Ineff= 2 , 0
               0     120     5.1             120
Permanent Ineff=
       F       F
#Block Obstruct= 2 , 0
                             5.1
Bank Sta=0,5.1
XS Rating Curve= 0
Exp/Cntr=.3,.1

Type RM Length L Ch R = 1 ,448.00  ,48,48,48
BEGIN DESCRIPTION:
8.048
END DESCRIPTION:
#Sta/Elev= 11
   -12.3  116.01    -2.3  116.01    -1.5  116.71       0  116.71      .3  115.61
      .3  114.61     4.8  114.61     4.8  115.61     5.1  116.71     5.5  116.71
    15.5  116.71
#Mann= 3 , 0 , 0
   -12.3    .035       0       0    .035       0     5.1    .035       0
#XS Ineff= 2 , 0
               0     120     5.1             120
Permanent Ineff=
       F       F
#Block Obstruct= 2 , 0
                             5.1
Bank Sta=0,5.1
XS Rating Curve= 0
Exp/Cntr=.3,.1

Type RM Length L Ch R = 1 ,400.00  ,18,18,18
BEGIN DESCRIPTION:
8
END DESCRIPTION:
#Sta/Elev= 14
     -13  112.78      -3  112.78      -1  114.38       0  114.38      .5  114.18
      .8  114.18     1.1  113.28     2.1  113.28     2.5 112.258       4  112.58
       6  113.28     6.2  114.28     7.7  115.28    17.7  115.28
#Mann= 3 , 0 , 0
     -13    .035       0       0    .035       0     6.2    .035       0
#XS Ineff= 2 , 0
               0     120     6.2             120
Permanent Ineff=
       F       F
#Block Obstruct= 2 , 0
                             6.2
Bank Sta=0,6.2
XS Rating Curve= 0
Exp/Cntr=.3,.1

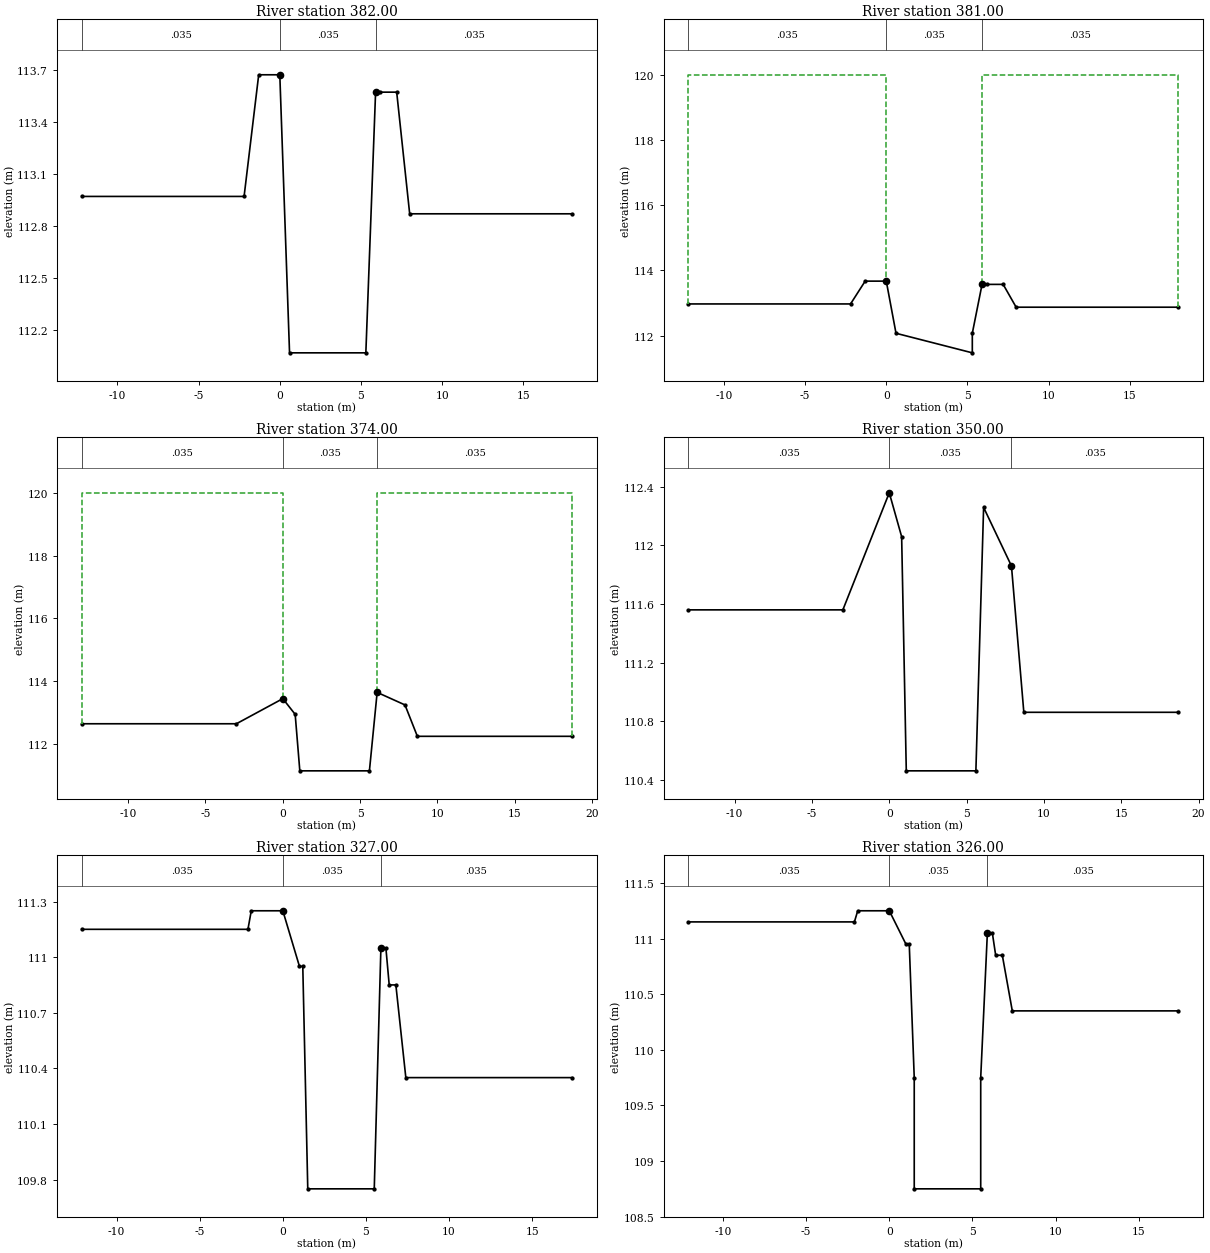
Type RM Length L Ch R = 1 ,382.00  ,1,1,1
BEGIN DESCRIPTION:
7.032
END DESCRIPTION:
#Sta/Elev= 11
   -12.2  112.97    -2.2  112.97    -1.3  113.67       0  113.67      .6  112.07
     5.3  112.07     5.9  113.57     6.2  113.57     7.2  113.57       8  112.87
      18  112.87
#Mann= 3 , 0 , 0
   -12.2    .035       0       0    .035       0     5.9    .035       0
#XS Ineff= 2 , 0
               0     120     5.9             120
Permanent Ineff=
       F       F
#Block Obstruct= 2 , 0
                             5.9
Bank Sta=0,5.9
XS Rating Curve= 0
Exp/Cntr=.3,.1

Type RM Length L Ch R = 1 ,381.00  ,7,7,7
BEGIN DESCRIPTION:
7.031
END DESCRIPTION:
#Sta/Elev= 12
   -12.2  112.97    -2.2  112.97    -1.3  113.67       0  113.67      .6  112.07
     5.3  111.47     5.3  112.07     5.9  113.57     6.2  113.57     7.2  113.57
       8  112.87      18  112.87
#Mann= 3 , 0 , 0
   -12.2    .035       0       0    .035       0     5.9    .035       0
#XS Ineff= 2 , 0
               0     120     5.9             120
Permanent Ineff=
       F       F
#Block Obstruct= 2 , 0
                             5.9
Bank Sta=0,5.9
XS Rating Curve= 0
Exp/Cntr=.3,.1

Type RM Length L Ch R = 1 ,374.00  ,24,24,24
BEGIN DESCRIPTION:
7.024
END DESCRIPTION:
#Sta/Elev= 10
     -13  112.64      -3  112.64       0  113.44      .8  112.94     1.1  111.14
     5.6  111.14     6.1  113.64     7.9  113.24     8.7  112.24    18.7  112.24
#Mann= 3 , 0 , 0
     -13    .035       0       0    .035       0     6.1    .035       0
#XS Ineff= 2 , 0
               0     120     6.1             120
Permanent Ineff=
       F       F
#Block Obstruct= 2 , 0
                             6.1
Bank Sta=0,6.1
XS Rating Curve= 0
Exp/Cntr=.3,.1

Type RM Length L Ch R = 1 ,350.00  ,23,23,23
BEGIN DESCRIPTION:
7
END DESCRIPTION:
#Sta/Elev= 10
     -13  111.56      -3  111.56       0  112.36      .8  112.06     1.1  110.46
     5.6  110.46     6.1  112.26     7.9  111.86     8.7  110.86    18.7  110.86
#Mann= 3 , 0 , 0
     -13    .035       0       0    .035       0     7.9    .035       0
#XS Ineff= 2 , 0
               0     120     7.9             120
Permanent Ineff=
       F       F
#Block Obstruct= 2 , 0
                             7.9
Bank Sta=0,7.9
XS Rating Curve= 0
Exp/Cntr=.3,.1

Type RM Length L Ch R = 1 ,327.00  ,1,1,1
BEGIN DESCRIPTION:
6.027
END DESCRIPTION:
#Sta/Elev= 14
   -12.1  111.15    -2.1  111.15    -1.9  111.25       0  111.25       1  110.95
     1.2  110.95     1.5  109.75     5.5  109.75     5.9  111.05     6.2  111.05
     6.4  110.85     6.8  110.85     7.4  110.35    17.4  110.35
#Mann= 3 , 0 , 0
   -12.1    .035       0       0    .035       0     5.9    .035       0
#XS Ineff= 2 , 0
               0     120     5.9             120
Permanent Ineff=
       F       F
#Block Obstruct= 2 , 0
                             5.9
Bank Sta=0,5.9
XS Rating Curve= 0
Exp/Cntr=.3,.1

Type RM Length L Ch R = 1 ,326.00  ,26,26,26
BEGIN DESCRIPTION:
6.026
END DESCRIPTION:
#Sta/Elev= 16
   -12.1  111.15    -2.1  111.15    -1.9  111.25       0  111.25       1  110.95
     1.2  110.95     1.5  109.75     1.5  108.75     5.5  108.75     5.5  109.75
     5.9  111.05     6.2  111.05     6.4  110.85     6.8  110.85     7.4  110.35
    17.4  110.35
#Mann= 3 , 0 , 0
   -12.1    .035       0       0    .035       0     5.9    .035       0
#XS Ineff= 2 , 0
               0     120     5.9             120
Permanent Ineff=
       F       F
#Block Obstruct= 2 , 0
                             5.9
Bank Sta=0,5.9
XS Rating Curve= 0
Exp/Cntr=.3,.1

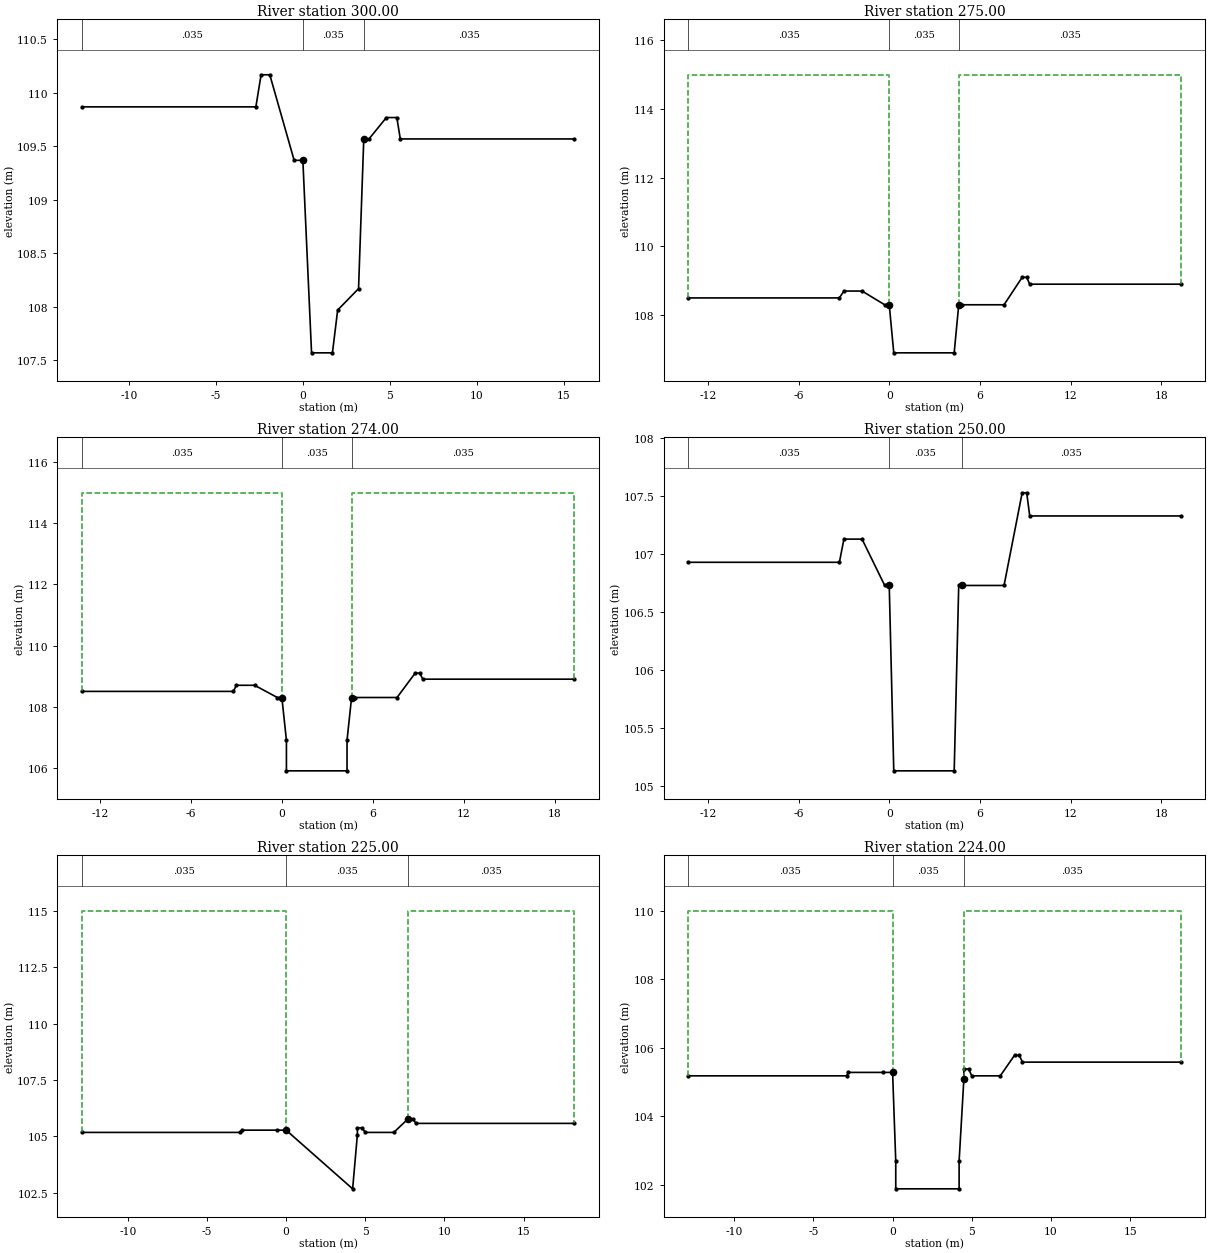
Type RM Length L Ch R = 1 ,300.00  ,25,25,25
BEGIN DESCRIPTION:
6
END DESCRIPTION:
#Sta/Elev= 16
   -12.7  109.87    -2.7  109.87    -2.4  110.17    -1.9  110.17     -.5  109.37
       0  109.37      .5  107.57     1.7  107.57       2  107.97     3.2  108.17
     3.5  109.57     3.8  109.57     4.8  109.77     5.4  109.77     5.6  109.57
    15.6  109.57
#Mann= 3 , 0 , 0
   -12.7    .035       0       0    .035       0     3.5    .035       0
#XS Ineff= 2 , 0
               0     120     3.5             120
Permanent Ineff=
       F       F
#Block Obstruct= 2 , 0
                             3.5
Bank Sta=0,3.5
XS Rating Curve= 0
Exp/Cntr=.3,.1

Type RM Length L Ch R = 1 ,275.00  ,1,1,1
BEGIN DESCRIPTION:
5.025
END DESCRIPTION:
#Sta/Elev= 15
   -13.3   108.5    -3.3   108.5      -3   108.7    -1.8   108.7     -.3   108.3
       0   108.3      .3   106.9     4.3   106.9     4.6   108.3     4.8   108.3
     7.6   108.3     8.8   109.1     9.1   109.1     9.3   108.9    19.3   108.9
#Mann= 3 , 0 , 0
   -13.3    .035       0       0    .035       0     4.6    .035       0
#XS Ineff= 2 , 0
               0     115     4.6             115
Permanent Ineff=
       F       F
#Block Obstruct= 2 , 0
                             4.6
Bank Sta=0,4.6
XS Rating Curve= 0
Exp/Cntr=.3,.1

Type RM Length L Ch R = 1 ,274.00  ,24,24,24
BEGIN DESCRIPTION:
5.024
END DESCRIPTION:
#Sta/Elev= 17
   -13.2   108.5    -3.2   108.5      -3   108.7    -1.8   108.7     -.3   108.3
       0   108.3      .3   106.9      .3   105.9     4.3   105.9     4.3   106.9
     4.6   108.3     4.8   108.3     7.6   108.3     8.8   109.1     9.1   109.1
     9.3   108.9    19.3   108.9
#Mann= 3 , 0 , 0
   -13.2    .035       0       0    .035       0     4.6    .035       0
#XS Ineff= 2 , 0
               0     115     4.6             115
Permanent Ineff=
       F       F
#Block Obstruct= 2 , 0
                             4.6
Bank Sta=0,4.6
XS Rating Curve= 0
Exp/Cntr=.3,.1

Type RM Length L Ch R = 1 ,250.00  ,25,25,25
BEGIN DESCRIPTION:
5
END DESCRIPTION:
#Sta/Elev= 15
   -13.3  106.93    -3.3  106.93      -3  107.13    -1.8  107.13     -.3  106.73
       0  106.73      .3  105.13     4.3  105.13     4.6  106.73     4.8  106.73
     7.6  106.73     8.8  107.53     9.1  107.53     9.3  107.33    19.3  107.33
#Mann= 3 , 0 , 0
   -13.3    .035       0       0    .035       0     4.8    .035       0
#XS Ineff= 2 , 0
               0     115     4.8             115
Permanent Ineff=
       F       F
#Block Obstruct= 2 , 0
                             4.8
Bank Sta=0,4.8
XS Rating Curve= 0
Exp/Cntr=.3,.1

Type RM Length L Ch R = 1 ,225.00  ,1,1,1
BEGIN DESCRIPTION:
4.025
END DESCRIPTION:
#Sta/Elev= 15
   -12.9  105.18    -2.9  105.18    -2.8  105.28     -.6  105.28       0  105.28
     4.2  102.68     4.5  105.08     4.5  105.38     4.8  105.38       5  105.18
     6.8  105.18     7.7  105.78       8  105.78     8.2  105.58    18.2  105.58
#Mann= 3 , 0 , 0
   -12.9    .035       0       0    .035       0     7.7    .035       0
#XS Ineff= 2 , 0
               0     115     7.7             115
Permanent Ineff=
       F       F
#Block Obstruct= 2 , 0
                             7.7
Bank Sta=0,7.7
XS Rating Curve= 0
Exp/Cntr=.3,.1

Type RM Length L Ch R = 1 ,224.00  ,24,24,24
BEGIN DESCRIPTION:
4.024
END DESCRIPTION:
#Sta/Elev= 18
   -12.9  105.18    -2.9  105.18    -2.8  105.28     -.6  105.28       0  105.28
      .2  102.68      .2  101.88     4.2  101.88     4.2  102.68     4.5  105.08
     4.5  105.38     4.8  105.38       5  105.18     6.8  105.18     7.7  105.78
       8  105.78     8.2  105.58    18.2  105.58
#Mann= 3 , 0 , 0
   -12.9    .035       0       0    .035       0     4.5    .035       0
#XS Ineff= 2 , 0
               0     110     4.5             110
Permanent Ineff=
       F       F
#Block Obstruct= 2 , 0
                             4.5
Bank Sta=0,4.5
XS Rating Curve= 0
Exp/Cntr=.3,.1

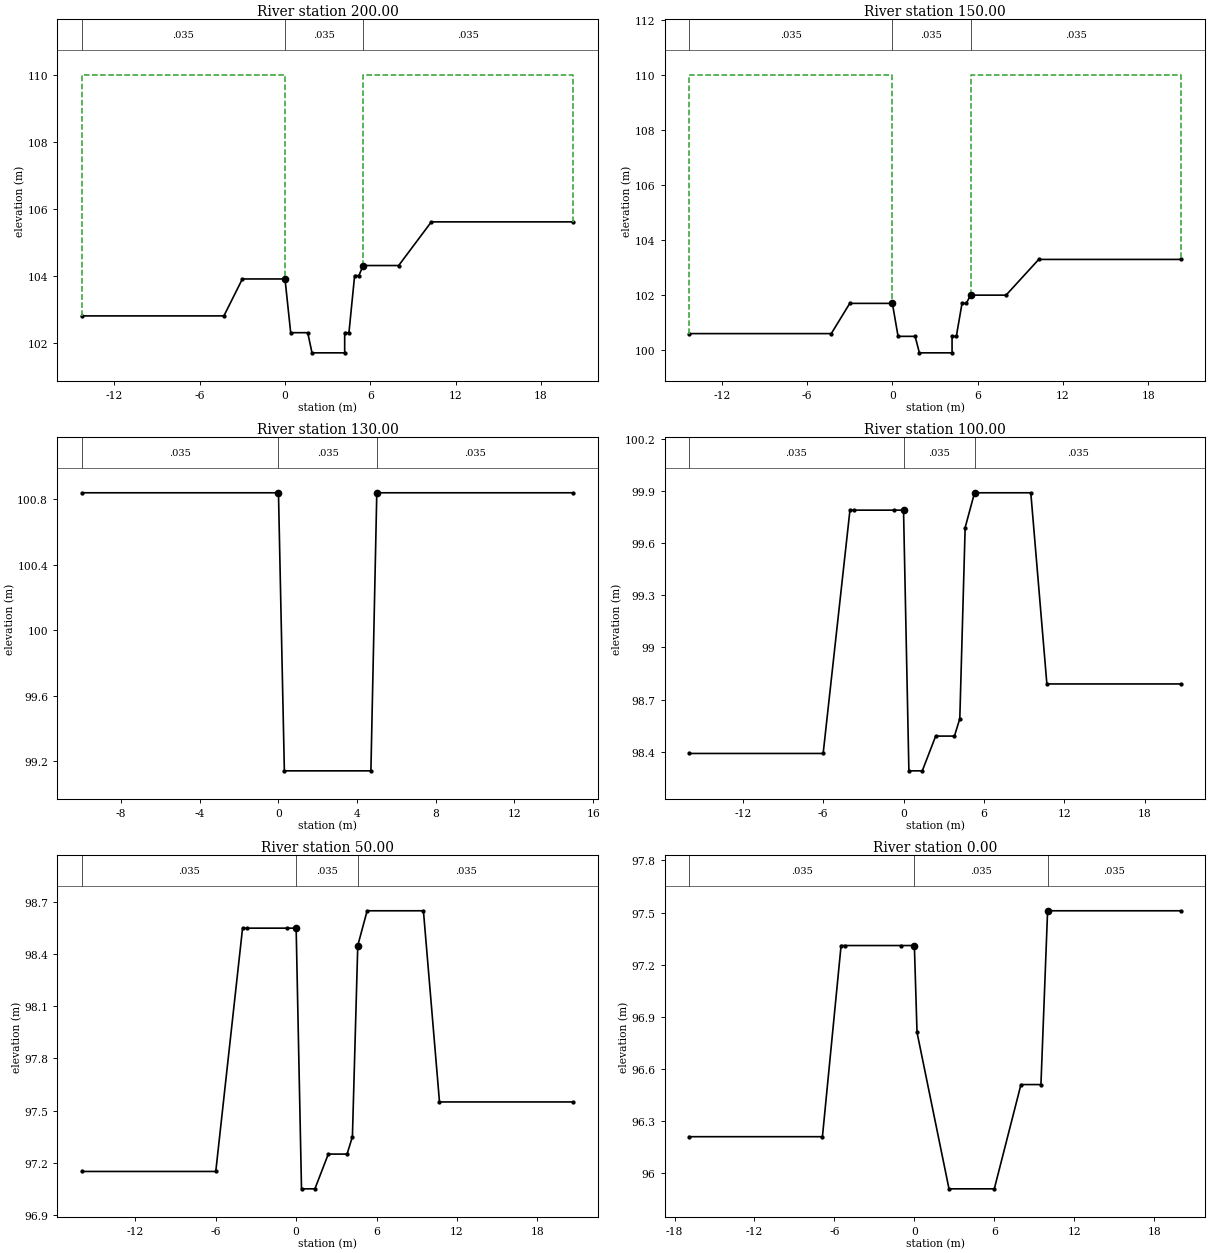
Type RM Length L Ch R = 1 ,200.00  ,50,50,50
BEGIN DESCRIPTION:
4
END DESCRIPTION:
#Sta/Elev= 16
   -14.3  102.82    -4.3  102.82      -3  103.92       0  103.92      .4  102.32
     1.6  102.32     1.9  101.72     4.2  101.72     4.2  102.32     4.5  102.32
     4.9  104.02     5.2  104.02     5.5  104.32       8  104.32    10.3  105.62
    20.3  105.62
#Mann= 3 , 0 , 0
   -14.3    .035       0       0    .035       0     5.5    .035       0
#XS Ineff= 2 , 0
               0     110     5.5             110
Permanent Ineff=
       F       F
#Block Obstruct= 2 , 0
                             5.5
Bank Sta=0,5.5
XS Rating Curve= 0
Exp/Cntr=.3,.1

Type RM Length L Ch R = 1 ,150.00  ,20,20,20
BEGIN DESCRIPTION:
3
END DESCRIPTION:
#Sta/Elev= 16
   -14.3  100.58    -4.3  100.58      -3  101.68       0  101.68      .4  100.48
     1.6  100.48     1.9   99.88     4.2   99.88     4.2  100.48     4.5  100.48
     4.9  101.68     5.2  101.68     5.5  101.98       8  101.98    10.3  103.28
    20.3  103.28
#Mann= 3 , 0 , 0
   -14.3    .035       0       0    .035       0     5.5    .035       0
#XS Ineff= 2 , 0
               0     110     5.5             110
Permanent Ineff=
       F       F
#Block Obstruct= 2 , 0
                             5.5
Bank Sta=0,5.5
XS Rating Curve= 0
Exp/Cntr=.3,.1

Type RM Length L Ch R = 1 ,130.00  ,30,30,30
BEGIN DESCRIPTION:
2.03
END DESCRIPTION:
#Sta/Elev= 6
     -10  100.84       0  100.84      .3   99.14     4.7   99.14       5  100.84
      15  100.84
#Mann= 3 , 0 , 0
     -10    .035       0       0    .035       0       5    .035       0
#XS Ineff= 2 , 0
               0     110       5             110
Permanent Ineff=
       F       F
#Block Obstruct= 2 , 0
                               5
Bank Sta=0,5
XS Rating Curve= 0
Exp/Cntr=.3,.1

Type RM Length L Ch R = 1 ,100.00  ,50,50,50
BEGIN DESCRIPTION:
2
END DESCRIPTION:
#Sta/Elev= 16
     -16   98.39      -6   98.39      -4   99.79    -3.7   99.79     -.7   99.79
       0   99.79      .4   98.29     1.4   98.29     2.4   98.49     3.8   98.49
     4.2   98.59     4.6   99.69     5.3   99.89     9.5   99.89    10.7   98.79
    20.7   98.79
#Mann= 3 , 0 , 0
     -16    .035       0       0    .035       0     5.3    .035       0
#XS Ineff= 2 , 0
               0     110     5.3             110
Permanent Ineff=
       F       F
#Block Obstruct= 2 , 0
                             5.3
Bank Sta=0,5.3
XS Rating Curve= 0
Exp/Cntr=.3,.1

Type RM Length L Ch R = 1 ,50.00   ,50,50,50
BEGIN DESCRIPTION:
1
END DESCRIPTION:
#Sta/Elev= 16
     -16   97.15      -6   97.15      -4   98.55    -3.7   98.55     -.7   98.55
       0   98.55      .4   97.05     1.4   97.05     2.4   97.25     3.8   97.25
     4.2   97.35     4.6   98.45     5.3   98.65     9.5   98.65    10.7   97.55
    20.7   97.55
#Mann= 3 , 0 , 0
     -16    .035       0       0    .035       0     4.6    .035       0
#XS Ineff= 2 , 0
               0     110     4.6             110
Permanent Ineff=
       F       F
#Block Obstruct= 2 , 0
                             4.6
Bank Sta=0,4.6
XS Rating Curve= 0
Exp/Cntr=.3,.1

Type RM Length L Ch R = 1 ,0.00    ,0,0,0
BEGIN DESCRIPTION:
0
END DESCRIPTION:
#Sta/Elev= 13
   -16.9   96.21    -6.9   96.21    -5.5   97.31    -5.2   97.31      -1   97.31
       0   97.31      .2   96.81     2.6   95.91       6   95.91       8   96.51
     9.5   96.51      10   97.51      20   97.51
#Mann= 3 , 0 , 0
   -16.9    .035       0       0    .035       0      10    .035       0
#XS Ineff= 2 , 0
               0     110      10             110
Permanent Ineff=
       F       F
#Block Obstruct= 2 , 0
                              10
Bank Sta=0,10
XS Rating Curve= 0
Exp/Cntr=.3,.1

Chan Stop Cuts=-1