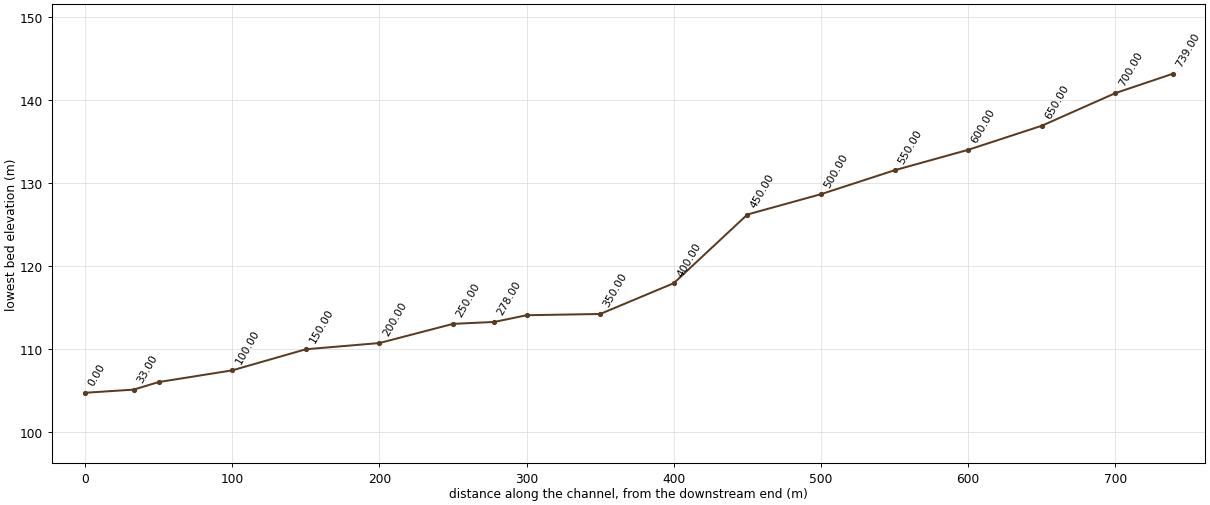
--- JI.prj (project) ---

Proj Title=JI
Current Plan=p01
Default Exp/Contr=.3,.1
SI Units
Geom File=g01
Flow File=f01
Plan File=p01
Y Axis Title=Elevation
X Axis Title(PF)=Main Channel Distance
X Axis Title(XS)=Station
BEGIN DESCRIPTION:
           BACK WATER COMPUTATION
      APPLICATION OF HEC-2 BY Samju Construction Engineering
      zizang-ch: 10,20,30,50,80 yr
END DESCRIPTION:
DSS Export Rating Curves= 0
DSS Export Rating Curve Sorted= 0
DSS Export Volume Flow Curves= 0
DXF OffsetX= 0
DXF OffsetY= 0
DXF ScaleX= 1
DXF ScaleY= 10

--- JI.p01 (plan) ---

Plan Title=Imported Plan 01
Version=Version 3.0.1  Mar 2001
Short Identifier=Imported Pla
Geom File=g01
Flow File=f01
Subcritical Flow
K Sum by GR= 0
Std Step Tol= 0.003
Critical Tol= 0.003
Num of Std Step Trials= 20
Max Error Tol= 0.1
Flow Tol Ratio= 0.001
Split Flow NTrial= 30
Split Flow Tol= 0.02
Split Flow Ratio= 0.02
Log Output Level= 0
Friction Slope Method= 1
Unsteady Friction Slope Method= 2
Parabolic Critical Depth
Global Vel Dist= 0 , 0 , 0
Global Log Level= 0
CheckData=True
Encroach Param=-1 ,0,0, 0
Computation Interval=1HOUR
Output Interval=1HOUR
Run HTab= 0
Run UNet= 0
Run PostProcess= 0
UNET Theta= 1
UNET ZTol= 0.02
UNET ZSATol= 0.1
UNET MxIter= 20
UNET MaxInSteps= 20
UNET DtIC= 0
UNET DtMin= 0
UNET MaxCRTS= 20
UNET WFStab= 2
UNET SFStab= 1
UNET WFX= 1
UNET SFX= 1
UNET Convert EG Bridges=-1
UNET Use Existing IB Tables=-1
Instantaneous Interval=1HOUR
Write IC File= 0
Write Velocity= 0
Write Detailed= 0

--- JI.f01 (steady flow) ---

Flow Title=Imported Flow 01
Version=Version 3.0.1  Mar 2001
Number of Profiles= 5
Profile Names=10YR,20YR,30YR,50YR,80YR
River Rch & RM=RIVER-1,Reach-1         ,739.00
   20.53   22.62   23.84   25.38    26.8
Boundary for River Rch & Prof#=RIVER-1,Reach-1         , 1
Up Type= 0
Dn Type= 3
Dn Slope=.078
Boundary for River Rch & Prof#=RIVER-1,Reach-1         , 2
Up Type= 0
Dn Type= 3
Dn Slope=.078
Boundary for River Rch & Prof#=RIVER-1,Reach-1         , 3
Up Type= 0
Dn Type= 3
Dn Slope=.078
Boundary for River Rch & Prof#=RIVER-1,Reach-1         , 4
Up Type= 0
Dn Type= 3
Dn Slope=.078
Boundary for River Rch & Prof#=RIVER-1,Reach-1         , 5
Up Type= 0
Dn Type= 3
Dn Slope=.078
DSS Import GetInterval= 0
DSS Import GetPeak= 0
DSS Import FillOption= 0

--- JI.g01 (geometry) ---

Geom Title=Imported Geom 01
Version=Version 3.0.1  Mar 2001

River Reach=RIVER-1         ,Reach-1
Reach XY= 2
              .5             .95              .5             .05

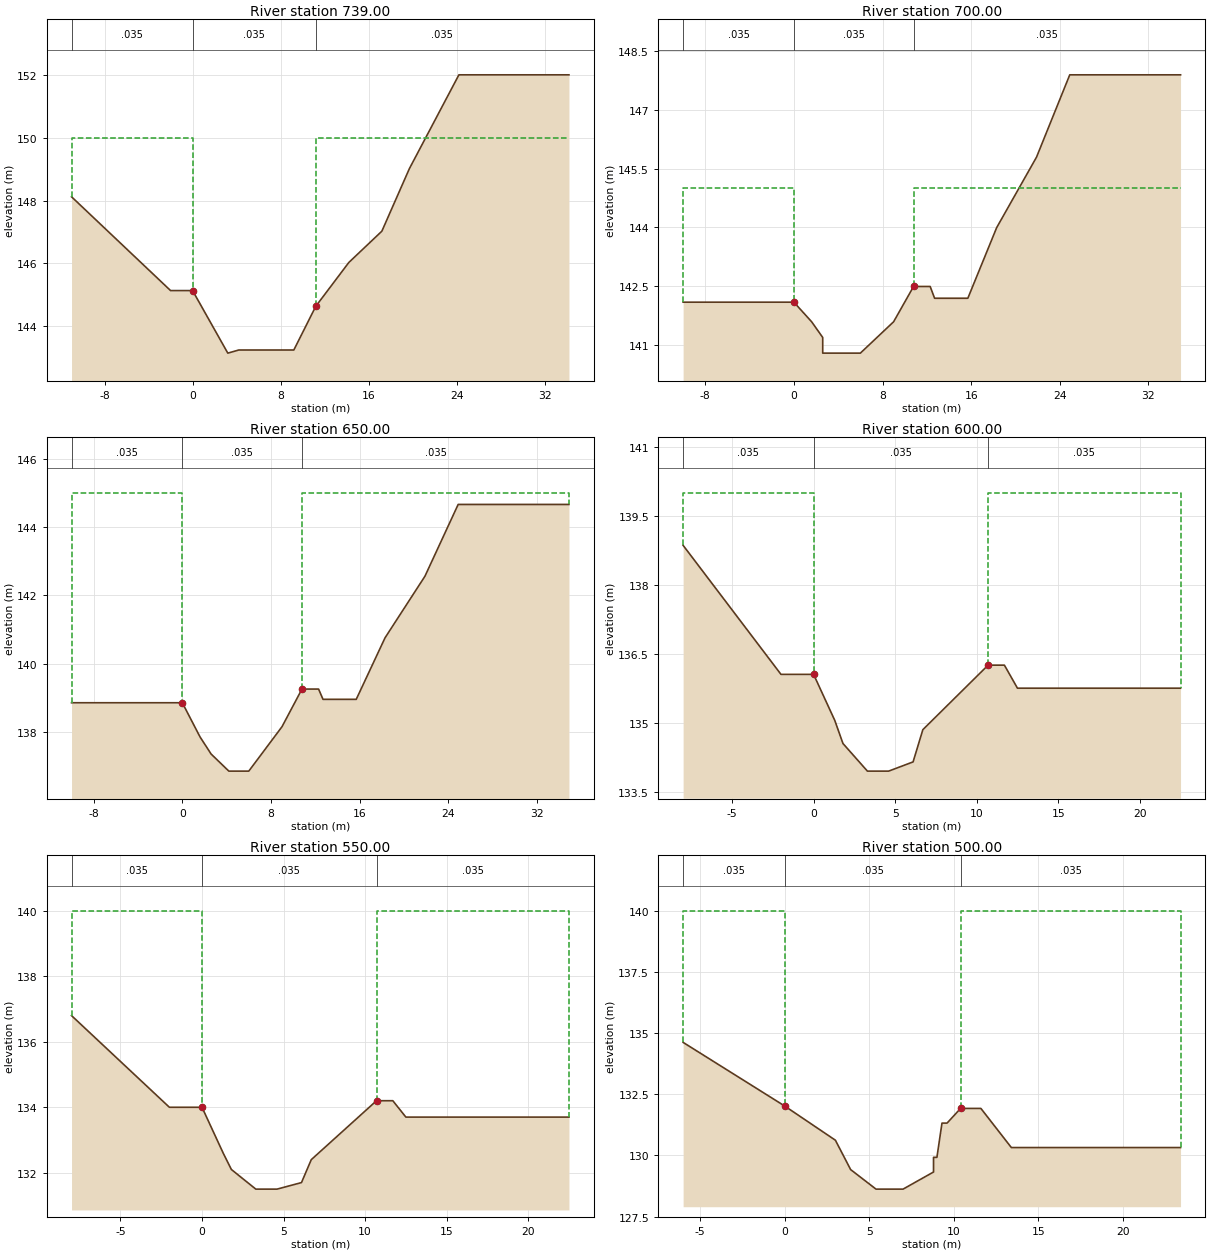
Type RM Length L Ch R = 1 ,739.00  ,39,39,39
BEGIN DESCRIPTION:
14.039
END DESCRIPTION:
#Sta/Elev= 14
     -11  148.12      -8  147.12      -5  146.12      -2  145.12       0  145.12
     3.2  143.12     4.2  143.22     9.2  143.22    11.2  144.62    14.2  146.02
    17.2  147.02    19.7  149.02    24.2  152.02    34.2  152.02
#Mann= 3 , 0 , 0
     -11    .035       0       0    .035       0    11.2    .035       0
#XS Ineff= 2 , 0
               0     150    11.2             150
Permanent Ineff=
       F       F
#Block Obstruct= 2 , 0
                            11.2
Bank Sta=0,11.2
XS Rating Curve= 0
Exp/Cntr=.3,.1

Type RM Length L Ch R = 1 ,700.00  ,50,50,50
BEGIN DESCRIPTION:
14
END DESCRIPTION:
#Sta/Elev= 16
     -10  142.09       0  142.09     1.6  141.59     2.6  141.19     2.6  140.79
     4.2  140.79       6  140.79       9  141.59    10.8  142.49    12.3  142.49
    12.7  142.19    15.7  142.19    18.3  143.99    21.9  145.79    24.9  147.89
    34.9  147.89
#Mann= 3 , 0 , 0
     -10    .035       0       0    .035       0    10.8    .035       0
#XS Ineff= 2 , 0
               0     145    10.8             145
Permanent Ineff=
       F       F
#Block Obstruct= 2 , 0
                            10.8
Bank Sta=0,10.8
XS Rating Curve= 0
Exp/Cntr=.3,.1

Type RM Length L Ch R = 1 ,650.00  ,50,50,50
BEGIN DESCRIPTION:
13
END DESCRIPTION:
#Sta/Elev= 15
     -10  138.86       0  138.86     1.6  137.86     2.6  137.36     4.2  136.86
       6  136.86       9  138.16    10.8  139.26    12.3  139.26    12.7  138.96
    15.7  138.96    18.3  140.76    21.9  142.56    24.9  144.66    34.9  144.66
#Mann= 3 , 0 , 0
     -10    .035       0       0    .035       0    10.8    .035       0
#XS Ineff= 2 , 0
               0     145    10.8             145
Permanent Ineff=
       F       F
#Block Obstruct= 2 , 0
                            10.8
Bank Sta=0,10.8
XS Rating Curve= 0
Exp/Cntr=.3,.1

Type RM Length L Ch R = 1 ,600.00  ,50,50,50
BEGIN DESCRIPTION:
12
END DESCRIPTION:
#Sta/Elev= 14
      -8  138.86      -5  137.46      -2  136.06       0  136.06     1.3  135.06
     1.8  134.56     3.3  133.96     4.6  133.96     6.1  134.16     6.7  134.86
    10.7  136.26    11.7  136.26    12.5  135.76    22.5  135.76
#Mann= 3 , 0 , 0
      -8    .035       0       0    .035       0    10.7    .035       0
#XS Ineff= 2 , 0
               0     140    10.7             140
Permanent Ineff=
       F       F
#Block Obstruct= 2 , 0
                            10.7
Bank Sta=0,10.7
XS Rating Curve= 0
Exp/Cntr=.3,.1

Type RM Length L Ch R = 1 ,550.00  ,50,50,50
BEGIN DESCRIPTION:
11
END DESCRIPTION:
#Sta/Elev= 14
      -8   136.8      -5   135.4      -2     134       0     134     1.3   132.6
     1.8   132.1     3.3   131.5     4.6   131.5     6.1   131.7     6.7   132.4
    10.7   134.2    11.7   134.2    12.5   133.7    22.5   133.7
#Mann= 3 , 0 , 0
      -8    .035       0       0    .035       0    10.7    .035       0
#XS Ineff= 2 , 0
               0     140    10.7             140
Permanent Ineff=
       F       F
#Block Obstruct= 2 , 0
                            10.7
Bank Sta=0,10.7
XS Rating Curve= 0
Exp/Cntr=.3,.1

Type RM Length L Ch R = 1 ,500.00  ,50,50,50
BEGIN DESCRIPTION:
10
END DESCRIPTION:
#Sta/Elev= 16
      -6  134.62      -3  133.32       0  132.02       3  130.62     3.9  129.42
     5.4  128.62       7  128.62     8.8  129.32     8.8  129.92       9  129.92
     9.3  131.32     9.6  131.32    10.4  131.92    11.6  131.92    13.4  130.32
    23.4  130.32
#Mann= 3 , 0 , 0
      -6    .035       0       0    .035       0    10.4    .035       0
#XS Ineff= 2 , 0
               0     140    10.4             140
Permanent Ineff=
       F       F
#Block Obstruct= 2 , 0
                            10.4
Bank Sta=0,10.4
XS Rating Curve= 0
Exp/Cntr=.3,.1

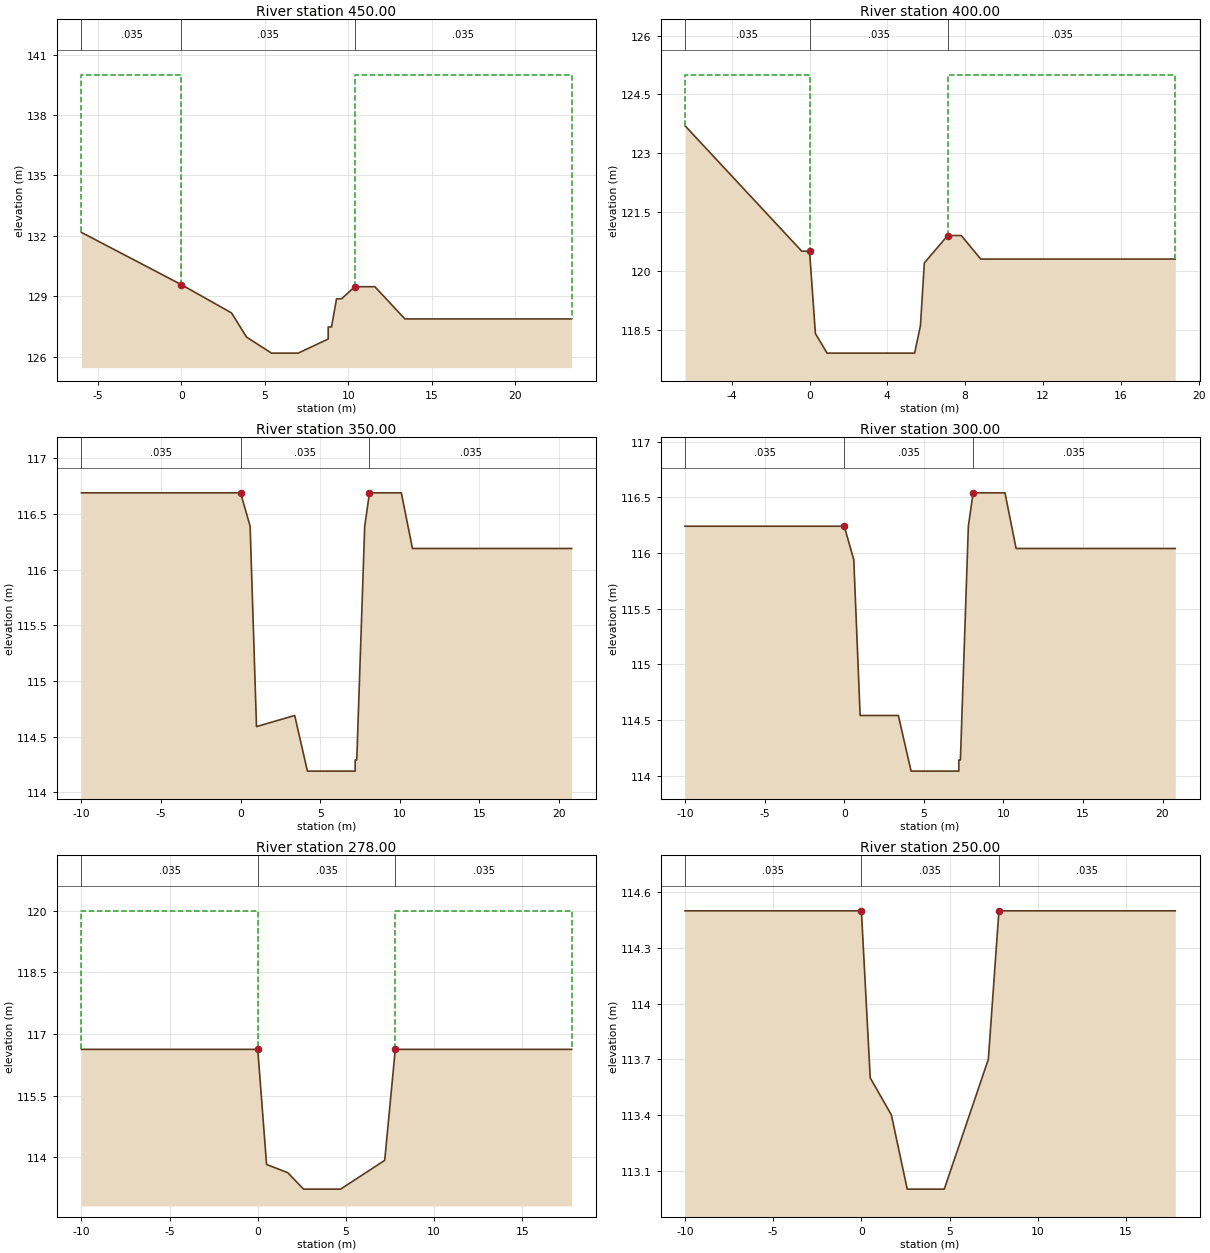
Type RM Length L Ch R = 1 ,450.00  ,50,50,50
BEGIN DESCRIPTION:
9
END DESCRIPTION:
#Sta/Elev= 16
      -6  132.17      -3  130.87       0  129.57       3  128.17     3.9  126.97
     5.4  126.17       7  126.17     8.8  126.87     8.8  127.47       9  127.47
     9.3  128.87     9.6  128.87    10.4  129.47    11.6  129.47    13.4  127.87
    23.4  127.87
#Mann= 3 , 0 , 0
      -6    .035       0       0    .035       0    10.4    .035       0
#XS Ineff= 2 , 0
               0     140    10.4             140
Permanent Ineff=
       F       F
#Block Obstruct= 2 , 0
                            10.4
Bank Sta=0,10.4
XS Rating Curve= 0
Exp/Cntr=.3,.1

Type RM Length L Ch R = 1 ,400.00  ,50,50,50
BEGIN DESCRIPTION:
8
END DESCRIPTION:
#Sta/Elev= 13
    -6.4   123.7    -3.4   122.1     -.4   120.5       0   120.5      .3   118.4
      .9   117.9     5.4   117.9     5.7   118.6     5.9   120.2     7.1   120.9
     7.8   120.9     8.8   120.3    18.8   120.3
#Mann= 3 , 0 , 0
    -6.4    .035       0       0    .035       0     7.1    .035       0
#XS Ineff= 2 , 0
               0     125     7.1             125
Permanent Ineff=
       F       F
#Block Obstruct= 2 , 0
                             7.1
Bank Sta=0,7.1
XS Rating Curve= 0
Exp/Cntr=.3,.1

Type RM Length L Ch R = 1 ,350.00  ,50,50,50
BEGIN DESCRIPTION:
7
END DESCRIPTION:
#Sta/Elev= 14
     -10  116.69       0  116.69      .6  116.39       1  114.59     3.4  114.69
     4.2  114.19     7.2  114.19     7.2  114.29     7.3  114.29     7.8  116.39
     8.1  116.69    10.1  116.69    10.8  116.19    20.8  116.19
#Mann= 3 , 0 , 0
     -10    .035       0       0    .035       0     8.1    .035       0
#XS Ineff= 2 , 0
               0     125     8.1             125
Permanent Ineff=
       F       F
#Block Obstruct= 2 , 0
                             8.1
Bank Sta=0,8.1
XS Rating Curve= 0
Exp/Cntr=.3,.1

Type RM Length L Ch R = 1 ,300.00  ,22,22,22
BEGIN DESCRIPTION:
6
END DESCRIPTION:
#Sta/Elev= 14
     -10  116.24       0  116.24      .6  115.94       1  114.54     3.4  114.54
     4.2  114.04     7.2  114.04     7.2  114.14     7.3  114.14     7.8  116.24
     8.1  116.54    10.1  116.54    10.8  116.04    20.8  116.04
#Mann= 3 , 0 , 0
     -10    .035       0       0    .035       0     8.1    .035       0
#XS Ineff= 2 , 0
               0     125     8.1             125
Permanent Ineff=
       F       F
#Block Obstruct= 2 , 0
                             8.1
Bank Sta=0,8.1
XS Rating Curve= 0
Exp/Cntr=.3,.1

Type RM Length L Ch R = 1 ,278.00  ,28,28,28
BEGIN DESCRIPTION:
5.028
END DESCRIPTION:
#Sta/Elev= 9
     -10  116.63       0  116.63      .5  113.83     1.7  113.63     2.6  113.23
     4.7  113.23     7.2  113.93     7.8  116.63    17.8  116.63
#Mann= 3 , 0 , 0
     -10    .035       0       0    .035       0     7.8    .035       0
#XS Ineff= 2 , 0
               0     120     7.8             120
Permanent Ineff=
       F       F
#Block Obstruct= 2 , 0
                             7.8
Bank Sta=0,7.8
XS Rating Curve= 0
Exp/Cntr=.3,.1

Type RM Length L Ch R = 1 ,250.00  ,50,50,50
BEGIN DESCRIPTION:
5
END DESCRIPTION:
#Sta/Elev= 9
     -10   114.5       0   114.5      .5   113.6     1.7   113.4     2.6     113
     4.7     113     7.2   113.7     7.8   114.5    17.8   114.5
#Mann= 3 , 0 , 0
     -10    .035       0       0    .035       0     7.8    .035       0
#XS Ineff= 2 , 0
               0     120     7.8             120
Permanent Ineff=
       F       F
#Block Obstruct= 2 , 0
                             7.8
Bank Sta=0,7.8
XS Rating Curve= 0
Exp/Cntr=.3,.1

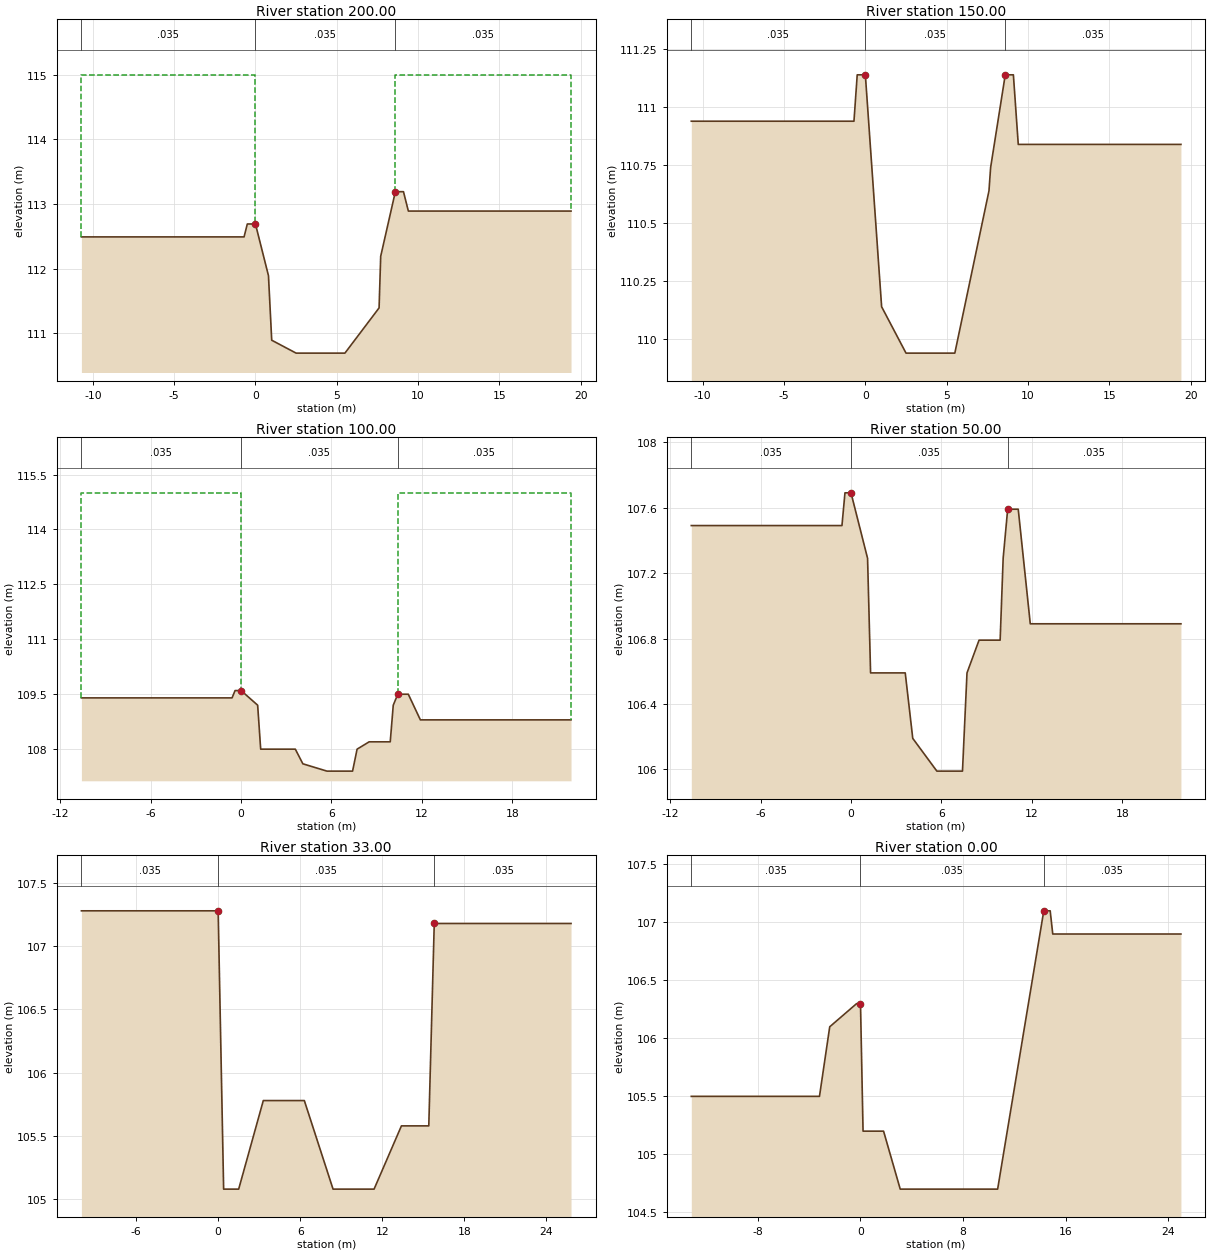
Type RM Length L Ch R = 1 ,200.00  ,50,50,50
BEGIN DESCRIPTION:
4
END DESCRIPTION:
#Sta/Elev= 14
   -10.7  112.49     -.7  112.49     -.5  112.69       0  112.69      .8  111.89
       1  110.89     2.5  110.69     5.5  110.69     7.6  111.39     7.7  112.19
     8.6  113.19     9.1  113.19     9.4  112.89    19.4  112.89
#Mann= 3 , 0 , 0
   -10.7    .035       0       0    .035       0     8.6    .035       0
#XS Ineff= 2 , 0
               0     115     8.6             115
Permanent Ineff=
       F       F
#Block Obstruct= 2 , 0
                             8.6
Bank Sta=0,8.6
XS Rating Curve= 0
Exp/Cntr=.3,.1

Type RM Length L Ch R = 1 ,150.00  ,50,50,50
BEGIN DESCRIPTION:
3
END DESCRIPTION:
#Sta/Elev= 14
   -10.7  110.94     -.7  110.94     -.5  111.14       0  111.14      .8  110.34
       1  110.14     2.5  109.94     5.5  109.94     7.6  110.64     7.7  110.74
     8.6  111.14     9.1  111.14     9.4  110.84    19.4  110.84
#Mann= 3 , 0 , 0
   -10.7    .035       0       0    .035       0     8.6    .035       0
#XS Ineff= 2 , 0
               0     115     8.6             115
Permanent Ineff=
       F       F
#Block Obstruct= 2 , 0
                             8.6
Bank Sta=0,8.6
XS Rating Curve= 0
Exp/Cntr=.3,.1

Type RM Length L Ch R = 1 ,100.00  ,50,50,50
BEGIN DESCRIPTION:
2
END DESCRIPTION:
#Sta/Elev= 18
   -10.6   109.4     -.6   109.4     -.4   109.6       0   109.6     1.1   109.2
     1.3     108     3.6     108     4.1   107.6     5.7   107.4     7.4   107.4
     7.7     108     8.5   108.2     9.9   108.2    10.1   109.2    10.4   109.5
    11.1   109.5    11.9   108.8    21.9   108.8
#Mann= 3 , 0 , 0
   -10.6    .035       0       0    .035       0    10.4    .035       0
#XS Ineff= 2 , 0
               0     115    10.4             115
Permanent Ineff=
       F       F
#Block Obstruct= 2 , 0
                            10.4
Bank Sta=0,10.4
XS Rating Curve= 0
Exp/Cntr=.3,.1

Type RM Length L Ch R = 1 ,50.00   ,17,17,17
BEGIN DESCRIPTION:
1
END DESCRIPTION:
#Sta/Elev= 18
   -10.6  107.49     -.6  107.49     -.4  107.69       0  107.69     1.1  107.29
     1.3  106.59     3.6  106.59     4.1  106.19     5.7  105.99     7.4  105.99
     7.7  106.59     8.5  106.79     9.9  106.79    10.1  107.29    10.4  107.59
    11.1  107.59    11.9  106.89    21.9  106.89
#Mann= 3 , 0 , 0
   -10.6    .035       0       0    .035       0    10.4    .035       0
#XS Ineff= 2 , 0
               0     115    10.4             115
Permanent Ineff=
       F       F
#Block Obstruct= 2 , 0
                            10.4
Bank Sta=0,10.4
XS Rating Curve= 0
Exp/Cntr=.3,.1

Type RM Length L Ch R = 1 ,33.00   ,33,33,33
BEGIN DESCRIPTION:
0.033
END DESCRIPTION:
#Sta/Elev= 12
     -10  107.28       0  107.28      .4  105.08     1.5  105.08     3.3  105.78
     6.3  105.78     8.4  105.08    11.4  105.08    13.4  105.58    15.4  105.58
    15.8  107.18    25.8  107.18
#Mann= 3 , 0 , 0
     -10    .035       0       0    .035       0    15.8    .035       0
#XS Ineff= 2 , 0
               0     115    15.8             115
Permanent Ineff=
       F       F
#Block Obstruct= 2 , 0
                            15.8
Bank Sta=0,15.8
XS Rating Curve= 0
Exp/Cntr=.3,.1

Type RM Length L Ch R = 1 ,0.00    ,0,0,0
BEGIN DESCRIPTION:
0
END DESCRIPTION:
#Sta/Elev= 13
   -13.2   105.5    -3.2   105.5    -2.4   106.1     -.3   106.3       0   106.3
      .2   105.2     1.8   105.2     3.1   104.7    10.7   104.7    14.3   107.1
    14.8   107.1      15   106.9      25   106.9
#Mann= 3 , 0 , 0
   -13.2    .035       0       0    .035       0    14.3    .035       0
#XS Ineff= 2 , 0
               0     115    14.3             115
Permanent Ineff=
       F       F
#Block Obstruct= 2 , 0
                            14.3
Bank Sta=0,14.3
XS Rating Curve= 0
Exp/Cntr=.3,.1

Chan Stop Cuts=-1