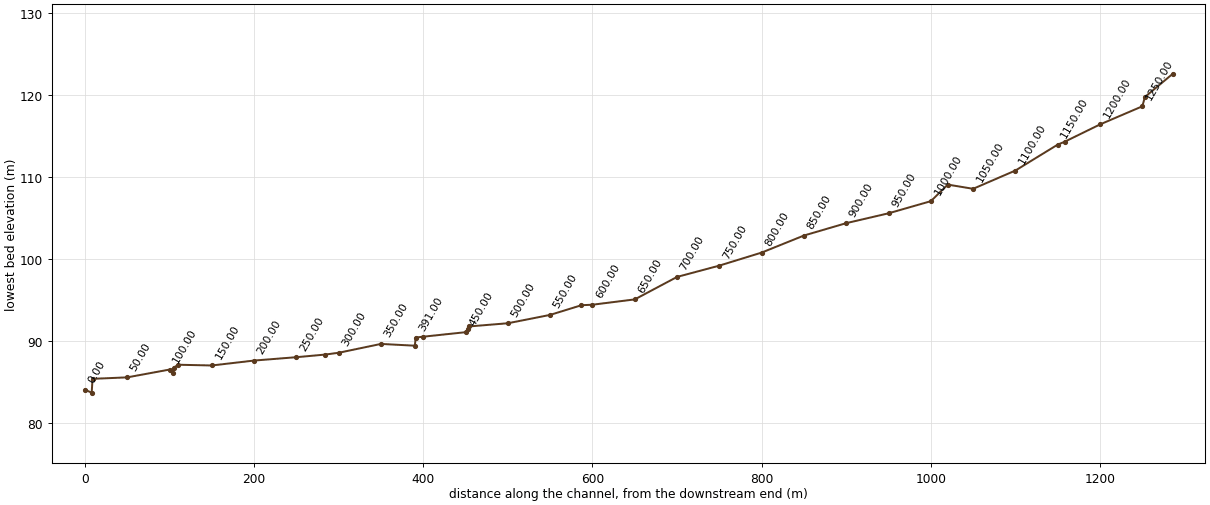
--- SO.prj (project) ---

Proj Title=SO
Current Plan=p01
Default Exp/Contr=.3,.1
SI Units
Geom File=g01
Flow File=f01
Plan File=p01
Y Axis Title=Elevation
X Axis Title(PF)=Main Channel Distance
X Axis Title(XS)=Station
BEGIN DESCRIPTION:
           BACK WATER COMPUTATION
      APPLICATION OF HEC-2 BY Samju Construction Engineering
      sodung-ch: 10,20,30,50,80 yr
END DESCRIPTION:
DSS Export Rating Curves= 0
DSS Export Rating Curve Sorted= 0
DSS Export Volume Flow Curves= 0
DXF OffsetX= 0
DXF OffsetY= 0
DXF ScaleX= 1
DXF ScaleY= 10

--- SO.p01 (plan) ---

Plan Title=Imported Plan 01
Version=Version 3.0.1  Mar 2001
Short Identifier=Imported Pla
Geom File=g01
Flow File=f01
Subcritical Flow
K Sum by GR= 0
Std Step Tol= 0.003
Critical Tol= 0.003
Num of Std Step Trials= 20
Max Error Tol= 0.1
Flow Tol Ratio= 0.001
Split Flow NTrial= 30
Split Flow Tol= 0.02
Split Flow Ratio= 0.02
Log Output Level= 0
Friction Slope Method= 1
Unsteady Friction Slope Method= 2
Parabolic Critical Depth
Global Vel Dist= 0 , 0 , 0
Global Log Level= 0
CheckData=True
Encroach Param=-1 ,0,0, 0
Computation Interval=1HOUR
Output Interval=1HOUR
Run HTab= 0
Run UNet= 0
Run PostProcess= 0
UNET Theta= 1
UNET ZTol= 0.02
UNET ZSATol= 0.1
UNET MxIter= 20
UNET MaxInSteps= 20
UNET DtIC= 0
UNET DtMin= 0
UNET MaxCRTS= 20
UNET WFStab= 2
UNET SFStab= 1
UNET WFX= 1
UNET SFX= 1
UNET Convert EG Bridges=-1
UNET Use Existing IB Tables=-1
Instantaneous Interval=1HOUR
Write IC File= 0
Write Velocity= 0
Write Detailed= 0

--- SO.f01 (steady flow) ---

Flow Title=Imported Flow 01
Version=Version 3.0.1  Mar 2001
Number of Profiles= 5
Profile Names=10YR,20YR,30YR,50YR,80YR
River Rch & RM=RIVER-1,Reach-1         ,1286.00
   13.09   14.42    15.2   16.18   17.09
Boundary for River Rch & Prof#=RIVER-1,Reach-1         , 1
Up Type= 0
Dn Type= 3
Dn Slope=.032
Boundary for River Rch & Prof#=RIVER-1,Reach-1         , 2
Up Type= 0
Dn Type= 3
Dn Slope=.032
Boundary for River Rch & Prof#=RIVER-1,Reach-1         , 3
Up Type= 0
Dn Type= 3
Dn Slope=.032
Boundary for River Rch & Prof#=RIVER-1,Reach-1         , 4
Up Type= 0
Dn Type= 3
Dn Slope=.032
Boundary for River Rch & Prof#=RIVER-1,Reach-1         , 5
Up Type= 0
Dn Type= 3
Dn Slope=.032
DSS Import GetInterval= 0
DSS Import GetPeak= 0
DSS Import FillOption= 0

--- SO.g01 (geometry) ---

Geom Title=Imported Geom 01
Version=Version 3.0.1  Mar 2001

River Reach=RIVER-1         ,Reach-1
Reach XY= 2
              .5             .95              .5             .05

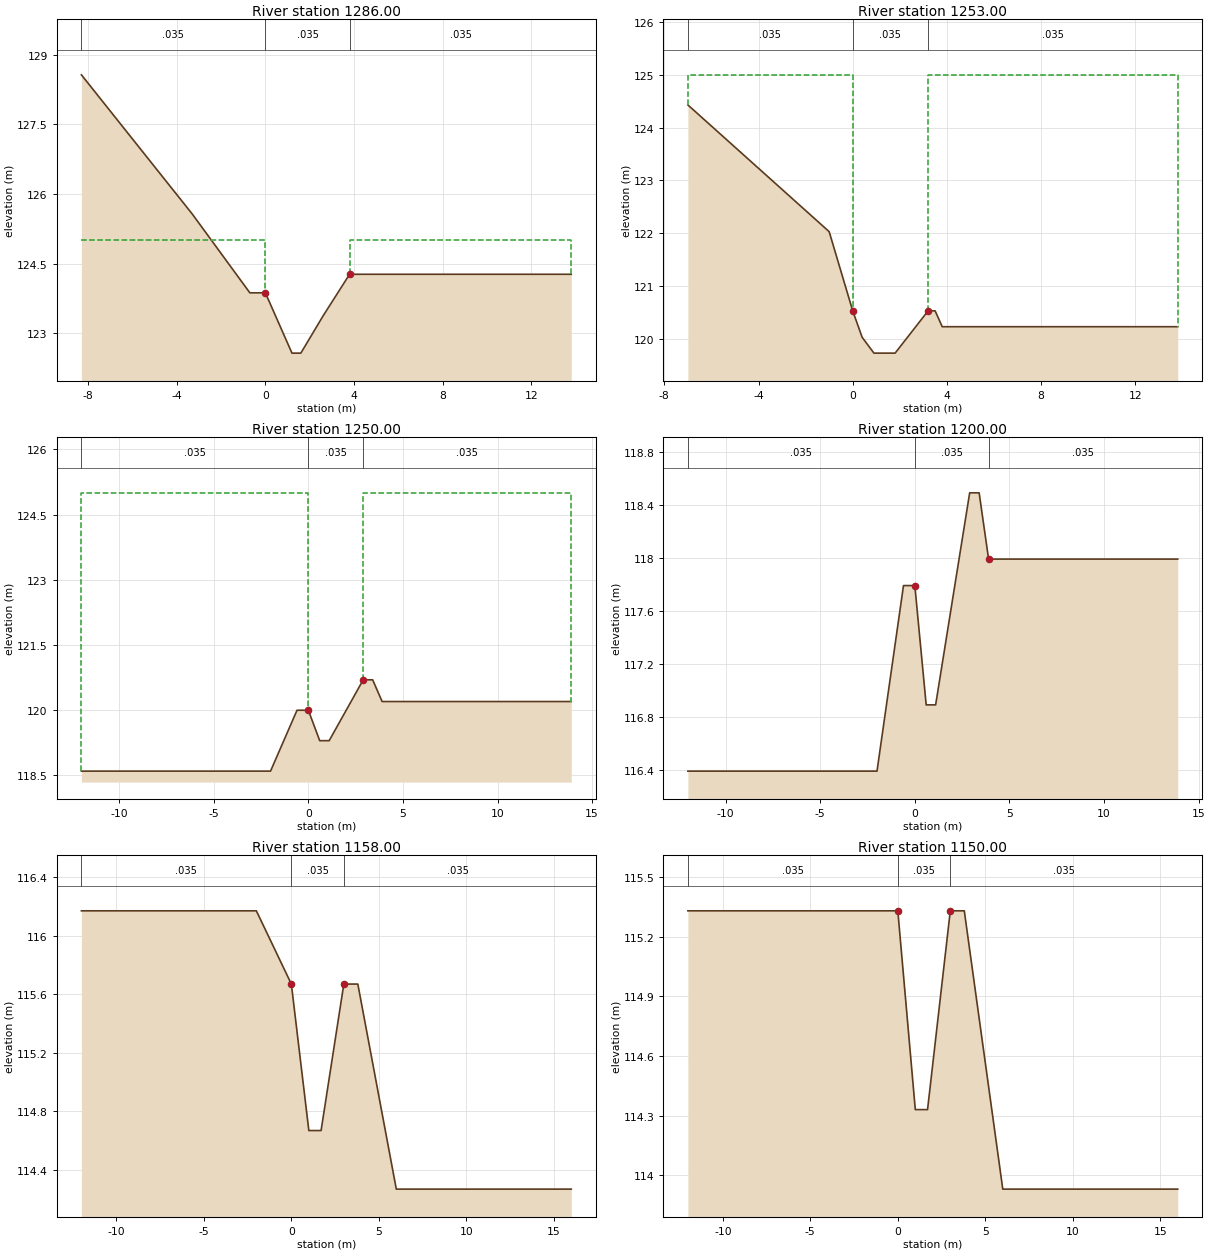
Type RM Length L Ch R = 1 ,1286.00 ,33,33,33
BEGIN DESCRIPTION:
25.036
END DESCRIPTION:
#Sta/Elev= 10
    -8.3  128.57    -5.8  127.07    -3.3  125.57     -.7  123.87       0  123.87
     1.2  122.57     1.6  122.57     2.6  123.37     3.8  124.27    13.8  124.27
#Mann= 3 , 0 , 0
    -8.3    .035       0       0    .035       0     3.8    .035       0
#XS Ineff= 2 , 0
               0     125     3.8             125
Permanent Ineff=
       F       F
#Block Obstruct= 2 , 0
                             3.8
Bank Sta=0,3.8
XS Rating Curve= 0
Exp/Cntr=.3,.1

Type RM Length L Ch R = 1 ,1253.00 ,3,3,3
BEGIN DESCRIPTION:
25.003
END DESCRIPTION:
#Sta/Elev= 11
      -7  124.43      -4  123.23      -1  122.03       0  120.53      .4  120.03
      .9  119.73     1.8  119.73     3.2  120.53     3.5  120.53     3.8  120.23
    13.8  120.23
#Mann= 3 , 0 , 0
      -7    .035       0       0    .035       0     3.2    .035       0
#XS Ineff= 2 , 0
               0     125     3.2             125
Permanent Ineff=
       F       F
#Block Obstruct= 2 , 0
                             3.2
Bank Sta=0,3.2
XS Rating Curve= 0
Exp/Cntr=.3,.1

Type RM Length L Ch R = 1 ,1250.00 ,50,50,50
BEGIN DESCRIPTION:
25
END DESCRIPTION:
#Sta/Elev= 10
     -12   118.6      -2   118.6     -.6     120       0     120      .6   119.3
     1.1   119.3     2.9   120.7     3.4   120.7     3.9   120.2    13.9   120.2
#Mann= 3 , 0 , 0
     -12    .035       0       0    .035       0     2.9    .035       0
#XS Ineff= 2 , 0
               0     125     2.9             125
Permanent Ineff=
       F       F
#Block Obstruct= 2 , 0
                             2.9
Bank Sta=0,2.9
XS Rating Curve= 0
Exp/Cntr=.3,.1

Type RM Length L Ch R = 1 ,1200.00 ,42,42,42
BEGIN DESCRIPTION:
24
END DESCRIPTION:
#Sta/Elev= 10
     -12  116.39      -2  116.39     -.6  117.79       0  117.79      .6  116.89
     1.1  116.89     2.9  118.49     3.4  118.49     3.9  117.99    13.9  117.99
#Mann= 3 , 0 , 0
     -12    .035       0       0    .035       0     3.9    .035       0
#XS Ineff= 2 , 0
               0     125     3.9             125
Permanent Ineff=
       F       F
#Block Obstruct= 2 , 0
                             3.9
Bank Sta=0,3.9
XS Rating Curve= 0
Exp/Cntr=.3,.1

Type RM Length L Ch R = 1 ,1158.00 ,8,8,8
BEGIN DESCRIPTION:
23.008
END DESCRIPTION:
#Sta/Elev= 9
     -12  116.17      -2  116.17       0  115.67       1  114.67     1.7  114.67
       3  115.67     3.8  115.67       6  114.27      16  114.27
#Mann= 3 , 0 , 0
     -12    .035       0       0    .035       0       3    .035       0
#XS Ineff= 2 , 0
               0     125       3             125
Permanent Ineff=
       F       F
#Block Obstruct= 2 , 0
                               3
Bank Sta=0,3
XS Rating Curve= 0
Exp/Cntr=.3,.1

Type RM Length L Ch R = 1 ,1150.00 ,50,50,50
BEGIN DESCRIPTION:
23
END DESCRIPTION:
#Sta/Elev= 9
     -12  115.33      -2  115.33       0  115.33       1  114.33     1.7  114.33
       3  115.33     3.8  115.33       6  113.93      16  113.93
#Mann= 3 , 0 , 0
     -12    .035       0       0    .035       0       3    .035       0
#XS Ineff= 2 , 0
               0     120       3             120
Permanent Ineff=
       F       F
#Block Obstruct= 2 , 0
                               3
Bank Sta=0,3
XS Rating Curve= 0
Exp/Cntr=.3,.1

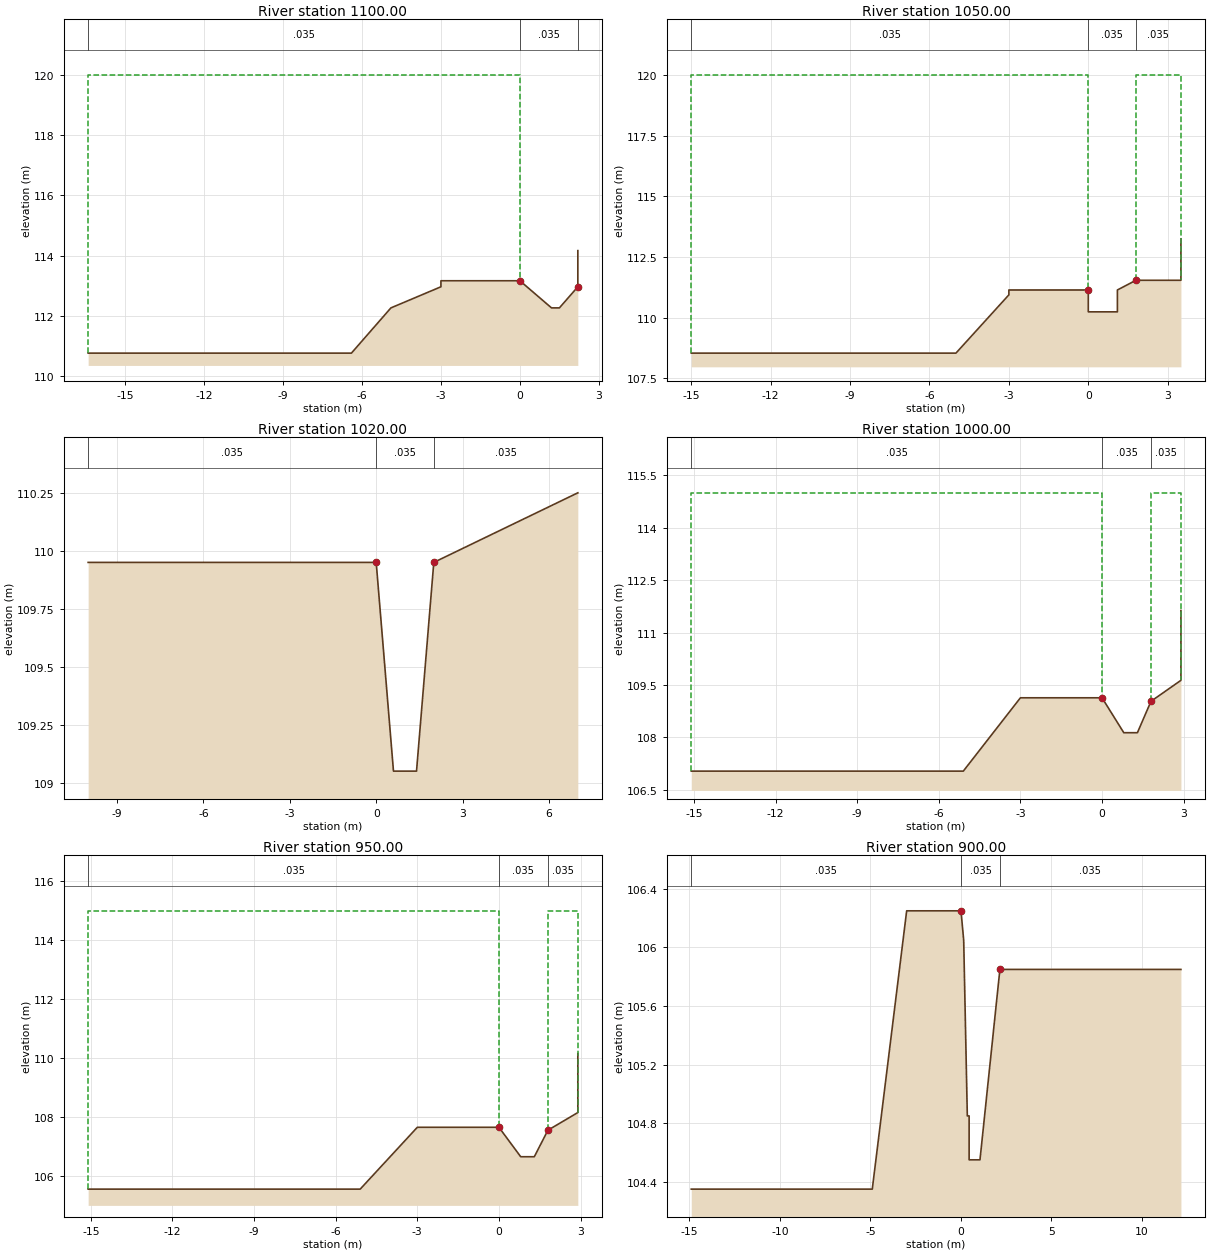
Type RM Length L Ch R = 1 ,1100.00 ,50,50,50
BEGIN DESCRIPTION:
22
END DESCRIPTION:
#Sta/Elev= 10
   -16.4  110.77    -6.4  110.77    -4.9  112.27      -3  112.97      -3  113.17
       0  113.17     1.2  112.27     1.5  112.27     2.2  112.97     2.2  114.17
#Mann= 3 , 0 , 0
   -16.4    .035       0       0    .035       0     2.2    .035       0
#XS Ineff= 2 , 0
               0     120     2.2             120
Permanent Ineff=
       F       F
#Block Obstruct= 2 , 0
                             2.2
Bank Sta=0,2.2
XS Rating Curve= 0
Exp/Cntr=.3,.1

Type RM Length L Ch R = 1 ,1050.00 ,30,30,30
BEGIN DESCRIPTION:
21
END DESCRIPTION:
#Sta/Elev= 11
     -15  108.54      -5  108.54      -3  110.94      -3  111.14       0  111.14
       0  110.24     1.1  110.24     1.1  111.14     1.8  111.54     3.5  111.54
     3.5  113.24
#Mann= 3 , 0 , 0
     -15    .035       0       0    .035       0     1.8    .035       0
#XS Ineff= 2 , 0
               0     120     1.8             120
Permanent Ineff=
       F       F
#Block Obstruct= 2 , 0
                             1.8
Bank Sta=0,1.8
XS Rating Curve= 0
Exp/Cntr=.3,.1

Type RM Length L Ch R = 1 ,1020.00 ,20,20,20
BEGIN DESCRIPTION:
20.02
END DESCRIPTION:
#Sta/Elev= 6
     -10  109.95       0  109.95      .6  109.05     1.4  109.05       2  109.95
       7  110.25
#Mann= 3 , 0 , 0
     -10    .035       0       0    .035       0       2    .035       0
#XS Ineff= 2 , 0
               0     115       2             115
Permanent Ineff=
       F       F
#Block Obstruct= 2 , 0
                               2
Bank Sta=0,2
XS Rating Curve= 0
Exp/Cntr=.3,.1

Type RM Length L Ch R = 1 ,1000.00 ,50,50,50
BEGIN DESCRIPTION:
20
END DESCRIPTION:
#Sta/Elev= 9
   -15.1  107.03    -5.1  107.03      -3  109.13       0  109.13      .8  108.13
     1.3  108.13     1.8  109.03     2.9  109.63     2.9  111.63
#Mann= 3 , 0 , 0
   -15.1    .035       0       0    .035       0     1.8    .035       0
#XS Ineff= 2 , 0
               0     115     1.8             115
Permanent Ineff=
       F       F
#Block Obstruct= 2 , 0
                             1.8
Bank Sta=0,1.8
XS Rating Curve= 0
Exp/Cntr=.3,.1

Type RM Length L Ch R = 1 ,950.00  ,50,50,50
BEGIN DESCRIPTION:
19
END DESCRIPTION:
#Sta/Elev= 9
   -15.1  105.55    -5.1  105.55      -3  107.65       0  107.65      .8  106.65
     1.3  106.65     1.8  107.55     2.9  108.15     2.9  110.15
#Mann= 3 , 0 , 0
   -15.1    .035       0       0    .035       0     1.8    .035       0
#XS Ineff= 2 , 0
               0     115     1.8             115
Permanent Ineff=
       F       F
#Block Obstruct= 2 , 0
                             1.8
Bank Sta=0,1.8
XS Rating Curve= 0
Exp/Cntr=.3,.1

Type RM Length L Ch R = 1 ,900.00  ,50,50,50
BEGIN DESCRIPTION:
18
END DESCRIPTION:
#Sta/Elev= 11
   -14.9  104.35    -4.9  104.35      -3  106.25       0  106.25     .15  106.05
     .35  104.85     .45  104.85     .45  104.55    1.05  104.55    2.15  105.85
   12.15  105.85
#Mann= 3 , 0 , 0
   -14.9    .035       0       0    .035       0    2.15    .035       0
#XS Ineff= 2 , 0
               0     115    2.15             115
Permanent Ineff=
       F       F
#Block Obstruct= 2 , 0
                            2.15
Bank Sta=0,2.15
XS Rating Curve= 0
Exp/Cntr=.3,.1

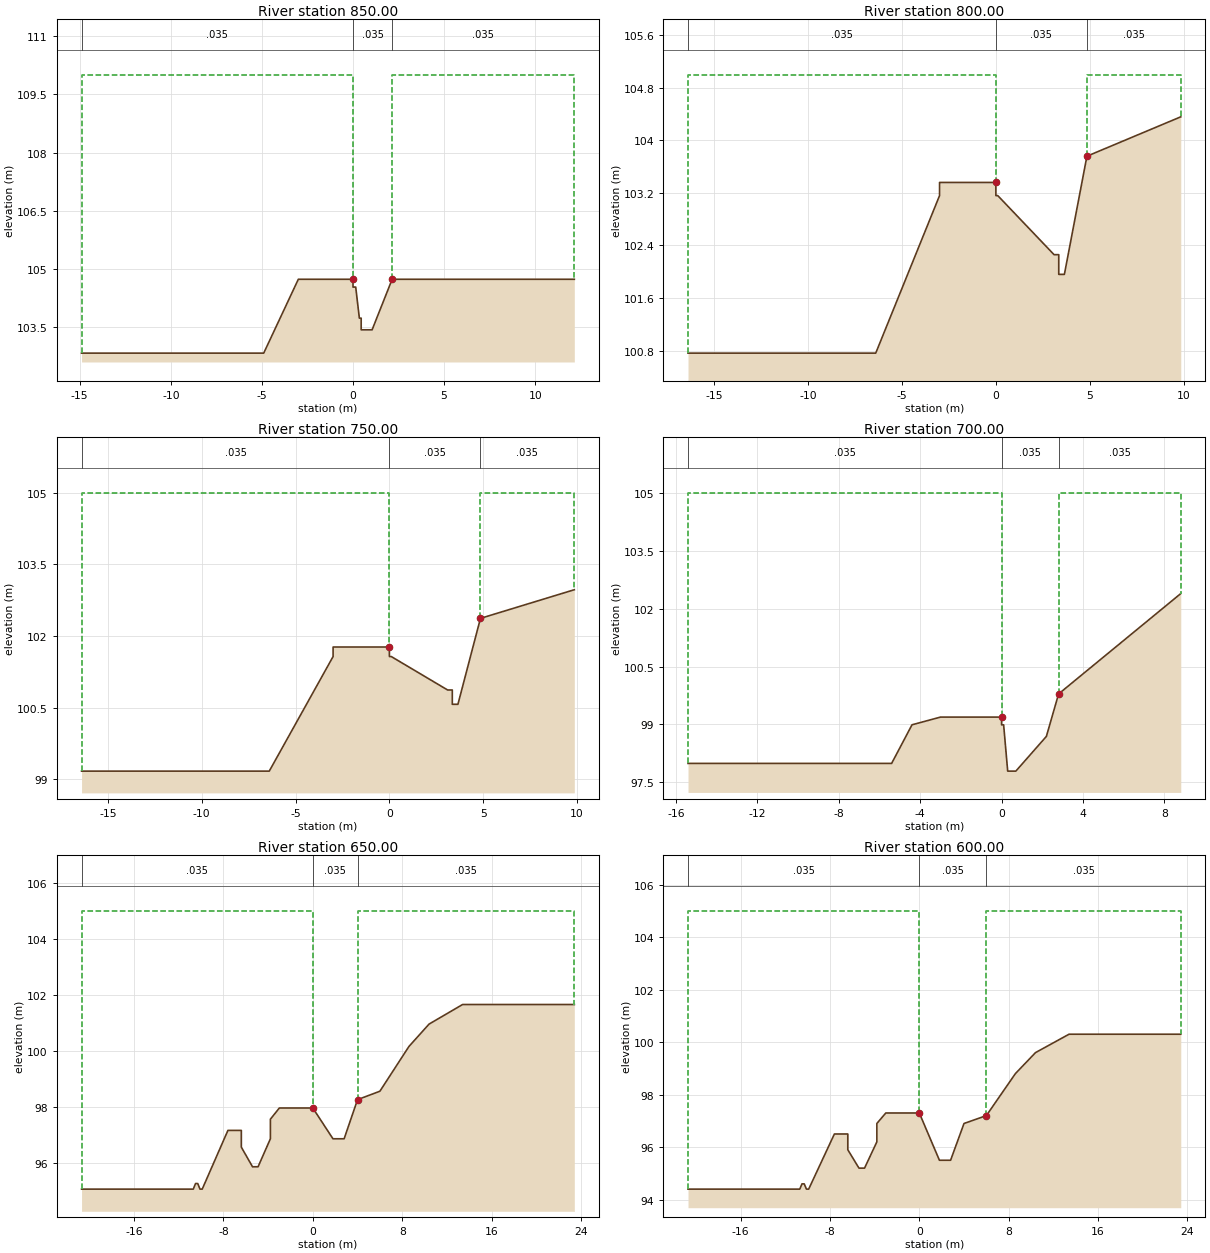
Type RM Length L Ch R = 1 ,850.00  ,50,50,50
BEGIN DESCRIPTION:
17
END DESCRIPTION:
#Sta/Elev= 12
   -14.9  102.84    -4.9  102.84      -3  104.74       0  104.74       0  104.54
     .15  104.54     .35  103.74     .45  103.74     .45  103.44    1.05  103.44
    2.15  104.74   12.15  104.74
#Mann= 3 , 0 , 0
   -14.9    .035       0       0    .035       0    2.15    .035       0
#XS Ineff= 2 , 0
               0     110    2.15             110
Permanent Ineff=
       F       F
#Block Obstruct= 2 , 0
                            2.15
Bank Sta=0,2.15
XS Rating Curve= 0
Exp/Cntr=.3,.1

Type RM Length L Ch R = 1 ,800.00  ,50,50,50
BEGIN DESCRIPTION:
16
END DESCRIPTION:
#Sta/Elev= 13
   -16.4  100.76    -6.4  100.76      -3  103.16      -3  103.36       0  103.36
       0  103.16      .1  103.16     3.1  102.26    3.35  102.26    3.35  101.96
    3.65  101.96    4.85  103.76    9.85  104.36
#Mann= 3 , 0 , 0
   -16.4    .035       0       0    .035       0    4.85    .035       0
#XS Ineff= 2 , 0
               0     105    4.85             105
Permanent Ineff=
       F       F
#Block Obstruct= 2 , 0
                            4.85
Bank Sta=0,4.85
XS Rating Curve= 0
Exp/Cntr=.3,.1

Type RM Length L Ch R = 1 ,750.00  ,50,50,50
BEGIN DESCRIPTION:
15
END DESCRIPTION:
#Sta/Elev= 13
   -16.4   99.17    -6.4   99.17      -3  101.57      -3  101.77       0  101.77
       0  101.57      .1  101.57     3.1  100.87    3.35  100.87    3.35  100.57
    3.65  100.57    4.85  102.37    9.85  102.97
#Mann= 3 , 0 , 0
   -16.4    .035       0       0    .035       0    4.85    .035       0
#XS Ineff= 2 , 0
               0     105    4.85             105
Permanent Ineff=
       F       F
#Block Obstruct= 2 , 0
                            4.85
Bank Sta=0,4.85
XS Rating Curve= 0
Exp/Cntr=.3,.1

Type RM Length L Ch R = 1 ,700.00  ,50,50,50
BEGIN DESCRIPTION:
14
END DESCRIPTION:
#Sta/Elev= 13
   -15.4   97.99    -5.4   97.99    -4.4   98.99      -3   99.19       0   99.19
       0   98.99      .1   98.99      .3   97.79      .7   97.79     2.2   98.69
     2.8   99.79     5.8  101.09     8.8  102.39
#Mann= 3 , 0 , 0
   -15.4    .035       0       0    .035       0     2.8    .035       0
#XS Ineff= 2 , 0
               0     105     2.8             105
Permanent Ineff=
       F       F
#Block Obstruct= 2 , 0
                             2.8
Bank Sta=0,2.8
XS Rating Curve= 0
Exp/Cntr=.3,.1

Type RM Length L Ch R = 1 ,650.00  ,50,50,50
BEGIN DESCRIPTION:
13
END DESCRIPTION:
#Sta/Elev= 23
   -20.7   95.05   -10.7   95.05   -10.5   95.25   -10.3   95.25   -10.1   95.05
    -9.9   95.05    -7.6   97.15    -6.4   97.15    -6.4   96.55    -5.4   95.85
    -4.9   95.85    -3.8   96.85    -3.8   97.55      -3   97.95       0   97.95
     1.8   96.85     2.8   96.85       4   98.25       6   98.55     8.6  100.15
    10.4  100.95    13.4  101.65    23.4  101.65
#Mann= 3 , 0 , 0
   -20.7    .035       0       0    .035       0       4    .035       0
#XS Ineff= 2 , 0
               0     105       4             105
Permanent Ineff=
       F       F
#Block Obstruct= 2 , 0
                               4
Bank Sta=0,4
XS Rating Curve= 0
Exp/Cntr=.3,.1

Type RM Length L Ch R = 1 ,600.00  ,13,13,13
BEGIN DESCRIPTION:
12
END DESCRIPTION:
#Sta/Elev= 23
   -20.7    94.4   -10.7    94.4   -10.5    94.6   -10.3    94.6   -10.1    94.4
    -9.9    94.4    -7.6    96.5    -6.4    96.5    -6.4    95.9    -5.4    95.2
    -4.9    95.2    -3.8    96.2    -3.8    96.9      -3    97.3       0    97.3
     1.8    95.5     2.8    95.5       4    96.9       6    97.2     8.6    98.8
    10.4    99.6    13.4   100.3    23.4   100.3
#Mann= 3 , 0 , 0
   -20.7    .035       0       0    .035       0       6    .035       0
#XS Ineff= 2 , 0
               0     105       6             105
Permanent Ineff=
       F       F
#Block Obstruct= 2 , 0
                               6
Bank Sta=0,6
XS Rating Curve= 0
Exp/Cntr=.3,.1

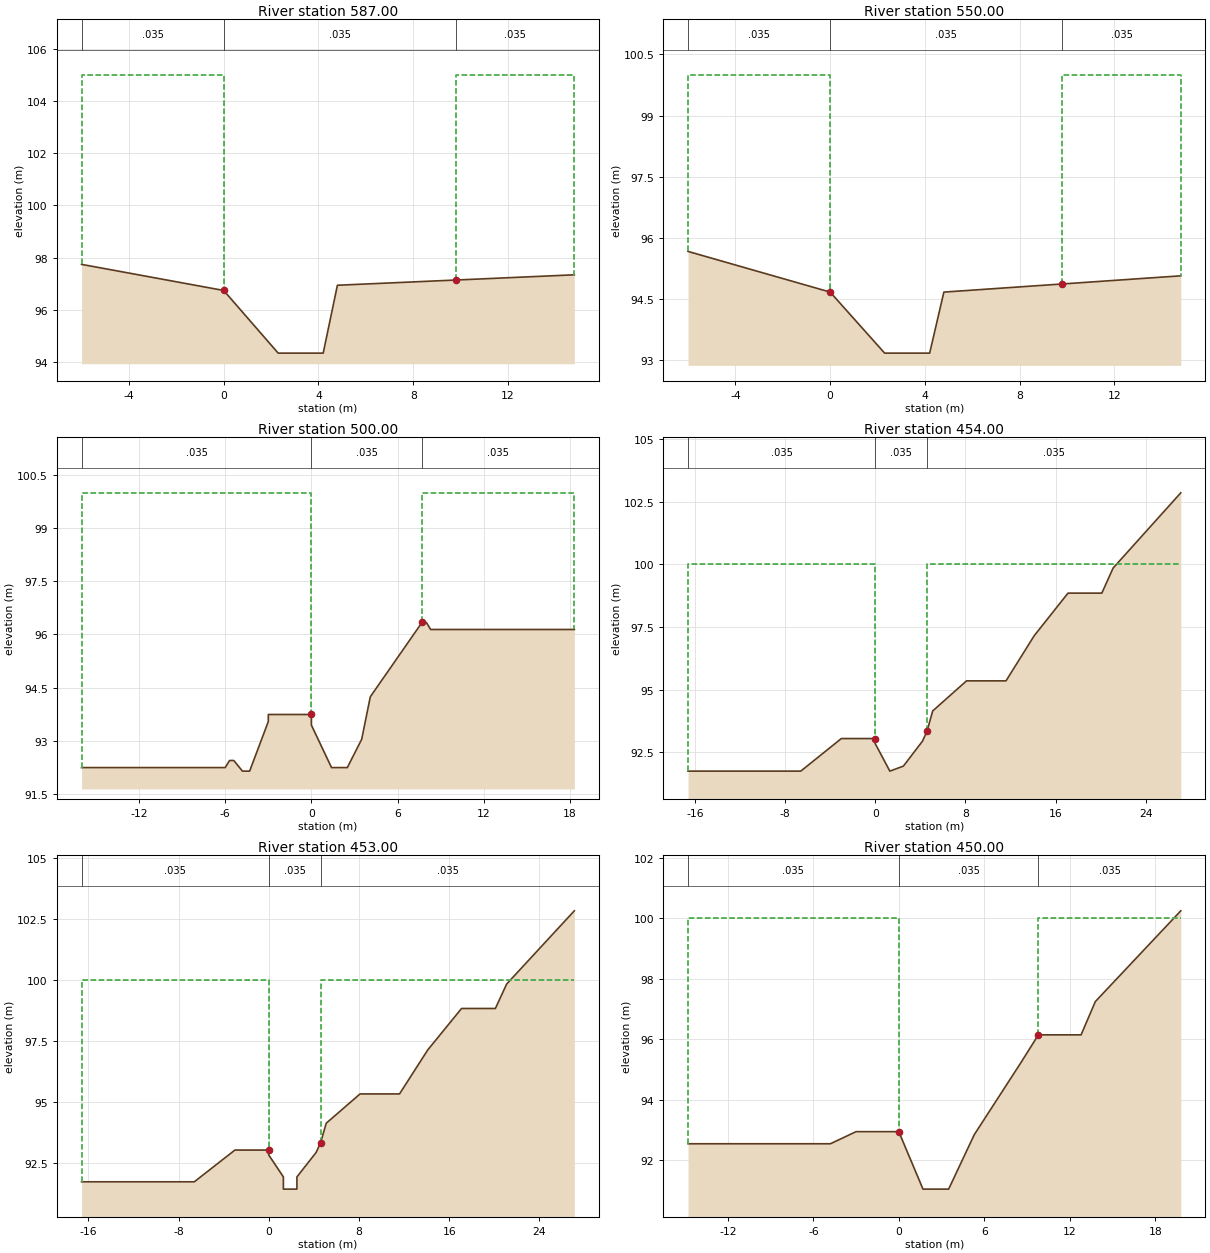
Type RM Length L Ch R = 1 ,587.00  ,37,37,37
BEGIN DESCRIPTION:
11.037
END DESCRIPTION:
#Sta/Elev= 8
      -6   97.74      -3   97.24       0   96.74     2.3   94.34     4.2   94.34
     4.8   96.94     9.8   97.14    14.8   97.34
#Mann= 3 , 0 , 0
      -6    .035       0       0    .035       0     9.8    .035       0
#XS Ineff= 2 , 0
               0     105     9.8             105
Permanent Ineff=
       F       F
#Block Obstruct= 2 , 0
                             9.8
Bank Sta=0,9.8
XS Rating Curve= 0
Exp/Cntr=.3,.1

Type RM Length L Ch R = 1 ,550.00  ,50,50,50
BEGIN DESCRIPTION:
11
END DESCRIPTION:
#Sta/Elev= 8
      -6   95.66      -3   95.16       0   94.66     2.3   93.16     4.2   93.16
     4.8   94.66     9.8   94.86    14.8   95.06
#Mann= 3 , 0 , 0
      -6    .035       0       0    .035       0     9.8    .035       0
#XS Ineff= 2 , 0
               0     100     9.8             100
Permanent Ineff=
       F       F
#Block Obstruct= 2 , 0
                             9.8
Bank Sta=0,9.8
XS Rating Curve= 0
Exp/Cntr=.3,.1

Type RM Length L Ch R = 1 ,500.00  ,46,46,46
BEGIN DESCRIPTION:
10
END DESCRIPTION:
#Sta/Elev= 18
     -16   92.24      -6   92.24    -5.7   92.44    -5.4   92.44    -4.8   92.14
    -4.3   92.14      -3   93.54      -3   93.74       0   93.74       0   93.44
     1.4   92.24     2.5   92.24     3.5   93.04     4.1   94.24     7.7   96.34
       8   96.34     8.3   96.14    18.3   96.14
#Mann= 3 , 0 , 0
     -16    .035       0       0    .035       0     7.7    .035       0
#XS Ineff= 2 , 0
               0     100     7.7             100
Permanent Ineff=
       F       F
#Block Obstruct= 2 , 0
                             7.7
Bank Sta=0,7.7
XS Rating Curve= 0
Exp/Cntr=.3,.1

Type RM Length L Ch R = 1 ,454.00  ,1,1,1
BEGIN DESCRIPTION:
9.004
END DESCRIPTION:
#Sta/Elev= 18
   -16.6   91.75    -6.6   91.75      -3   93.05       0   93.05       0   92.85
     1.3   91.75     2.5   91.95     4.2   92.95     4.6   93.35     5.1   94.15
     8.1   95.35    11.6   95.35    14.1   97.15    17.1   98.85    20.1   98.85
    21.1   99.85    24.1  101.35    27.1  102.85
#Mann= 3 , 0 , 0
   -16.6    .035       0       0    .035       0     4.6    .035       0
#XS Ineff= 2 , 0
               0     100     4.6             100
Permanent Ineff=
       F       F
#Block Obstruct= 2 , 0
                             4.6
Bank Sta=0,4.6
XS Rating Curve= 0
Exp/Cntr=.3,.1

Type RM Length L Ch R = 1 ,453.00  ,3,3,3
BEGIN DESCRIPTION:
9.003
END DESCRIPTION:
#Sta/Elev= 20
   -16.6   91.75    -6.6   91.75      -3   93.05       0   93.05       0   92.85
     1.3   91.95     1.3   91.45     2.5   91.45     2.5   91.95     4.2   92.95
     4.6   93.35     5.1   94.15     8.1   95.35    11.6   95.35    14.1   97.15
    17.1   98.85    20.1   98.85    21.1   99.85    24.1  101.35    27.1  102.85
#Mann= 3 , 0 , 0
   -16.6    .035       0       0    .035       0     4.6    .035       0
#XS Ineff= 2 , 0
               0     100     4.6             100
Permanent Ineff=
       F       F
#Block Obstruct= 2 , 0
                             4.6
Bank Sta=0,4.6
XS Rating Curve= 0
Exp/Cntr=.3,.1

Type RM Length L Ch R = 1 ,450.00  ,50,50,50
BEGIN DESCRIPTION:
9
END DESCRIPTION:
#Sta/Elev= 13
   -14.8   92.55    -4.8   92.55      -3   92.95       0   92.95     1.7   91.05
     3.5   91.05     5.3   92.85     8.6   95.25     9.8   96.15    12.8   96.15
    13.8   97.25    16.8   98.75    19.8  100.25
#Mann= 3 , 0 , 0
   -14.8    .035       0       0    .035       0     9.8    .035       0
#XS Ineff= 2 , 0
               0     100     9.8             100
Permanent Ineff=
       F       F
#Block Obstruct= 2 , 0
                             9.8
Bank Sta=0,9.8
XS Rating Curve= 0
Exp/Cntr=.3,.1

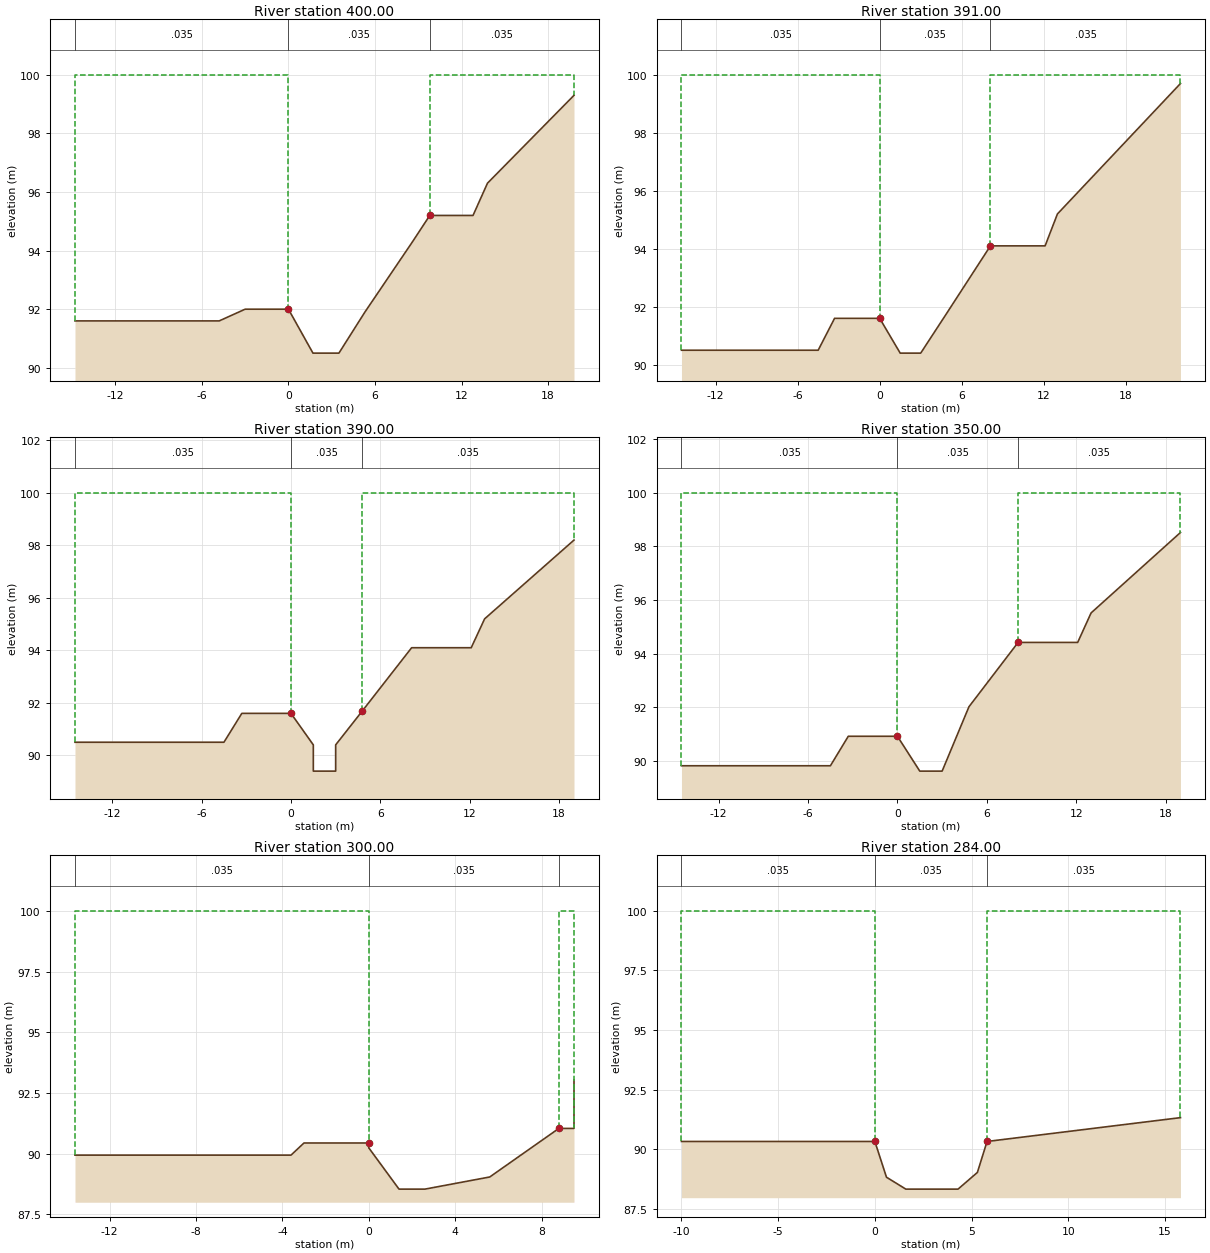
Type RM Length L Ch R = 1 ,400.00  ,9,9,9
BEGIN DESCRIPTION:
8
END DESCRIPTION:
#Sta/Elev= 13
   -14.8    91.6    -4.8    91.6      -3      92       0      92     1.7    90.5
     3.5    90.5     5.3    91.9     8.6    94.3     9.8    95.2    12.8    95.2
    13.8    96.3    16.8    97.8    19.8    99.3
#Mann= 3 , 0 , 0
   -14.8    .035       0       0    .035       0     9.8    .035       0
#XS Ineff= 2 , 0
               0     100     9.8             100
Permanent Ineff=
       F       F
#Block Obstruct= 2 , 0
                             9.8
Bank Sta=0,9.8
XS Rating Curve= 0
Exp/Cntr=.3,.1

Type RM Length L Ch R = 1 ,391.00  ,1,1,1
BEGIN DESCRIPTION:
7.041
END DESCRIPTION:
#Sta/Elev= 14
   -14.5    90.5    -4.5    90.5    -3.3    91.6      -3    91.6       0    91.6
     1.5    90.4       3    90.4     4.8    91.7     8.1    94.1    12.1    94.1
      13    95.2      16    96.7      19    98.2      22    99.7
#Mann= 3 , 0 , 0
   -14.5    .035       0       0    .035       0     8.1    .035       0
#XS Ineff= 2 , 0
               0     100     8.1             100
Permanent Ineff=
       F       F
#Block Obstruct= 2 , 0
                             8.1
Bank Sta=0,8.1
XS Rating Curve= 0
Exp/Cntr=.3,.1

Type RM Length L Ch R = 1 ,390.00  ,40,40,40
BEGIN DESCRIPTION:
7.04
END DESCRIPTION:
#Sta/Elev= 15
   -14.5    90.5    -4.5    90.5    -3.3    91.6      -3    91.6       0    91.6
     1.5    90.4     1.5    89.4       3    89.4       3    90.4     4.8    91.7
     8.1    94.1    12.1    94.1      13    95.2      16    96.7      19    98.2
#Mann= 3 , 0 , 0
   -14.5    .035       0       0    .035       0     4.8    .035       0
#XS Ineff= 2 , 0
               0     100     4.8             100
Permanent Ineff=
       F       F
#Block Obstruct= 2 , 0
                             4.8
Bank Sta=0,4.8
XS Rating Curve= 0
Exp/Cntr=.3,.1

Type RM Length L Ch R = 1 ,350.00  ,50,50,50
BEGIN DESCRIPTION:
7
END DESCRIPTION:
#Sta/Elev= 13
   -14.5   89.82    -4.5   89.82    -3.3   90.92      -3   90.92       0   90.92
     1.5   89.62       3   89.62     4.8   92.02     8.1   94.42    12.1   94.42
      13   95.52      16   97.02      19   98.52
#Mann= 3 , 0 , 0
   -14.5    .035       0       0    .035       0     8.1    .035       0
#XS Ineff= 2 , 0
               0     100     8.1             100
Permanent Ineff=
       F       F
#Block Obstruct= 2 , 0
                             8.1
Bank Sta=0,8.1
XS Rating Curve= 0
Exp/Cntr=.3,.1

Type RM Length L Ch R = 1 ,300.00  ,16,16,16
BEGIN DESCRIPTION:
6
END DESCRIPTION:
#Sta/Elev= 11
   -13.6   89.94    -3.6   89.94      -3   90.44       0   90.44       0   90.24
     1.4   88.54     2.6   88.54     5.6   89.04     8.8   91.04     9.5   91.04
     9.5   93.04
#Mann= 3 , 0 , 0
   -13.6    .035       0       0    .035       0     8.8    .035       0
#XS Ineff= 2 , 0
               0     100     8.8             100
Permanent Ineff=
       F       F
#Block Obstruct= 2 , 0
                             8.8
Bank Sta=0,8.8
XS Rating Curve= 0
Exp/Cntr=.3,.1

Type RM Length L Ch R = 1 ,284.00  ,34,34,34
BEGIN DESCRIPTION:
5.034
END DESCRIPTION:
#Sta/Elev= 9
     -10   90.32       0   90.32      .6   88.82     1.6   88.32     4.3   88.32
     5.3   89.02     5.8   90.32    10.8   90.82    15.8   91.32
#Mann= 3 , 0 , 0
     -10    .035       0       0    .035       0     5.8    .035       0
#XS Ineff= 2 , 0
               0     100     5.8             100
Permanent Ineff=
       F       F
#Block Obstruct= 2 , 0
                             5.8
Bank Sta=0,5.8
XS Rating Curve= 0
Exp/Cntr=.3,.1

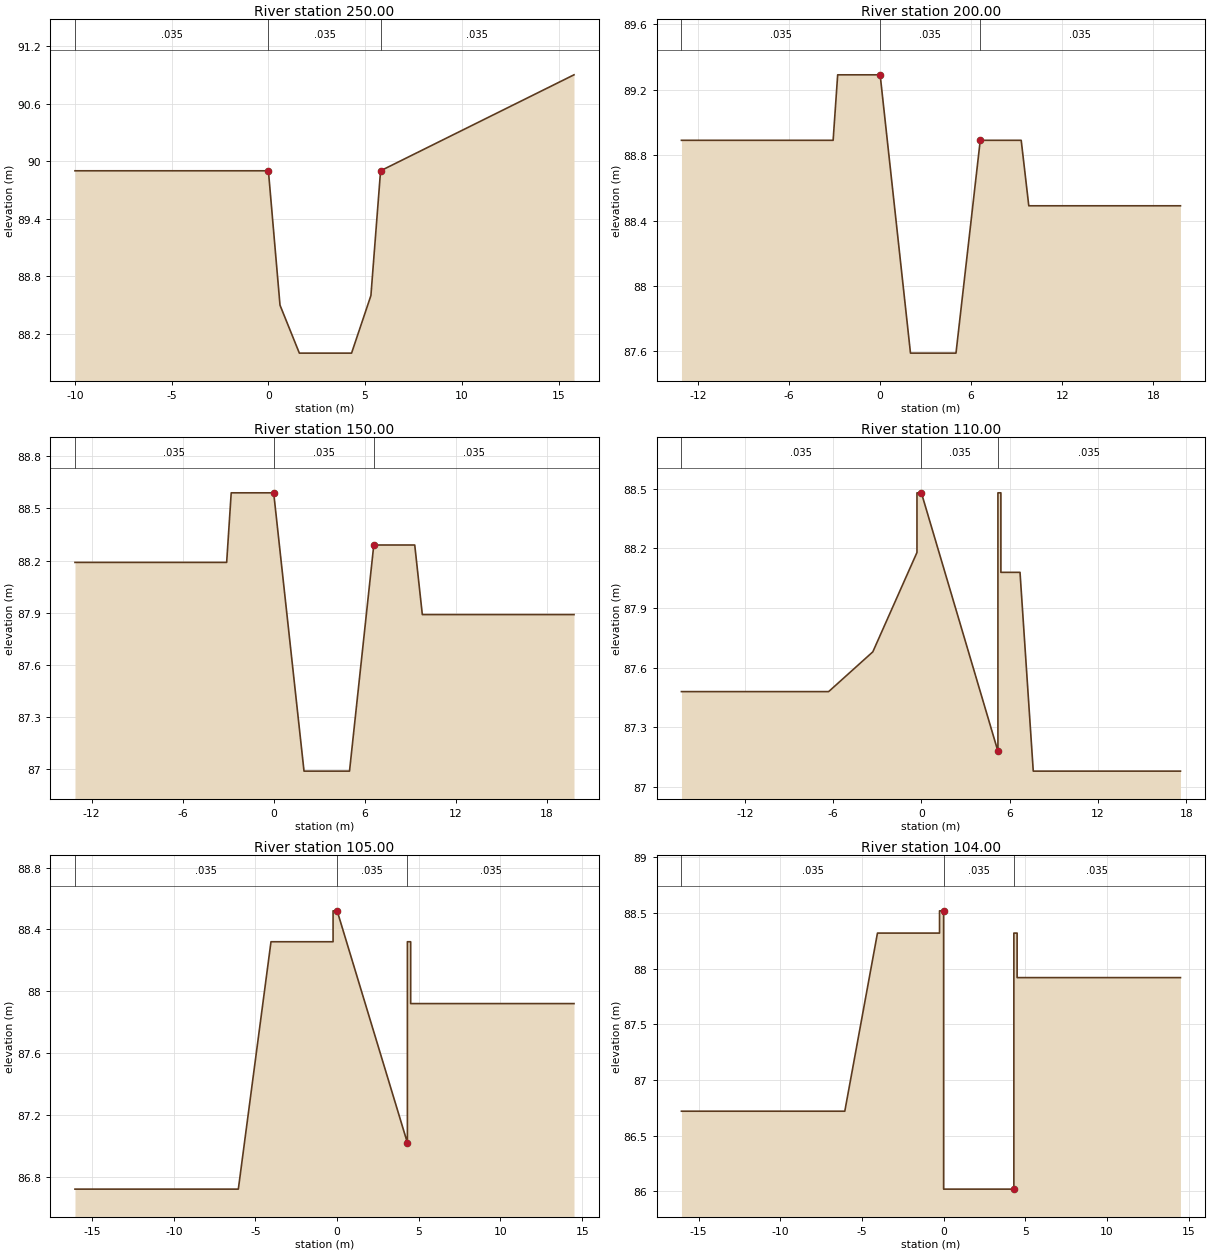
Type RM Length L Ch R = 1 ,250.00  ,50,50,50
BEGIN DESCRIPTION:
5
END DESCRIPTION:
#Sta/Elev= 9
     -10    89.9       0    89.9      .6    88.5     1.6      88     4.3      88
     5.3    88.6     5.8    89.9    10.8    90.4    15.8    90.9
#Mann= 3 , 0 , 0
     -10    .035       0       0    .035       0     5.8    .035       0
#XS Ineff= 2 , 0
               0     100     5.8             100
Permanent Ineff=
       F       F
#Block Obstruct= 2 , 0
                             5.8
Bank Sta=0,5.8
XS Rating Curve= 0
Exp/Cntr=.3,.1

Type RM Length L Ch R = 1 ,200.00  ,50,50,50
BEGIN DESCRIPTION:
4
END DESCRIPTION:
#Sta/Elev= 10
   -13.1   88.89    -3.1   88.89    -2.8   89.29       0   89.29       2   87.59
       5   87.59     6.6   88.89     9.3   88.89     9.8   88.49    19.8   88.49
#Mann= 3 , 0 , 0
   -13.1    .035       0       0    .035       0     6.6    .035       0
#XS Ineff= 2 , 0
               0     100     6.6             100
Permanent Ineff=
       F       F
#Block Obstruct= 2 , 0
                             6.6
Bank Sta=0,6.6
XS Rating Curve= 0
Exp/Cntr=.3,.1

Type RM Length L Ch R = 1 ,150.00  ,40,40,40
BEGIN DESCRIPTION:
3
END DESCRIPTION:
#Sta/Elev= 10
   -13.1   88.19    -3.1   88.19    -2.8   88.59       0   88.59       2   86.99
       5   86.99     6.6   88.29     9.3   88.29     9.8   87.89    19.8   87.89
#Mann= 3 , 0 , 0
   -13.1    .035       0       0    .035       0     6.6    .035       0
#XS Ineff= 2 , 0
               0     100     6.6             100
Permanent Ineff=
       F       F
#Block Obstruct= 2 , 0
                             6.6
Bank Sta=0,6.6
XS Rating Curve= 0
Exp/Cntr=.3,.1

Type RM Length L Ch R = 1 ,110.00  ,5,5,5
BEGIN DESCRIPTION:
2.01
END DESCRIPTION:
#Sta/Elev= 13
   -16.3   87.48    -6.3   87.48    -3.3   87.68     -.3   88.18     -.3   88.48
       0   88.48     5.2   87.18     5.2   88.48     5.4   88.48     5.4   88.08
     6.7   88.08     7.6   87.08    17.6   87.08
#Mann= 3 , 0 , 0
   -16.3    .035       0       0    .035       0     5.2    .035       0
#XS Ineff= 2 , 0
               0     100     5.2             100
Permanent Ineff=
       F       F
#Block Obstruct= 2 , 0
                             5.2
Bank Sta=0,5.2
XS Rating Curve= 0
Exp/Cntr=.3,.1

Type RM Length L Ch R = 1 ,105.00  ,1,1,1
BEGIN DESCRIPTION:
2.005
END DESCRIPTION:
#Sta/Elev= 11
  -16.05   86.72   -6.05   86.72   -4.05   88.32    -.25   88.32    -.25   88.52
       0   88.52     4.3   87.02     4.3   88.32     4.5   88.32     4.5   87.92
    14.5   87.92
#Mann= 3 , 0 , 0
  -16.05    .035       0       0    .035       0     4.3    .035       0
#XS Ineff= 2 , 0
               0     100     4.3             100
Permanent Ineff=
       F       F
#Block Obstruct= 2 , 0
                             4.3
Bank Sta=0,4.3
XS Rating Curve= 0
Exp/Cntr=.3,.1

Type RM Length L Ch R = 1 ,104.00  ,4,4,4
BEGIN DESCRIPTION:
2.004
END DESCRIPTION:
#Sta/Elev= 14
  -16.05   86.72   -6.05   86.72   -4.05   88.32    -.25   88.32    -.25   88.52
       0   88.52       0   87.02       0   86.02     4.3   86.02     4.3   87.02
     4.3   88.32     4.5   88.32     4.5   87.92    14.5   87.92
#Mann= 3 , 0 , 0
  -16.05    .035       0       0    .035       0     4.3    .035       0
#XS Ineff= 2 , 0
               0     100     4.3             100
Permanent Ineff=
       F       F
#Block Obstruct= 2 , 0
                             4.3
Bank Sta=0,4.3
XS Rating Curve= 0
Exp/Cntr=.3,.1

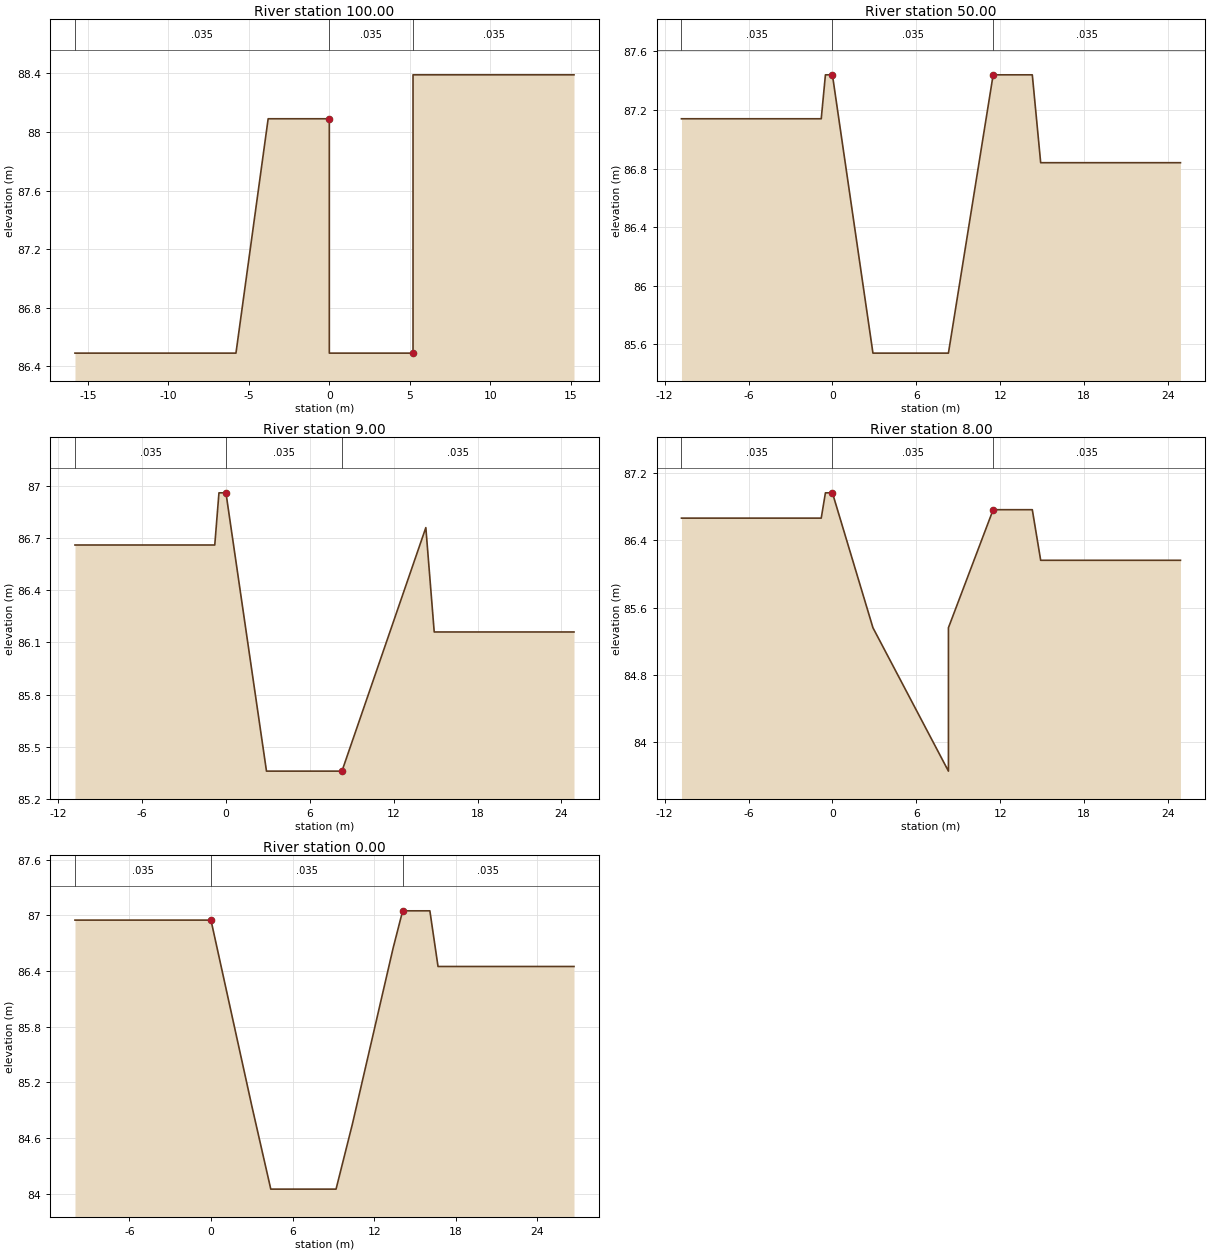
Type RM Length L Ch R = 1 ,100.00  ,50,50,50
BEGIN DESCRIPTION:
2
END DESCRIPTION:
#Sta/Elev= 8
   -15.8   86.49    -5.8   86.49    -3.8   88.09       0   88.09       0   86.49
     5.2   86.49     5.2   88.39    15.2   88.39
#Mann= 3 , 0 , 0
   -15.8    .035       0       0    .035       0     5.2    .035       0
#XS Ineff= 2 , 0
               0     100     5.2             100
Permanent Ineff=
       F       F
#Block Obstruct= 2 , 0
                             5.2
Bank Sta=0,5.2
XS Rating Curve= 0
Exp/Cntr=.3,.1

Type RM Length L Ch R = 1 ,50.00   ,41,41,41
BEGIN DESCRIPTION:
1
END DESCRIPTION:
#Sta/Elev= 10
   -10.8   87.14     -.8   87.14     -.5   87.44       0   87.44     2.9   85.54
     8.3   85.54    11.5   87.44    14.3   87.44    14.9   86.84    24.9   86.84
#Mann= 3 , 0 , 0
   -10.8    .035       0       0    .035       0    11.5    .035       0
#XS Ineff= 2 , 0
               0     100    11.5             100
Permanent Ineff=
       F       F
#Block Obstruct= 2 , 0
                            11.5
Bank Sta=0,11.5
XS Rating Curve= 0
Exp/Cntr=.3,.1

Type RM Length L Ch R = 1 ,9.00    ,1,1,1
BEGIN DESCRIPTION:
0.009
END DESCRIPTION:
#Sta/Elev= 9
   -10.8   86.66     -.8   86.66     -.5   86.96       0   86.96     2.9   85.36
     8.3   85.36    14.3   86.76    14.9   86.16    24.9   86.16
#Mann= 3 , 0 , 0
   -10.8    .035       0       0    .035       0     8.3    .035       0
#XS Ineff= 2 , 0
               0     100     8.3             100
Permanent Ineff=
       F       F
#Block Obstruct= 2 , 0
                            11.5
Bank Sta=0,8.3
XS Rating Curve= 0
Exp/Cntr=.3,.1

Type RM Length L Ch R = 1 ,8.00    ,8,8,8
BEGIN DESCRIPTION:
0.008
END DESCRIPTION:
#Sta/Elev= 11
   -10.8   86.66     -.8   86.66     -.5   86.96       0   86.96     2.9   85.36
     8.3   83.66     8.3   85.36    11.5   86.76    14.3   86.76    14.9   86.16
    24.9   86.16
#Mann= 3 , 0 , 0
   -10.8    .035       0       0    .035       0    11.5    .035       0
#XS Ineff= 2 , 0
               0     100    11.5             100
Permanent Ineff=
       F       F
#Block Obstruct= 2 , 0
                            11.5
Bank Sta=0,11.5
XS Rating Curve= 0
Exp/Cntr=.3,.1

Type RM Length L Ch R = 1 ,0.00    ,0,0,0
BEGIN DESCRIPTION:
0
END DESCRIPTION:
#Sta/Elev= 11
     -10   86.95       0   86.95       3   84.95     4.4   84.05     9.2   84.05
    10.4   84.75    13.4   86.65    14.1   87.05    16.1   87.05    16.7   86.45
    26.7   86.45
#Mann= 3 , 0 , 0
     -10    .035       0       0    .035       0    14.1    .035       0
#XS Ineff= 2 , 0
               0     100    14.1             100
Permanent Ineff=
       F       F
#Block Obstruct= 2 , 0
                            14.1
Bank Sta=0,14.1
XS Rating Curve= 0
Exp/Cntr=.3,.1

Chan Stop Cuts=-1