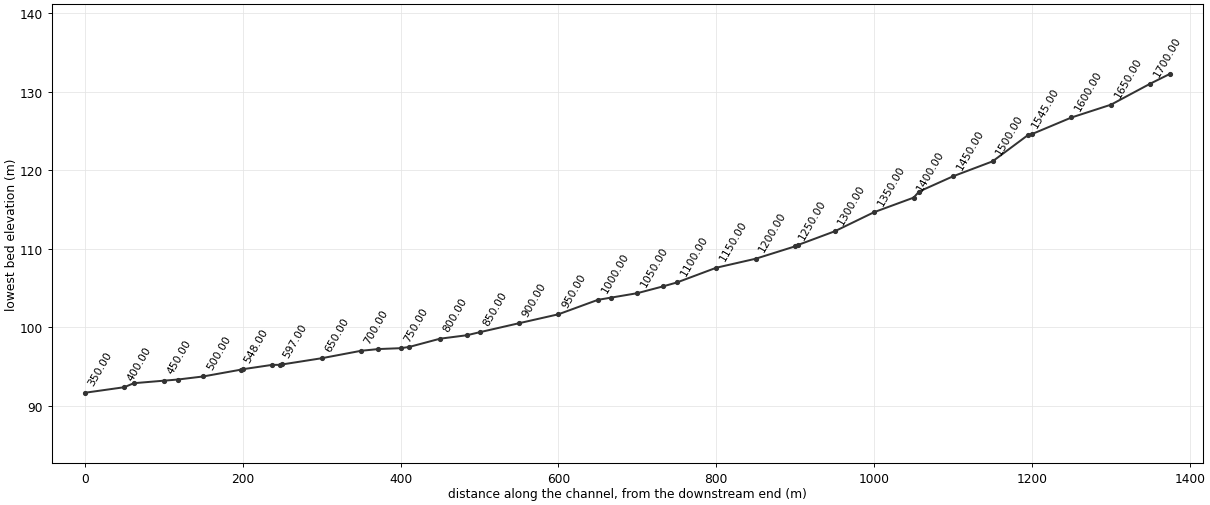
--- DDC.prj (project) ---

Proj Title=DUNDAE
Current Plan=p01
Default Exp/Contr=.3,.1
SI Units
Geom File=g01
Flow File=f01
Plan File=p01
Y Axis Title=Elevation
X Axis Title(PF)=Main Channel Distance
X Axis Title(XS)=Station
BEGIN DESCRIPTION:
           BACK WATER COMPUTATION
      APPLICATION OF HEC-2 BY Samju Construction Engineering
      doondae-ch: 10,20,30,50,80 yr
END DESCRIPTION:
DSS Export Rating Curves= 0
DSS Export Rating Curve Sorted= 0
DSS Export Volume Flow Curves= 0
DXF OffsetX= 0
DXF OffsetY= 0
DXF ScaleX= 1
DXF ScaleY= 10

--- DDC.p01 (plan) ---

Plan Title=Imported Plan 01
Version=Version 3.0.1  Mar 2001
Short Identifier=Imported Pla
Geom File=g01
Flow File=f01
Subcritical Flow
K Sum by GR= 0
Std Step Tol= 0.003
Critical Tol= 0.003
Num of Std Step Trials= 20
Max Error Tol= 0.1
Flow Tol Ratio= 0.001
Split Flow NTrial= 30
Split Flow Tol= 0.02
Split Flow Ratio= 0.02
Log Output Level= 0
Friction Slope Method= 1
Unsteady Friction Slope Method= 2
Parabolic Critical Depth
Global Vel Dist= 0 , 0 , 0
Global Log Level= 0
CheckData=True
Encroach Param=-1 ,0,0, 0
Computation Interval=1HOUR
Output Interval=1HOUR
Run HTab= 0
Run UNet= 0
Run PostProcess= 0
UNET Theta= 1
UNET ZTol= 0.02
UNET ZSATol= 0.1
UNET MxIter= 20
UNET MaxInSteps= 20
UNET DtIC= 0
UNET DtMin= 0
UNET MaxCRTS= 20
UNET WFStab= 2
UNET SFStab= 1
UNET WFX= 1
UNET SFX= 1
UNET Convert EG Bridges=-1
UNET Use Existing IB Tables=-1
Instantaneous Interval=1HOUR
Write IC File= 0
Write Velocity= 0
Write Detailed= 0

--- DDC.f01 (steady flow) ---

Flow Title=Imported Flow 01
Version=Version 3.0.1  Mar 2001
Number of Profiles= 5
Profile Names=10YR,20YR,30YR,50YR,80YR
River Rch & RM=RIVER-1,Reach-1         ,1725.00
    7.43    8.19    8.63    9.18    9.69
River Rch & RM=RIVER-1,Reach-1         ,1000.00
    14.5   15.97   16.84   17.92   18.92
Boundary for River Rch & Prof#=RIVER-1,Reach-1         , 1
Up Type= 0
Dn Type= 3
Dn Slope=.034
Boundary for River Rch & Prof#=RIVER-1,Reach-1         , 2
Up Type= 0
Dn Type= 3
Dn Slope=.034
Boundary for River Rch & Prof#=RIVER-1,Reach-1         , 3
Up Type= 0
Dn Type= 3
Dn Slope=.034
Boundary for River Rch & Prof#=RIVER-1,Reach-1         , 4
Up Type= 0
Dn Type= 3
Dn Slope=.034
Boundary for River Rch & Prof#=RIVER-1,Reach-1         , 5
Up Type= 0
Dn Type= 3
Dn Slope=.034
DSS Import GetInterval= 0
DSS Import GetPeak= 0
DSS Import FillOption= 0

--- DDC.g01 (geometry) ---

Geom Title=Imported Geom 01
Version=Version 3.0.1  Mar 2001

River Reach=RIVER-1         ,Reach-1
Reach XY= 2
              .5             .95              .5             .05

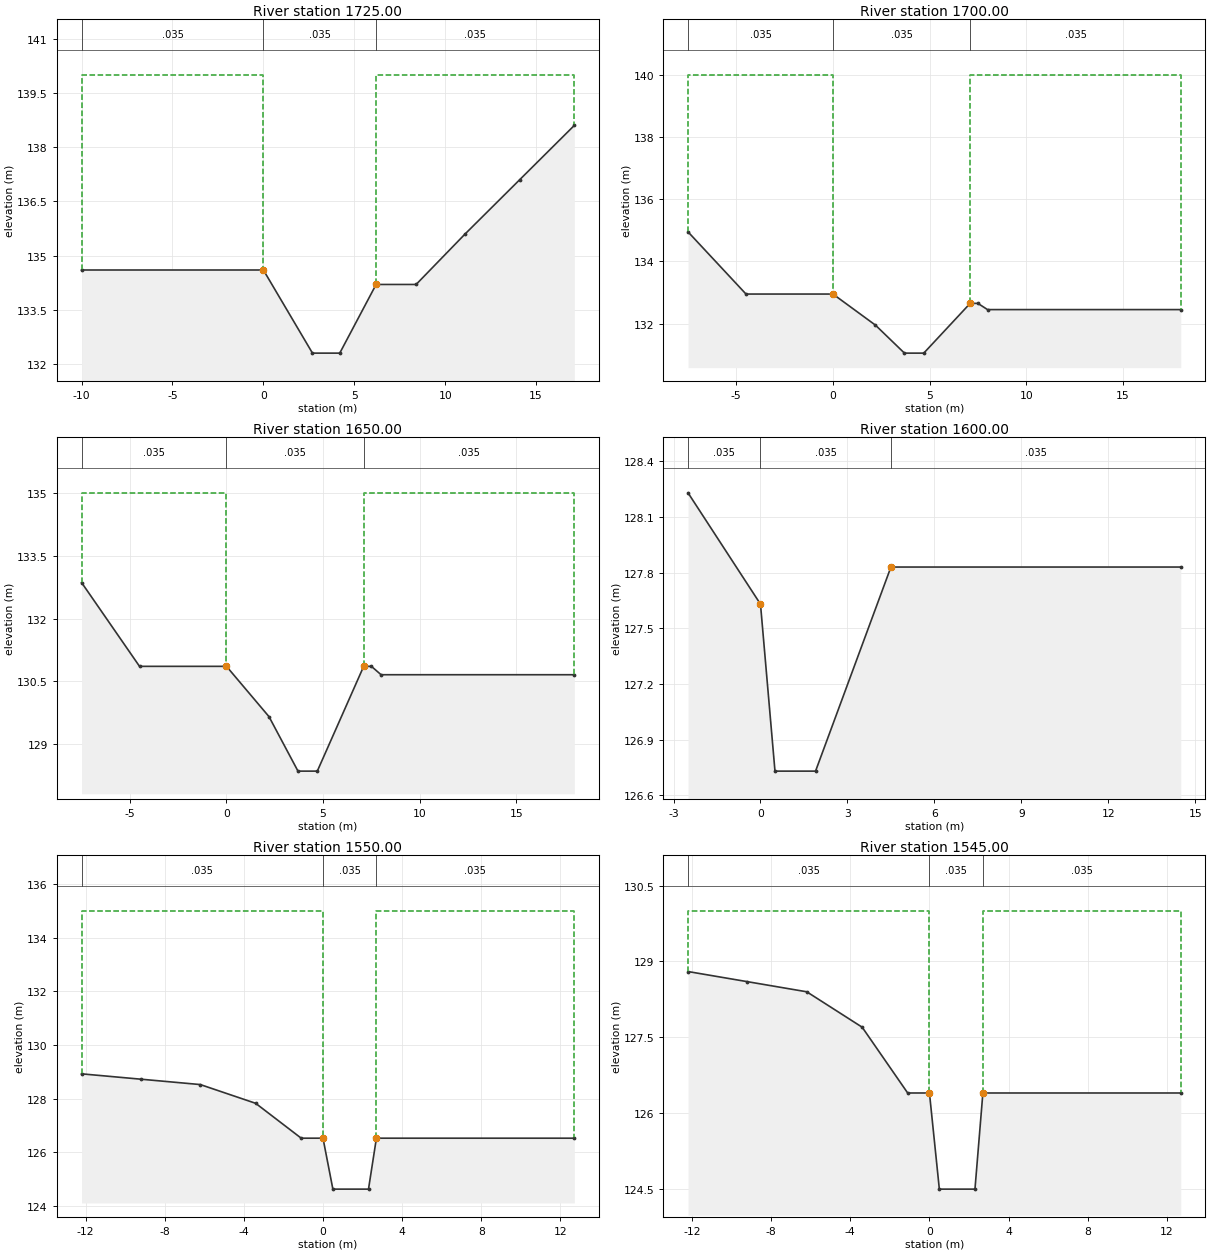
Type RM Length L Ch R = 1 ,1725.00 ,25,25,25
BEGIN DESCRIPTION:
34.025
END DESCRIPTION:
#Sta/Elev= 9
     -10   134.6       0   134.6     2.7   132.3     4.2   132.3     6.2   134.2
     8.4   134.2    11.1   135.6    14.1   137.1    17.1   138.6
#Mann= 3 , 0 , 0
     -10    .035       0       0    .035       0     6.2    .035       0
#XS Ineff= 2 , 0
               0     140     6.2             140
Permanent Ineff=
       F       F
#Block Obstruct= 2 , 0
                             6.2
Bank Sta=0,6.2
XS Rating Curve= 0
Exp/Cntr=.3,.1

Type RM Length L Ch R = 1 ,1700.00 ,50,50,50
BEGIN DESCRIPTION:
34
END DESCRIPTION:
#Sta/Elev= 10
    -7.5  134.95    -4.5  132.95       0  132.95     2.2  131.95     3.7  131.05
     4.7  131.05     7.1  132.65     7.5  132.65       8  132.45      18  132.45
#Mann= 3 , 0 , 0
    -7.5    .035       0       0    .035       0     7.1    .035       0
#XS Ineff= 2 , 0
               0     140     7.1             140
Permanent Ineff=
       F       F
#Block Obstruct= 2 , 0
                             7.1
Bank Sta=0,7.1
XS Rating Curve= 0
Exp/Cntr=.3,.1

Type RM Length L Ch R = 1 ,1650.00 ,50,50,50
BEGIN DESCRIPTION:
33
END DESCRIPTION:
#Sta/Elev= 10
    -7.5  132.86    -4.5  130.86       0  130.86     2.2  129.66     3.7  128.36
     4.7  128.36     7.1  130.86     7.5  130.86       8  130.66      18  130.66
#Mann= 3 , 0 , 0
    -7.5    .035       0       0    .035       0     7.1    .035       0
#XS Ineff= 2 , 0
               0     135     7.1             135
Permanent Ineff=
       F       F
#Block Obstruct= 2 , 0
                             7.1
Bank Sta=0,7.1
XS Rating Curve= 0
Exp/Cntr=.3,.1

Type RM Length L Ch R = 1 ,1600.00 ,50,50,50
BEGIN DESCRIPTION:
32
END DESCRIPTION:
#Sta/Elev= 6
    -2.5  128.23       0  127.63      .5  126.73     1.9  126.73     4.5  127.83
    14.5  127.83
#Mann= 3 , 0 , 0
    -2.5    .035       0       0    .035       0     4.5    .035       0
#XS Ineff= 2 , 0
               0     135     4.5             135
Permanent Ineff=
       F       F
#Block Obstruct= 2 , 0
                             4.5
Bank Sta=0,4.5
XS Rating Curve= 0
Exp/Cntr=.3,.1

Type RM Length L Ch R = 1 ,1550.00 ,5,5,5
BEGIN DESCRIPTION:
31
END DESCRIPTION:
#Sta/Elev= 10
   -12.2  128.92    -9.2  128.72    -6.2  128.52    -3.4  127.82    -1.1  126.52
       0  126.52      .5  124.62     2.3  124.62     2.7  126.52    12.7  126.52
#Mann= 3 , 0 , 0
   -12.2    .035       0       0    .035       0     2.7    .035       0
#XS Ineff= 2 , 0
               0     135     2.7             135
Permanent Ineff=
       F       F
#Block Obstruct= 2 , 0
                             2.7
Bank Sta=0,2.7
XS Rating Curve= 0
Exp/Cntr=.3,.1

Type RM Length L Ch R = 1 ,1545.00 ,45,45,45
BEGIN DESCRIPTION:
30.045
END DESCRIPTION:
#Sta/Elev= 10
   -12.2   128.8    -9.2   128.6    -6.2   128.4    -3.4   127.7    -1.1   126.4
       0   126.4      .5   124.5     2.3   124.5     2.7   126.4    12.7   126.4
#Mann= 3 , 0 , 0
   -12.2    .035       0       0    .035       0     2.7    .035       0
#XS Ineff= 2 , 0
               0     130     2.7             130
Permanent Ineff=
       F       F
#Block Obstruct= 2 , 0
                             2.7
Bank Sta=0,2.7
XS Rating Curve= 0
Exp/Cntr=.3,.1

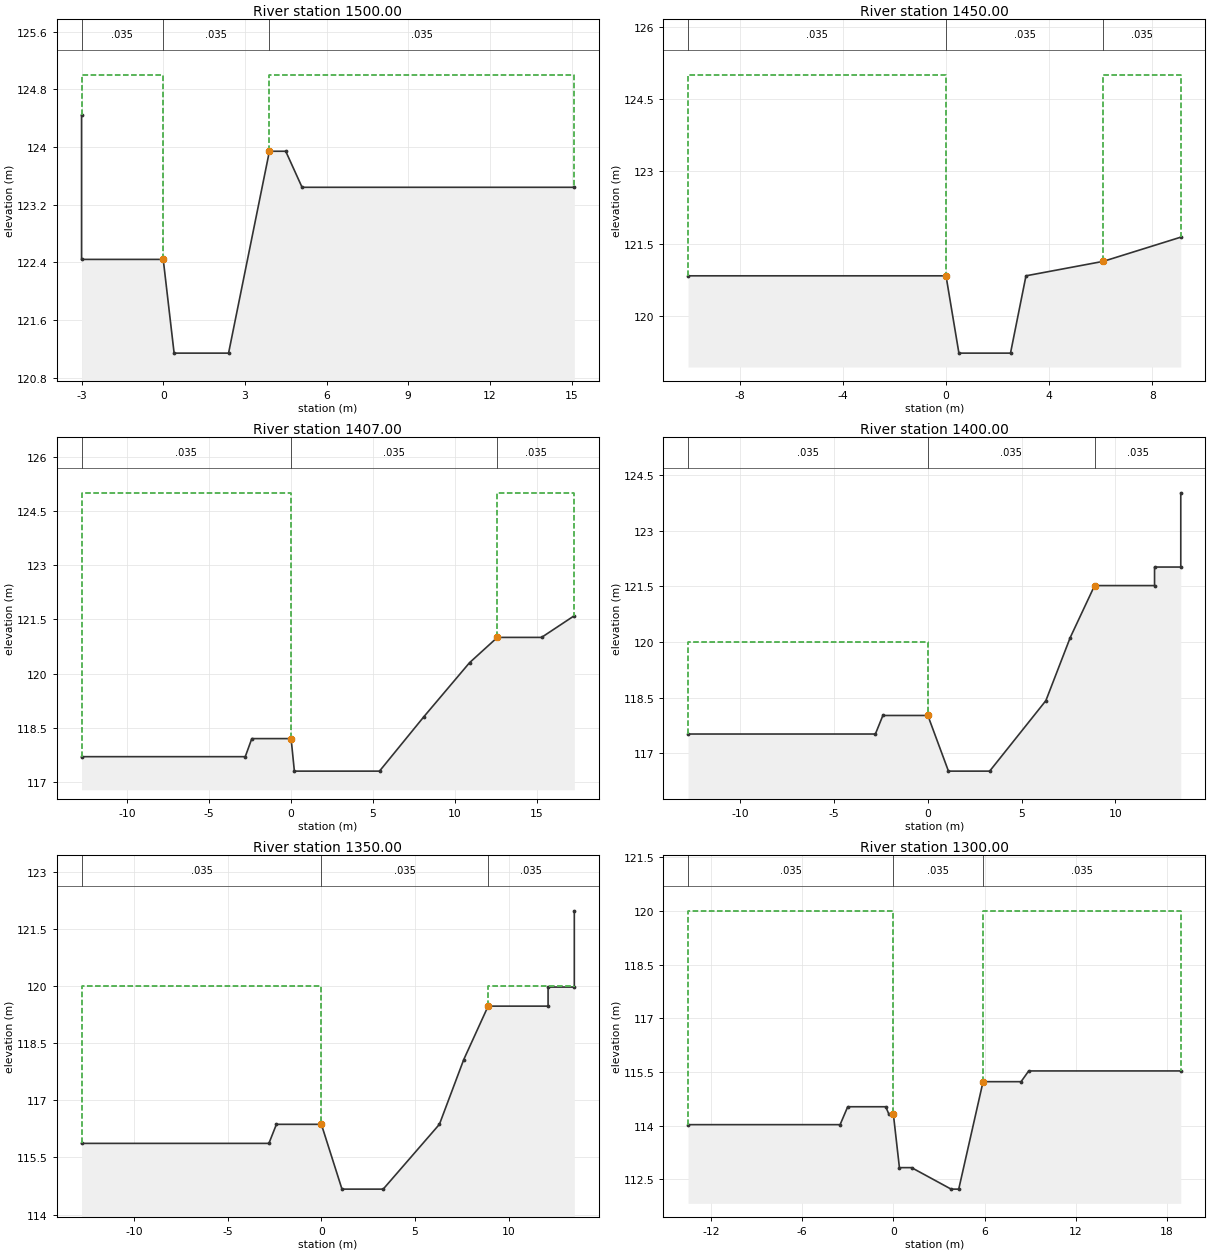
Type RM Length L Ch R = 1 ,1500.00 ,50,50,50
BEGIN DESCRIPTION:
30
END DESCRIPTION:
#Sta/Elev= 9
      -3  124.44      -3  122.44       0  122.44      .4  121.14     2.4  121.14
     3.9  123.94     4.5  123.94     5.1  123.44    15.1  123.44
#Mann= 3 , 0 , 0
      -3    .035       0       0    .035       0     3.9    .035       0
#XS Ineff= 2 , 0
               0     125     3.9             125
Permanent Ineff=
       F       F
#Block Obstruct= 2 , 0
                             3.9
Bank Sta=0,3.9
XS Rating Curve= 0
Exp/Cntr=.3,.1

Type RM Length L Ch R = 1 ,1450.00 ,43,43,43
BEGIN DESCRIPTION:
29
END DESCRIPTION:
#Sta/Elev= 7
     -10  120.84       0  120.84      .5  119.24     2.5  119.24     3.1  120.84
     6.1  121.14     9.1  121.64
#Mann= 3 , 0 , 0
     -10    .035       0       0    .035       0     6.1    .035       0
#XS Ineff= 2 , 0
               0     125     6.1             125
Permanent Ineff=
       F       F
#Block Obstruct= 2 , 0
                             6.1
Bank Sta=0,6.1
XS Rating Curve= 0
Exp/Cntr=.3,.1

Type RM Length L Ch R = 1 ,1407.00 ,7,7,7
BEGIN DESCRIPTION:
28.007
END DESCRIPTION:
#Sta/Elev= 11
   -12.8   117.7    -2.8   117.7    -2.4   118.2       0   118.2      .2   117.3
     5.4   117.3     8.1   118.8    10.9   120.3    12.6     121    15.3     121
    17.3   121.6
#Mann= 3 , 0 , 0
   -12.8    .035       0       0    .035       0    12.6    .035       0
#XS Ineff= 2 , 0
               0     125    12.6             125
Permanent Ineff=
       F       F
#Block Obstruct= 2 , 0
                            12.6
Bank Sta=0,12.6
XS Rating Curve= 0
Exp/Cntr=.3,.1

Type RM Length L Ch R = 1 ,1400.00 ,50,50,50
BEGIN DESCRIPTION:
28
END DESCRIPTION:
#Sta/Elev= 13
   -12.8  117.52    -2.8  117.52    -2.4  118.02       0  118.02     1.1  116.52
     3.3  116.52     6.3  118.42     7.6  120.12     8.9  121.52    12.1  121.52
    12.1  122.02    13.5  122.02    13.5  124.02
#Mann= 3 , 0 , 0
   -12.8    .035       0       0    .035       0     8.9    .035       0
#XS Ineff= 2 , 0
               0     120     8.9             120
Permanent Ineff=
       F       F
#Block Obstruct= 2 , 0
                             8.9
Bank Sta=0,8.9
XS Rating Curve= 0
Exp/Cntr=.3,.1

Type RM Length L Ch R = 1 ,1350.00 ,50,50,50
BEGIN DESCRIPTION:
27
END DESCRIPTION:
#Sta/Elev= 13
   -12.8  115.87    -2.8  115.87    -2.4  116.37       0  116.37     1.1  114.67
     3.3  114.67     6.3  116.37     7.6  118.07     8.9  119.47    12.1  119.47
    12.1  119.97    13.5  119.97    13.5  121.97
#Mann= 3 , 0 , 0
   -12.8    .035       0       0    .035       0     8.9    .035       0
#XS Ineff= 2 , 0
               0     120     8.9             120
Permanent Ineff=
       F       F
#Block Obstruct= 2 , 0
                             8.9
Bank Sta=0,8.9
XS Rating Curve= 0
Exp/Cntr=.3,.1

Type RM Length L Ch R = 1 ,1300.00 ,47,47,47
BEGIN DESCRIPTION:
26
END DESCRIPTION:
#Sta/Elev= 14
   -13.5  114.03    -3.5  114.03      -3  114.53     -.5  114.53     -.3  114.33
       0  114.33      .4  112.83     1.2  112.83     3.8  112.23     4.3  112.23
     5.9  115.23     8.4  115.23     8.9  115.53    18.9  115.53
#Mann= 3 , 0 , 0
   -13.5    .035       0       0    .035       0     5.9    .035       0
#XS Ineff= 2 , 0
               0     120     5.9             120
Permanent Ineff=
       F       F
#Block Obstruct= 2 , 0
                             5.9
Bank Sta=0,5.9
XS Rating Curve= 0
Exp/Cntr=.3,.1

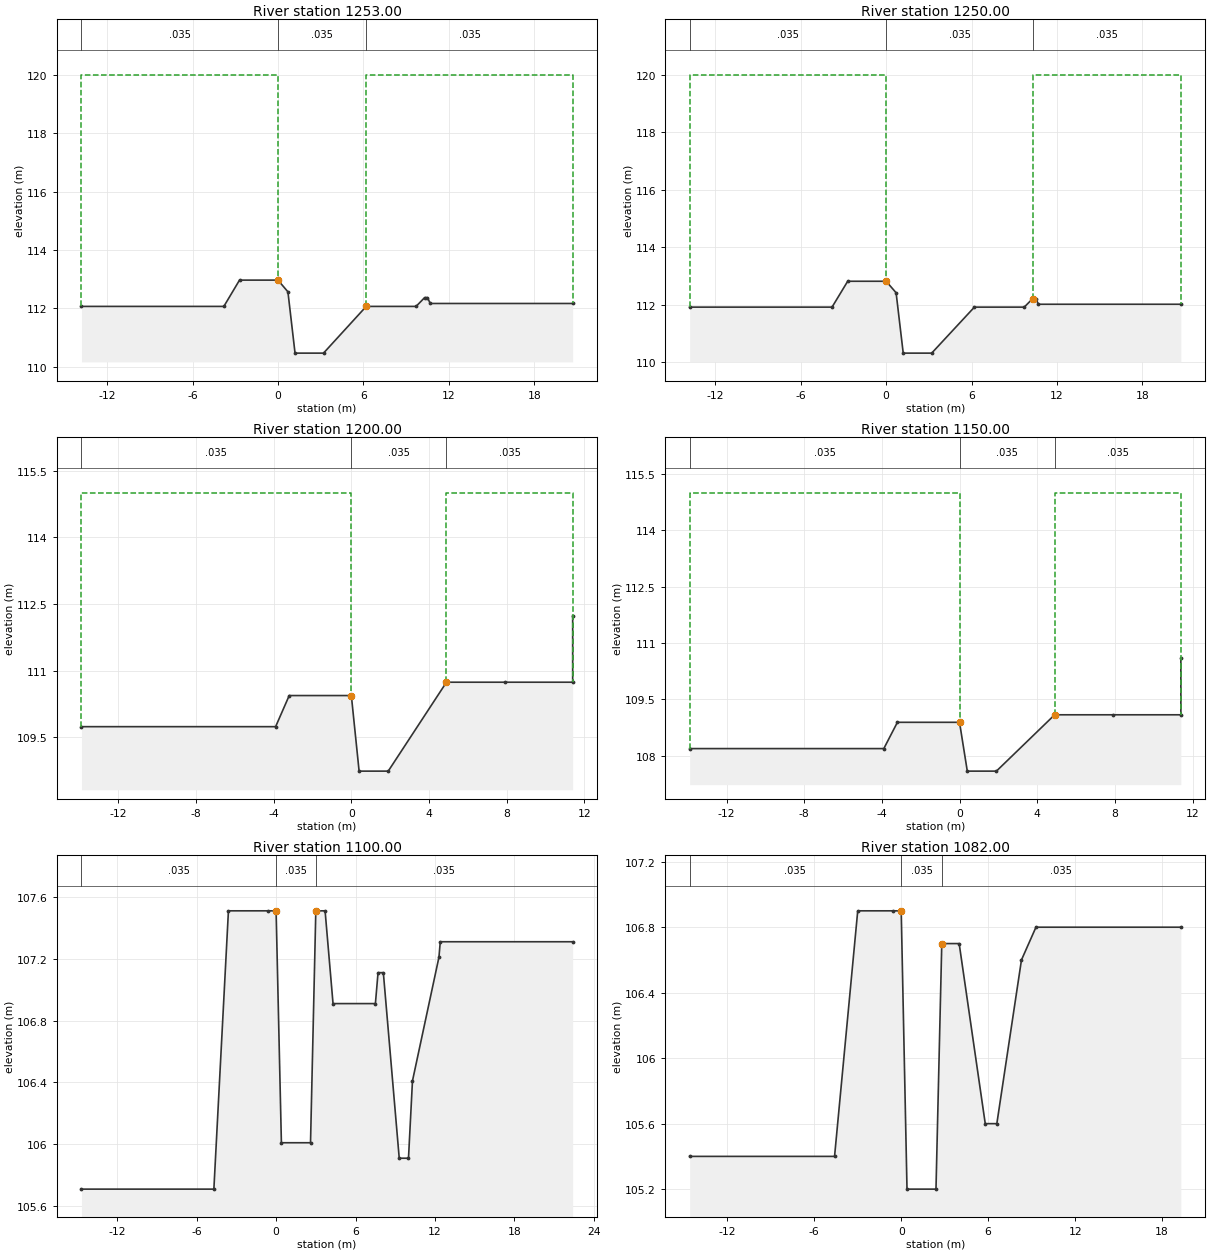
Type RM Length L Ch R = 1 ,1253.00 ,3,3,3
BEGIN DESCRIPTION:
25.003
END DESCRIPTION:
#Sta/Elev= 13
   -13.8  112.07    -3.8  112.07    -2.7  112.97       0  112.97      .7  112.57
     1.2  110.47     3.2  110.47     6.2  112.07     9.7  112.07    10.3  112.37
    10.5  112.37    10.7  112.17    20.7  112.17
#Mann= 3 , 0 , 0
   -13.8    .035       0       0    .035       0     6.2    .035       0
#XS Ineff= 2 , 0
               0     120     6.2             120
Permanent Ineff=
       F       F
#Block Obstruct= 2 , 0
                             6.2
Bank Sta=0,6.2
XS Rating Curve= 0
Exp/Cntr=.3,.1

Type RM Length L Ch R = 1 ,1250.00 ,50,50,50
BEGIN DESCRIPTION:
25
END DESCRIPTION:
#Sta/Elev= 13
   -13.8  111.92    -3.8  111.92    -2.7  112.82       0  112.82      .7  112.42
     1.2  110.32     3.2  110.32     6.2  111.92     9.7  111.92    10.3  112.22
    10.5  112.22    10.7  112.02    20.7  112.02
#Mann= 3 , 0 , 0
   -13.8    .035       0       0    .035       0    10.3    .035       0
#XS Ineff= 2 , 0
               0     120    10.3             120
Permanent Ineff=
       F       F
#Block Obstruct= 2 , 0
                            10.3
Bank Sta=0,10.3
XS Rating Curve= 0
Exp/Cntr=.3,.1

Type RM Length L Ch R = 1 ,1200.00 ,50,50,50
BEGIN DESCRIPTION:
24
END DESCRIPTION:
#Sta/Elev= 10
   -13.9  109.74    -3.9  109.74    -3.2  110.44       0  110.44      .4  108.74
     1.9  108.74     4.9  110.74     7.9  110.74    11.4  110.74    11.4  112.24
#Mann= 3 , 0 , 0
   -13.9    .035       0       0    .035       0     4.9    .035       0
#XS Ineff= 2 , 0
               0     115     4.9             115
Permanent Ineff=
       F       F
#Block Obstruct= 2 , 0
                             4.9
Bank Sta=0,4.9
XS Rating Curve= 0
Exp/Cntr=.3,.1

Type RM Length L Ch R = 1 ,1150.00 ,50,50,50
BEGIN DESCRIPTION:
23
END DESCRIPTION:
#Sta/Elev= 10
   -13.9  108.19    -3.9  108.19    -3.2  108.89       0  108.89      .4  107.59
     1.9  107.59     4.9  109.09     7.9  109.09    11.4  109.09    11.4  110.59
#Mann= 3 , 0 , 0
   -13.9    .035       0       0    .035       0     4.9    .035       0
#XS Ineff= 2 , 0
               0     115     4.9             115
Permanent Ineff=
       F       F
#Block Obstruct= 2 , 0
                             4.9
Bank Sta=0,4.9
XS Rating Curve= 0
Exp/Cntr=.3,.1

Type RM Length L Ch R = 1 ,1100.00 ,18,18,18
BEGIN DESCRIPTION:
22
END DESCRIPTION:
#Sta/Elev= 19
   -14.7  105.71    -4.7  105.71    -3.6  107.51     -.6  107.51       0  107.51
      .4  106.01     2.6  106.01       3  107.51     3.7  107.51     4.3  106.91
     7.5  106.91     7.7  107.11     8.1  107.11     9.3  105.91      10  105.91
    10.3  106.41    12.3  107.21    12.4  107.31    22.4  107.31
#Mann= 3 , 0 , 0
   -14.7    .035       0       0    .035       0       3    .035       0
#XS Ineff= 2 , 0
               0     115       3             115
Permanent Ineff=
       F       F
#Block Obstruct= 2 , 0
                               3
Bank Sta=0,3
XS Rating Curve= 0
Exp/Cntr=.3,.1

Type RM Length L Ch R = 1 ,1082.00 ,32,32,32
BEGIN DESCRIPTION:
21.032
END DESCRIPTION:
#Sta/Elev= 14
   -14.6   105.4    -4.6   105.4      -3   106.9     -.6   106.9       0   106.9
      .4   105.2     2.4   105.2     2.8   106.7       4   106.7     5.8   105.6
     6.6   105.6     8.3   106.6     9.3   106.8    19.3   106.8
#Mann= 3 , 0 , 0
   -14.6    .035       0       0    .035       0     2.8    .035       0
#XS Ineff= 2 , 0
               0     115     2.8             115
Permanent Ineff=
       F       F
#Block Obstruct= 2 , 0
                             2.8
Bank Sta=0,2.8
XS Rating Curve= 0
Exp/Cntr=.3,.1

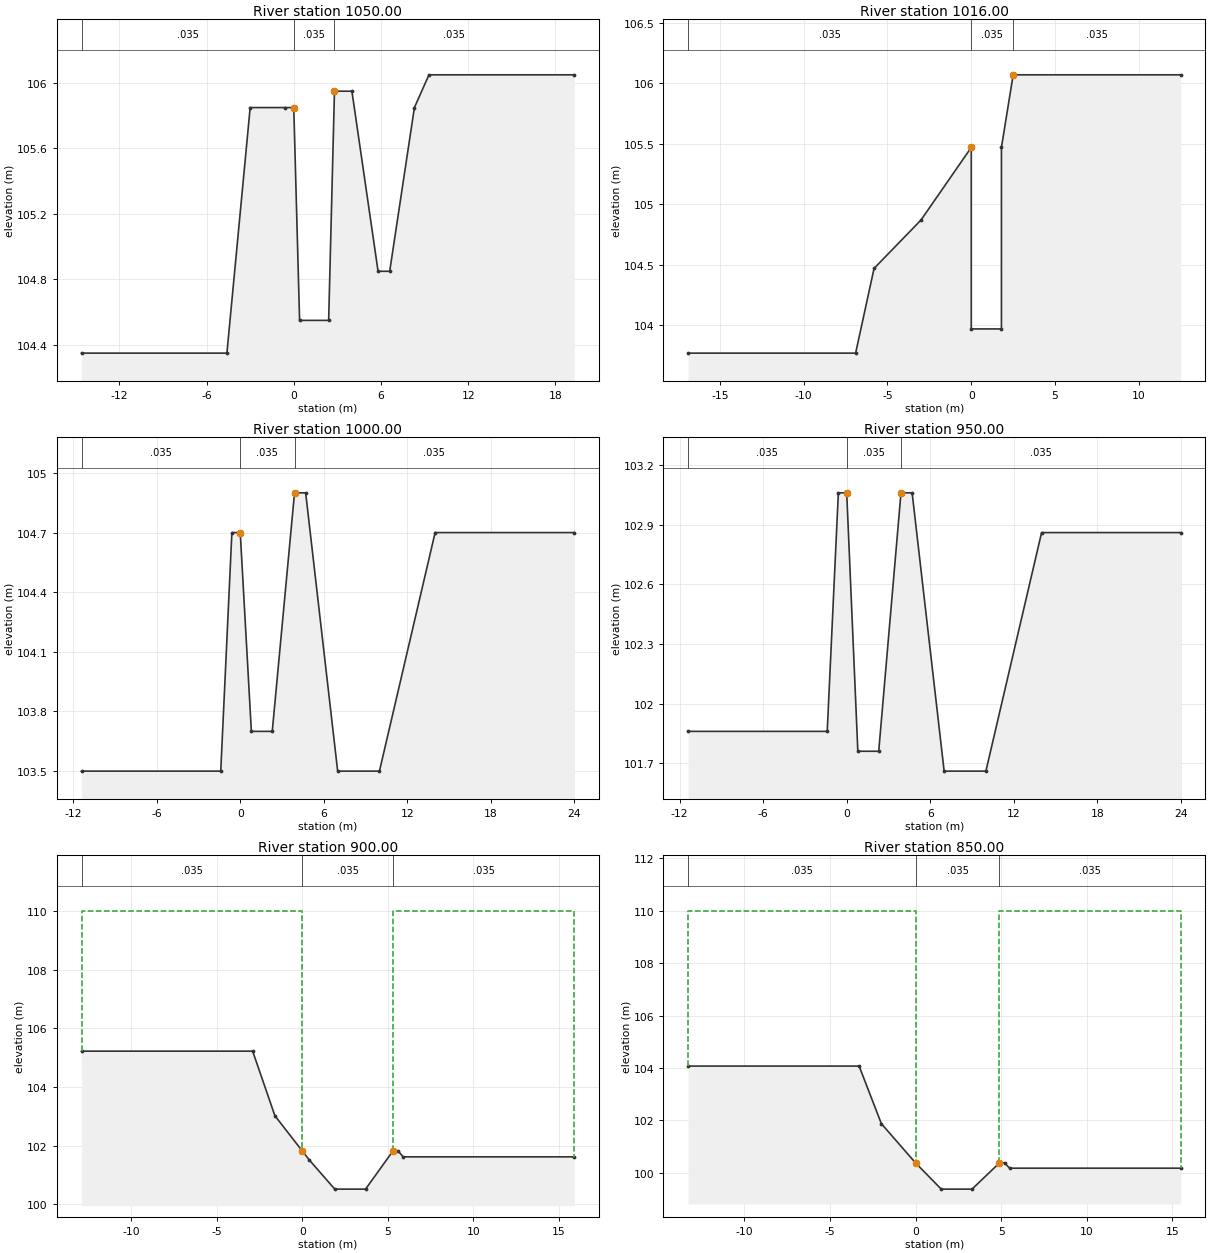
Type RM Length L Ch R = 1 ,1050.00 ,34,34,34
BEGIN DESCRIPTION:
21
END DESCRIPTION:
#Sta/Elev= 14
   -14.6  104.35    -4.6  104.35      -3  105.85     -.6  105.85       0  105.85
      .4  104.55     2.4  104.55     2.8  105.95       4  105.95     5.8  104.85
     6.6  104.85     8.3  105.85     9.3  106.05    19.3  106.05
#Mann= 3 , 0 , 0
   -14.6    .035       0       0    .035       0     2.8    .035       0
#XS Ineff= 2 , 0
               0     115     2.8             115
Permanent Ineff=
       F       F
#Block Obstruct= 2 , 0
                             2.8
Bank Sta=0,2.8
XS Rating Curve= 0
Exp/Cntr=.3,.1

Type RM Length L Ch R = 1 ,1016.00 ,16,16,16
BEGIN DESCRIPTION:
20.016
END DESCRIPTION:
#Sta/Elev= 10
   -16.9  103.77    -6.9  103.77    -5.8  104.47      -3  104.87       0  105.47
       0  103.97     1.8  103.97     1.8  105.47     2.5  106.07    12.5  106.07
#Mann= 3 , 0 , 0
   -16.9    .035       0       0    .035       0     2.5    .035       0
#XS Ineff= 2 , 0
               0     115     2.5             115
Permanent Ineff=
       F       F
#Block Obstruct= 2 , 0
                             2.5
Bank Sta=0,2.5
XS Rating Curve= 0
Exp/Cntr=.3,.1

Type RM Length L Ch R = 1 ,1000.00 ,50,50,50
BEGIN DESCRIPTION:
20
END DESCRIPTION:
#Sta/Elev= 12
   -11.4   103.5    -1.4   103.5     -.6   104.7       0   104.7      .8   103.7
     2.3   103.7     3.9   104.9     4.7   104.9       7   103.5      10   103.5
      14   104.7      24   104.7
#Mann= 3 , 0 , 0
   -11.4    .035       0       0    .035       0     3.9    .035       0
#XS Ineff= 2 , 0
               0     115     3.9             115
Permanent Ineff=
       F       F
#Block Obstruct= 2 , 0
                             3.9
Bank Sta=0,3.9
XS Rating Curve= 0
Exp/Cntr=.3,.1

Type RM Length L Ch R = 1 ,950.00  ,50,50,50
BEGIN DESCRIPTION:
19
END DESCRIPTION:
#Sta/Elev= 12
   -11.4  101.86    -1.4  101.86     -.6  103.06       0  103.06      .8  101.76
     2.3  101.76     3.9  103.06     4.7  103.06       7  101.66      10  101.66
      14  102.86      24  102.86
#Mann= 3 , 0 , 0
   -11.4    .035       0       0    .035       0     3.9    .035       0
#XS Ineff= 2 , 0
               0     110     3.9             110
Permanent Ineff=
       F       F
#Block Obstruct= 2 , 0
                             3.9
Bank Sta=0,3.9
XS Rating Curve= 0
Exp/Cntr=.3,.1

Type RM Length L Ch R = 1 ,900.00  ,50,50,50
BEGIN DESCRIPTION:
18
END DESCRIPTION:
#Sta/Elev= 11
   -12.9  105.22    -2.9  105.22    -1.6  103.02       0  101.82      .4  101.52
     1.9  100.52     3.7  100.52     5.3  101.82     5.6  101.82     5.9  101.62
    15.9  101.62
#Mann= 3 , 0 , 0
   -12.9    .035       0       0    .035       0     5.3    .035       0
#XS Ineff= 2 , 0
               0     110     5.3             110
Permanent Ineff=
       F       F
#Block Obstruct= 2 , 0
                             5.3
Bank Sta=0,5.3
XS Rating Curve= 0
Exp/Cntr=.3,.1

Type RM Length L Ch R = 1 ,850.00  ,16,16,16
BEGIN DESCRIPTION:
17
END DESCRIPTION:
#Sta/Elev= 10
   -13.3  104.07    -3.3  104.07      -2  101.87       0  100.37     1.5   99.37
     3.3   99.37     4.9  100.37     5.2  100.37     5.5  100.17    15.5  100.17
#Mann= 3 , 0 , 0
   -13.3    .035       0       0    .035       0     4.9    .035       0
#XS Ineff= 2 , 0
               0     110     4.9             110
Permanent Ineff=
       F       F
#Block Obstruct= 2 , 0
                             4.9
Bank Sta=0,4.9
XS Rating Curve= 0
Exp/Cntr=.3,.1

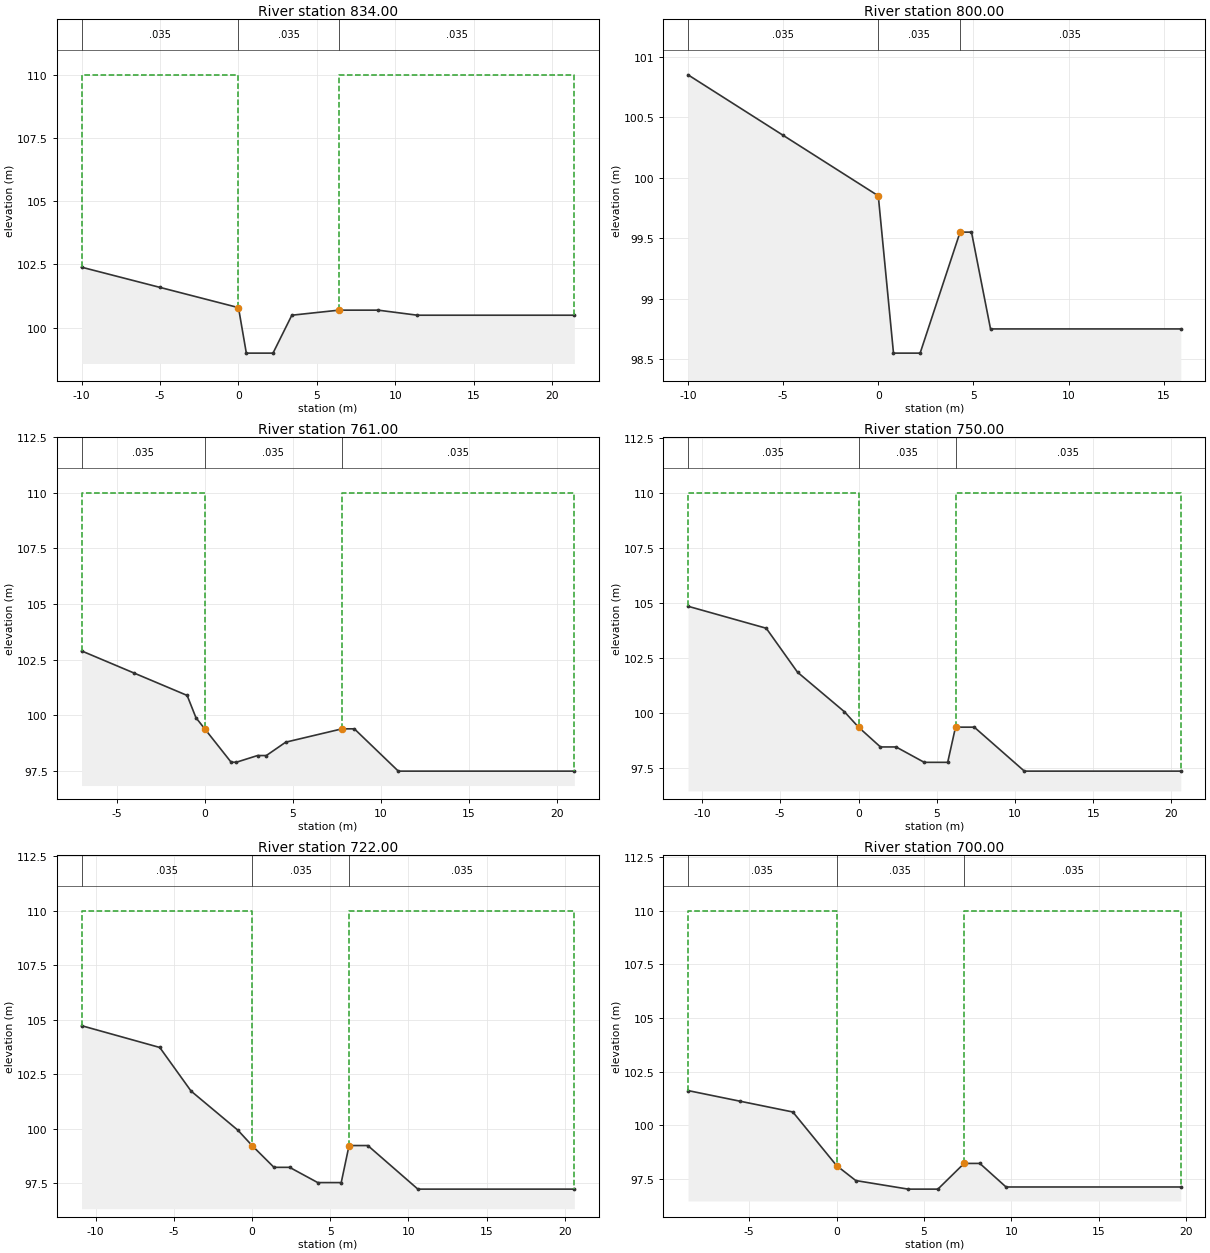
Type RM Length L Ch R = 1 ,834.00  ,34,34,34
BEGIN DESCRIPTION:
16.034
END DESCRIPTION:
#Sta/Elev= 10
     -10  102.39      -5  101.59       0  100.79      .5   98.99     2.2   98.99
     3.4  100.49     6.4  100.69     8.9  100.69    11.4  100.49    21.4  100.49
#Mann= 3 , 0 , 0
     -10    .035       0       0    .035       0     6.4    .035       0
#XS Ineff= 2 , 0
               0     110     6.4             110
Permanent Ineff=
       F       F
#Block Obstruct= 2 , 0
                             6.4
Bank Sta=0,6.4
XS Rating Curve= 0
Exp/Cntr=.3,.1

Type RM Length L Ch R = 1 ,800.00  ,39,39,39
BEGIN DESCRIPTION:
16
END DESCRIPTION:
#Sta/Elev= 9
     -10  100.85      -5  100.35       0   99.85      .8   98.55     2.2   98.55
     4.3   99.55     4.9   99.55     5.9   98.75    15.9   98.75
#Mann= 3 , 0 , 0
     -10    .035       0       0    .035       0     4.3    .035       0
#XS Ineff= 2 , 0
               0     110     4.3             110
Permanent Ineff=
       F       F
#Block Obstruct= 2 , 0
                             4.3
Bank Sta=0,4.3
XS Rating Curve= 0
Exp/Cntr=.3,.1

Type RM Length L Ch R = 1 ,761.00  ,11,11,11
BEGIN DESCRIPTION:
15.011
END DESCRIPTION:
#Sta/Elev= 14
      -7   102.9      -4   101.9      -1   100.9     -.5    99.9       0    99.4
     1.5    97.9     1.8    97.9       3    98.2     3.5    98.2     4.6    98.8
     7.8    99.4     8.5    99.4      11    97.5      21    97.5
#Mann= 3 , 0 , 0
      -7    .035       0       0    .035       0     7.8    .035       0
#XS Ineff= 2 , 0
               0     110     7.8             110
Permanent Ineff=
       F       F
#Block Obstruct= 2 , 0
                             7.8
Bank Sta=0,7.8
XS Rating Curve= 0
Exp/Cntr=.3,.1

Type RM Length L Ch R = 1 ,750.00  ,28,28,28
BEGIN DESCRIPTION:
15
END DESCRIPTION:
#Sta/Elev= 13
   -10.9  104.84    -5.9  103.84    -3.9  101.84     -.9  100.04       0   99.34
     1.4   98.44     2.4   98.44     4.2   97.74     5.7   97.74     6.2   99.34
     7.4   99.34    10.6   97.34    20.6   97.34
#Mann= 3 , 0 , 0
   -10.9    .035       0       0    .035       0     6.2    .035       0
#XS Ineff= 2 , 0
               0     110     6.2             110
Permanent Ineff=
       F       F
#Block Obstruct= 2 , 0
                             6.2
Bank Sta=0,6.2
XS Rating Curve= 0
Exp/Cntr=.3,.1

Type RM Length L Ch R = 1 ,722.00  ,22,22,22
BEGIN DESCRIPTION:
14.022
END DESCRIPTION:
#Sta/Elev= 13
   -10.9  104.73    -5.9  103.73    -3.9  101.73     -.9   99.93       0   99.23
     1.4   98.23     2.4   98.23     4.2   97.53     5.7   97.53     6.2   99.23
     7.4   99.23    10.6   97.23    20.6   97.23
#Mann= 3 , 0 , 0
   -10.9    .035       0       0    .035       0     6.2    .035       0
#XS Ineff= 2 , 0
               0     110     6.2             110
Permanent Ineff=
       F       F
#Block Obstruct= 2 , 0
                             6.2
Bank Sta=0,6.2
XS Rating Curve= 0
Exp/Cntr=.3,.1

Type RM Length L Ch R = 1 ,700.00  ,50,50,50
BEGIN DESCRIPTION:
14
END DESCRIPTION:
#Sta/Elev= 11
    -8.5  101.61    -5.5  101.11    -2.5  100.61       0   98.11     1.1   97.41
     4.1   97.01     5.8   97.01     7.3   98.21     8.2   98.21     9.7   97.11
    19.7   97.11
#Mann= 3 , 0 , 0
    -8.5    .035       0       0    .035       0     7.3    .035       0
#XS Ineff= 2 , 0
               0     110     7.3             110
Permanent Ineff=
       F       F
#Block Obstruct= 2 , 0
                             7.3
Bank Sta=0,7.3
XS Rating Curve= 0
Exp/Cntr=.3,.1

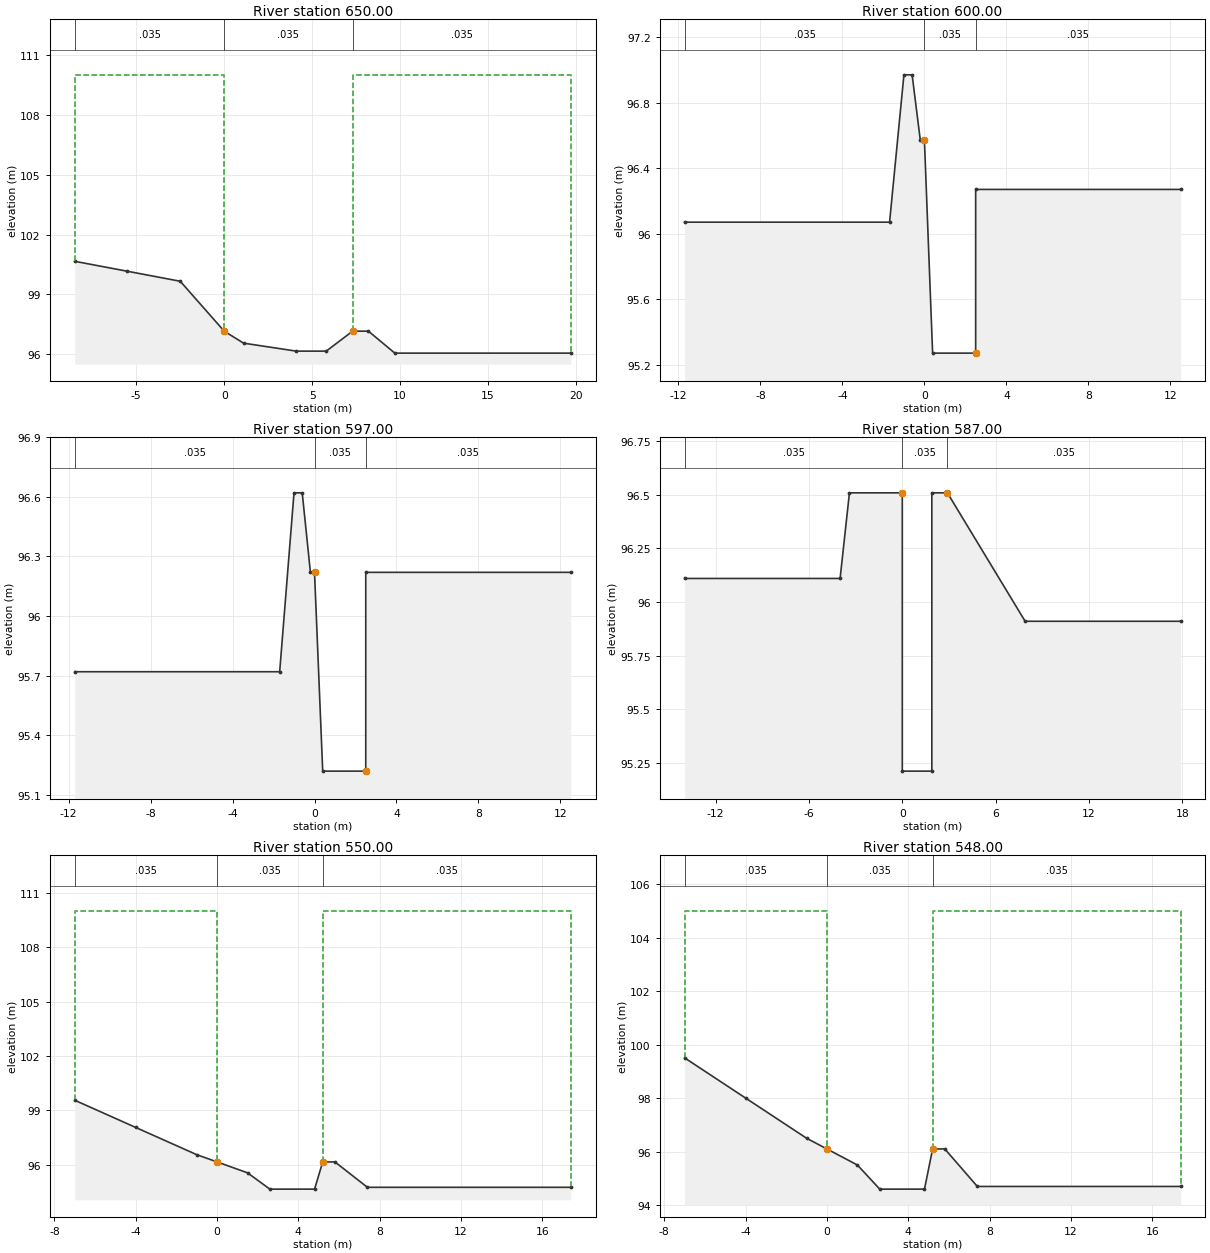
Type RM Length L Ch R = 1 ,650.00  ,50,50,50
BEGIN DESCRIPTION:
13
END DESCRIPTION:
#Sta/Elev= 11
    -8.5  100.66    -5.5  100.16    -2.5   99.66       0   97.16     1.1   96.56
     4.1   96.16     5.8   96.16     7.3   97.16     8.2   97.16     9.7   96.06
    19.7   96.06
#Mann= 3 , 0 , 0
    -8.5    .035       0       0    .035       0     7.3    .035       0
#XS Ineff= 2 , 0
               0     110     7.3             110
Permanent Ineff=
       F       F
#Block Obstruct= 2 , 0
                             7.3
Bank Sta=0,7.3
XS Rating Curve= 0
Exp/Cntr=.3,.1

Type RM Length L Ch R = 1 ,600.00  ,3,3,3
BEGIN DESCRIPTION:
12
END DESCRIPTION:
#Sta/Elev= 10
   -11.7   96.07    -1.7   96.07      -1   96.97     -.6   96.97     -.2   96.57
       0   96.57      .4   95.27     2.5   95.27     2.5   96.27    12.5   96.27
#Mann= 3 , 0 , 0
   -11.7    .035       0       0    .035       0     2.5    .035       0
#XS Ineff= 2 , 0
               0     110     2.5             110
Permanent Ineff=
       F       F
#Block Obstruct= 2 , 0
                             2.5
Bank Sta=0,2.5
XS Rating Curve= 0
Exp/Cntr=.3,.1

Type RM Length L Ch R = 1 ,597.00  ,10,10,10
BEGIN DESCRIPTION:
11.047
END DESCRIPTION:
#Sta/Elev= 10
   -11.7   95.72    -1.7   95.72      -1   96.62     -.6   96.62     -.2   96.22
       0   96.22      .4   95.22     2.5   95.22     2.5   96.22    12.5   96.22
#Mann= 3 , 0 , 0
   -11.7    .035       0       0    .035       0     2.5    .035       0
#XS Ineff= 2 , 0
               0     110     2.5             110
Permanent Ineff=
       F       F
#Block Obstruct= 2 , 0
                             2.5
Bank Sta=0,2.5
XS Rating Curve= 0
Exp/Cntr=.3,.1

Type RM Length L Ch R = 1 ,587.00  ,37,37,37
BEGIN DESCRIPTION:
11.037
END DESCRIPTION:
#Sta/Elev= 10
     -14   96.11      -4   96.11    -3.4   96.51       0   96.51       0   95.21
     1.9   95.21     1.9   96.51     2.9   96.51     7.9   95.91    17.9   95.91
#Mann= 3 , 0 , 0
     -14    .035       0       0    .035       0     2.9    .035       0
#XS Ineff= 2 , 0
               0     110     2.9             110
Permanent Ineff=
       F       F
#Block Obstruct= 2 , 0
                             2.9
Bank Sta=0,2.9
XS Rating Curve= 0
Exp/Cntr=.3,.1

Type RM Length L Ch R = 1 ,550.00  ,2,2,2
BEGIN DESCRIPTION:
11
END DESCRIPTION:
#Sta/Elev= 11
      -7   99.56      -4   98.06      -1   96.56       0   96.16     1.5   95.56
     2.6   94.66     4.8   94.66     5.2   96.16     5.8   96.16     7.4   94.76
    17.4   94.76
#Mann= 3 , 0 , 0
      -7    .035       0       0    .035       0     5.2    .035       0
#XS Ineff= 2 , 0
               0     110     5.2             110
Permanent Ineff=
       F       F
#Block Obstruct= 2 , 0
                             5.2
Bank Sta=0,5.2
XS Rating Curve= 0
Exp/Cntr=.3,.1

Type RM Length L Ch R = 1 ,548.00  ,48,48,48
BEGIN DESCRIPTION:
10.048
END DESCRIPTION:
#Sta/Elev= 11
      -7   99.51      -4   98.01      -1   96.51       0   96.11     1.5   95.51
     2.6   94.61     4.8   94.61     5.2   96.11     5.8   96.11     7.4   94.71
    17.4   94.71
#Mann= 3 , 0 , 0
      -7    .035       0       0    .035       0     5.2    .035       0
#XS Ineff= 2 , 0
               0     105     5.2             105
Permanent Ineff=
       F       F
#Block Obstruct= 2 , 0
                             5.2
Bank Sta=0,5.2
XS Rating Curve= 0
Exp/Cntr=.3,.1

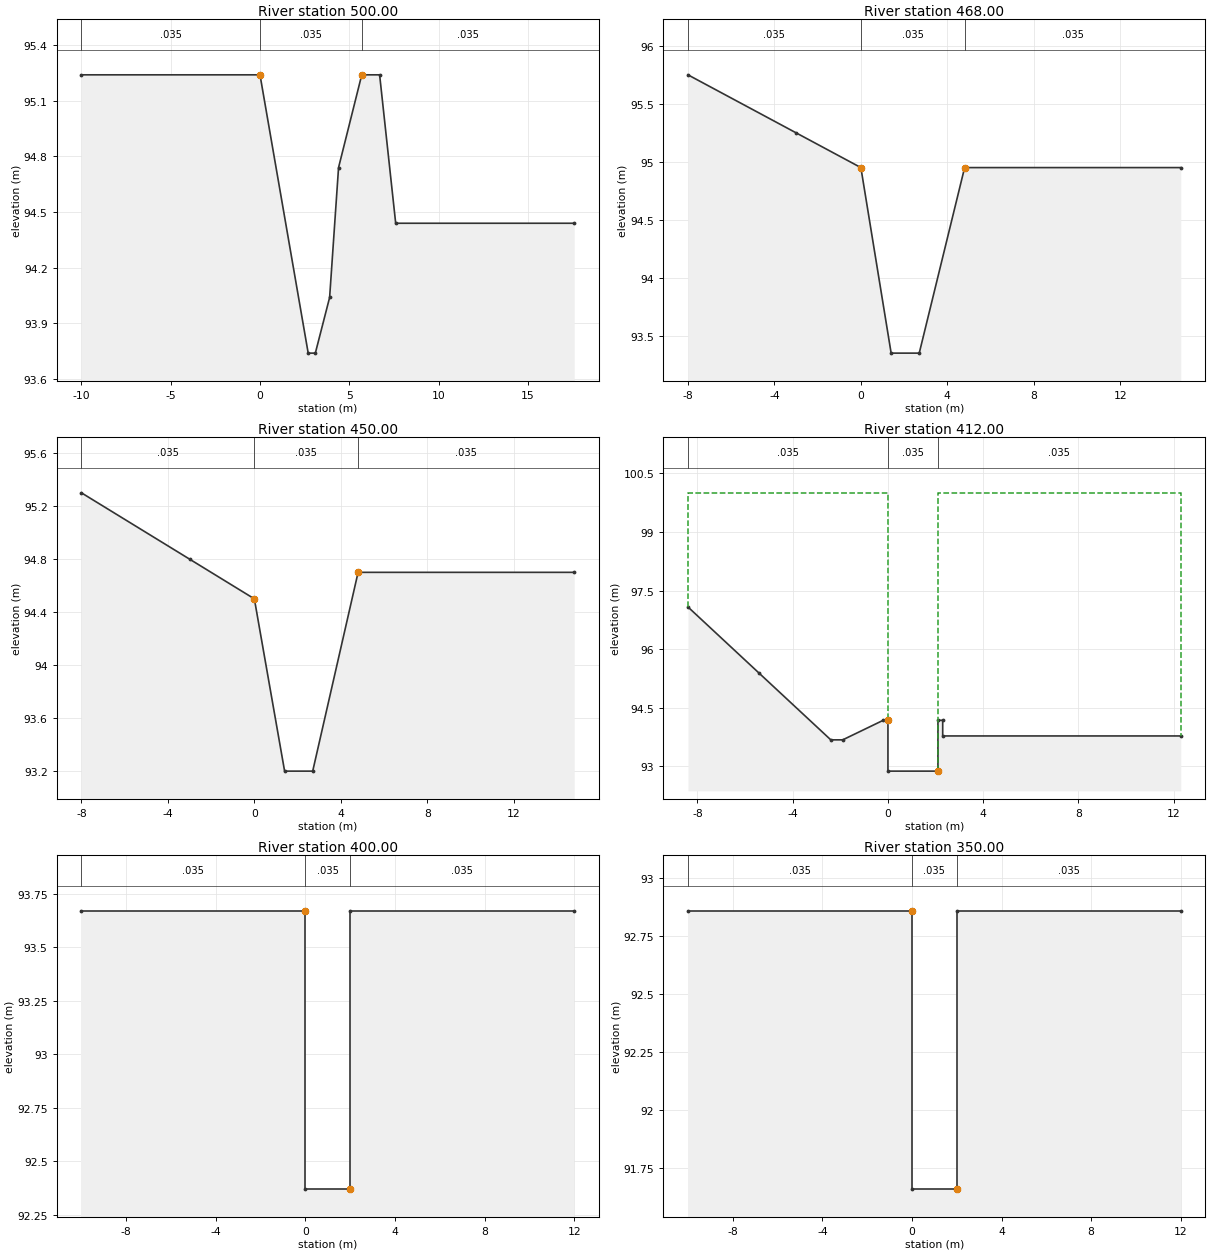
Type RM Length L Ch R = 1 ,500.00  ,32,32,32
BEGIN DESCRIPTION:
10
END DESCRIPTION:
#Sta/Elev= 10
     -10   95.24       0   95.24     2.7   93.74     3.1   93.74     3.9   94.04
     4.4   94.74     5.7   95.24     6.7   95.24     7.6   94.44    17.6   94.44
#Mann= 3 , 0 , 0
     -10    .035       0       0    .035       0     5.7    .035       0
#XS Ineff= 2 , 0
               0     105     5.7             105
Permanent Ineff=
       F       F
#Block Obstruct= 2 , 0
                             5.7
Bank Sta=0,5.7
XS Rating Curve= 0
Exp/Cntr=.3,.1

Type RM Length L Ch R = 1 ,468.00  ,18,18,18
BEGIN DESCRIPTION:
9.018
END DESCRIPTION:
#Sta/Elev= 7
      -8   95.75      -3   95.25       0   94.95     1.4   93.35     2.7   93.35
     4.8   94.95    14.8   94.95
#Mann= 3 , 0 , 0
      -8    .035       0       0    .035       0     4.8    .035       0
#XS Ineff= 2 , 0
               0     105     4.8             105
Permanent Ineff=
       F       F
#Block Obstruct= 2 , 0
                             4.8
Bank Sta=0,4.8
XS Rating Curve= 0
Exp/Cntr=.3,.1

Type RM Length L Ch R = 1 ,450.00  ,38,38,38
BEGIN DESCRIPTION:
9
END DESCRIPTION:
#Sta/Elev= 7
      -8    95.3      -3    94.8       0    94.5     1.4    93.2     2.7    93.2
     4.8    94.7    14.8    94.7
#Mann= 3 , 0 , 0
      -8    .035       0       0    .035       0     4.8    .035       0
#XS Ineff= 2 , 0
               0     105     4.8             105
Permanent Ineff=
       F       F
#Block Obstruct= 2 , 0
                             4.8
Bank Sta=0,4.8
XS Rating Curve= 0
Exp/Cntr=.3,.1

Type RM Length L Ch R = 1 ,412.00  ,12,12,12
BEGIN DESCRIPTION:
8.012
END DESCRIPTION:
#Sta/Elev= 12
    -8.4   97.08    -5.4   95.38    -2.4   93.68    -1.9   93.68     -.2   94.18
       0   94.18       0   92.88     2.1   92.88     2.1   94.18     2.3   94.18
     2.3   93.78    12.3   93.78
#Mann= 3 , 0 , 0
    -8.4    .035       0       0    .035       0     2.1    .035       0
#XS Ineff= 2 , 0
               0     100     2.1             100
Permanent Ineff=
       F       F
#Block Obstruct= 2 , 0
                             2.1
Bank Sta=0,2.1
XS Rating Curve= 0
Exp/Cntr=.3,.1

Type RM Length L Ch R = 1 ,400.00  ,50,50,50
BEGIN DESCRIPTION:
8
END DESCRIPTION:
#Sta/Elev= 6
     -10   93.67       0   93.67       0   92.37       2   92.37       2   93.67
      12   93.67
#Mann= 3 , 0 , 0
     -10    .035       0       0    .035       0       2    .035       0
#XS Ineff= 2 , 0
               0     100       2             100
Permanent Ineff=
       F       F
#Block Obstruct= 2 , 0
                               2
Bank Sta=0,2
XS Rating Curve= 0
Exp/Cntr=.3,.1

Type RM Length L Ch R = 1 ,350.00  ,50,50,50
BEGIN DESCRIPTION:
7
END DESCRIPTION:
#Sta/Elev= 6
     -10   92.86       0   92.86       0   91.66       2   91.66       2   92.86
      12   92.86
#Mann= 3 , 0 , 0
     -10    .035       0       0    .035       0       2    .035       0
#XS Ineff= 2 , 0
               0     100       2             100
Permanent Ineff=
       F       F
#Block Obstruct= 2 , 0
                               2
Bank Sta=0,2
XS Rating Curve= 0
Exp/Cntr=.3,.1