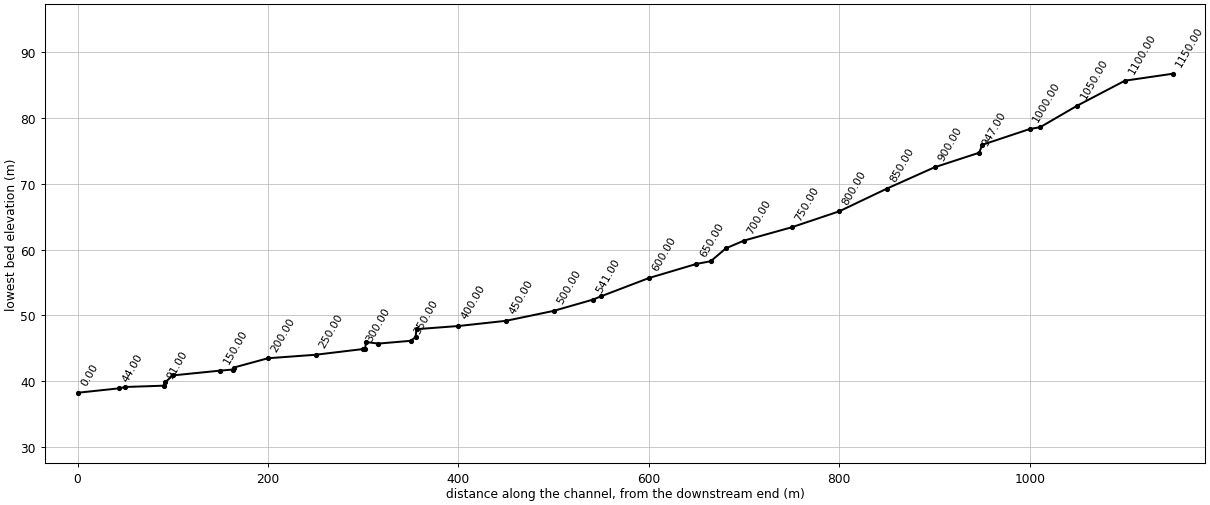
--- BHC.prj (project) ---

Proj Title=BUNHANG
Current Plan=p01
Default Exp/Contr=.3,.1
SI Units
Geom File=g01
Flow File=f01
Plan File=p01
Y Axis Title=Elevation
X Axis Title(PF)=Main Channel Distance
X Axis Title(XS)=Station
BEGIN DESCRIPTION:
           BACK WATER COMPUTATION
      APPLICATION OF HEC-2 BY Samju Construction Engineering
      bunhyang-ch: 10,20,30,50,80 yr
END DESCRIPTION:
DSS Export Rating Curves= 0
DSS Export Rating Curve Sorted= 0
DSS Export Volume Flow Curves= 0
DXF OffsetX= 0
DXF OffsetY= 0
DXF ScaleX= 1
DXF ScaleY= 10

--- BHC.p01 (plan) ---

Plan Title=Imported Plan 01
Version=Version 3.0.1  Mar 2001
Short Identifier=Imported Pla
Geom File=g01
Flow File=f01
Subcritical Flow
K Sum by GR= 0
Std Step Tol= 0.003
Critical Tol= 0.003
Num of Std Step Trials= 20
Max Error Tol= 0.1
Flow Tol Ratio= 0.001
Split Flow NTrial= 30
Split Flow Tol= 0.02
Split Flow Ratio= 0.02
Log Output Level= 0
Friction Slope Method= 1
Unsteady Friction Slope Method= 2
Parabolic Critical Depth
Global Vel Dist= 0 , 0 , 0
Global Log Level= 0
CheckData=True
Encroach Param=-1 ,0,0, 0
Computation Interval=1HOUR
Output Interval=1HOUR
Run HTab= 0
Run UNet= 0
Run PostProcess= 0
UNET Theta= 1
UNET ZTol= 0.02
UNET ZSATol= 0.1
UNET MxIter= 20
UNET MaxInSteps= 20
UNET DtIC= 0
UNET DtMin= 0
UNET MaxCRTS= 20
UNET WFStab= 2
UNET SFStab= 1
UNET WFX= 1
UNET SFX= 1
UNET Convert EG Bridges=-1
UNET Use Existing IB Tables=-1
Instantaneous Interval=1HOUR
Write IC File= 0
Write Velocity= 0
Write Detailed= 0

--- BHC.f01 (steady flow) ---

Flow Title=Imported Flow 01
Version=Version 3.0.1  Mar 2001
Number of Profiles= 5
Profile Names=10YR,20YR,30YR,50YR,80YR
River Rch & RM=RIVER-1,Reach-1         ,1150.00
    16.6   18.29   19.28   20.53   21.68
Boundary for River Rch & Prof#=RIVER-1,Reach-1         , 1
Up Type= 0
Dn Type= 3
Dn Slope=.052
Boundary for River Rch & Prof#=RIVER-1,Reach-1         , 2
Up Type= 0
Dn Type= 3
Dn Slope=.052
Boundary for River Rch & Prof#=RIVER-1,Reach-1         , 3
Up Type= 0
Dn Type= 3
Dn Slope=.052
Boundary for River Rch & Prof#=RIVER-1,Reach-1         , 4
Up Type= 0
Dn Type= 3
Dn Slope=.052
Boundary for River Rch & Prof#=RIVER-1,Reach-1         , 5
Up Type= 0
Dn Type= 3
Dn Slope=.052
DSS Import GetInterval= 0
DSS Import GetPeak= 0
DSS Import FillOption= 0

--- BHC.g01 (geometry) ---

Geom Title=Imported Geom 01
Version=Version 3.0.1  Mar 2001

River Reach=RIVER-1         ,Reach-1
Reach XY= 2
              .5             .95              .5             .05

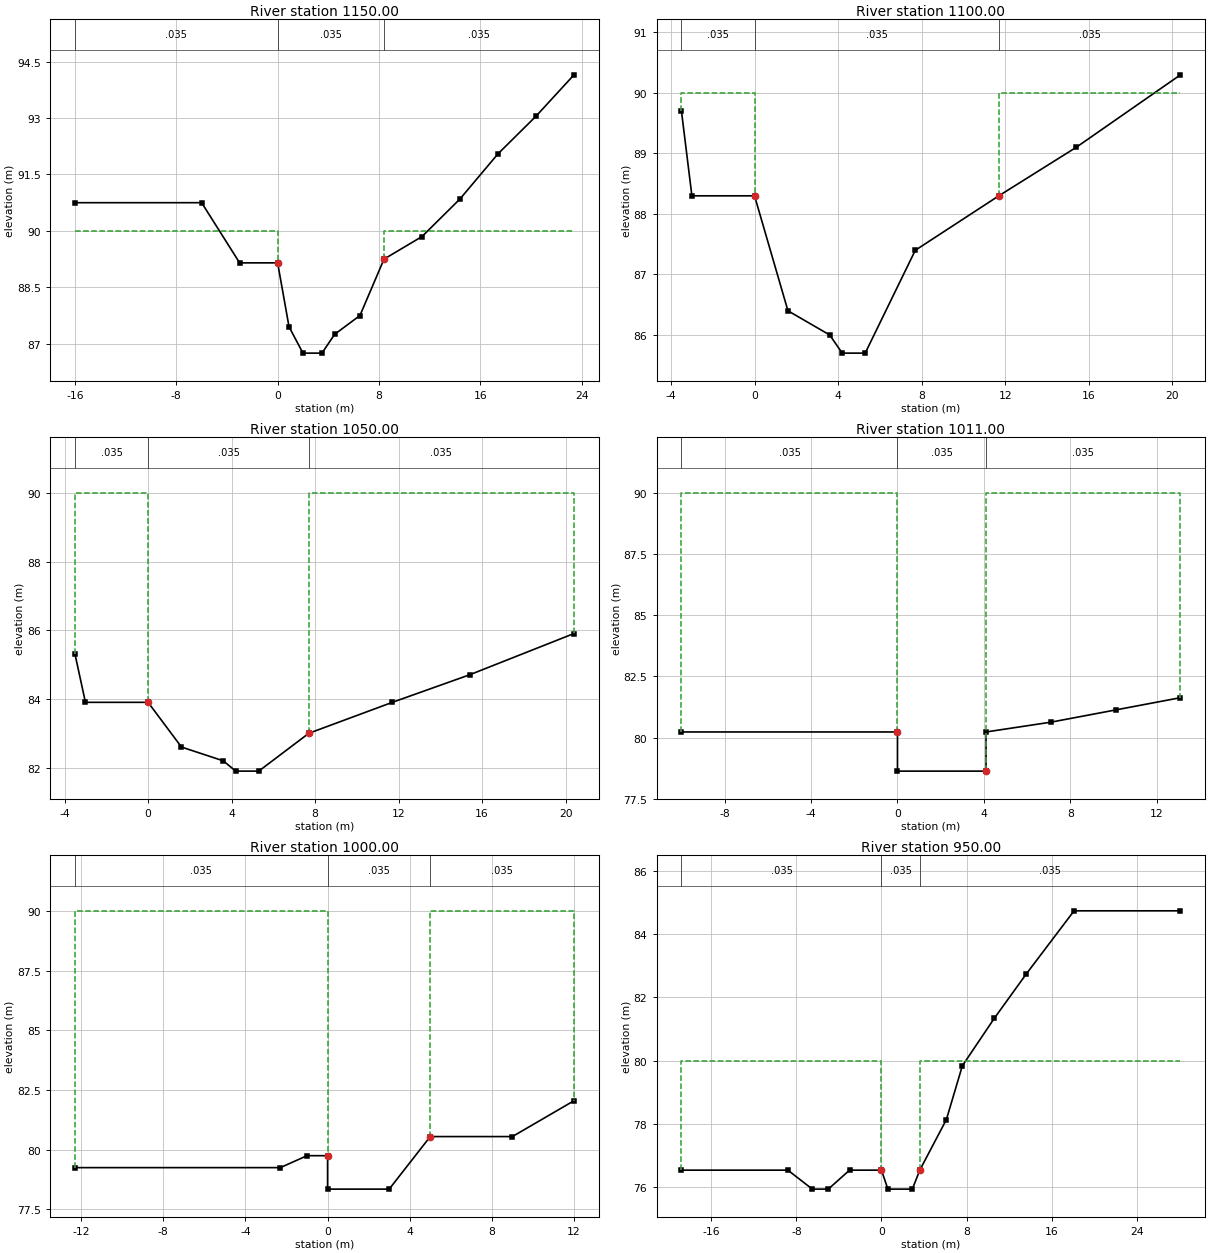
Type RM Length L Ch R = 1 ,1150.00 ,50,50,50
BEGIN DESCRIPTION:
24
END DESCRIPTION:
#Sta/Elev= 15
     -16   90.75      -6   90.75      -3   89.15       0   89.15      .9   87.45
       2   86.75     3.5   86.75     4.5   87.25     6.5   87.75     8.4   89.25
    11.4   89.85    14.4   90.85    17.4   92.05    20.4   93.05    23.4   94.15
#Mann= 3 , 0 , 0
     -16    .035       0       0    .035       0     8.4    .035       0
#XS Ineff= 2 , 0
               0      90     8.4              90
Permanent Ineff=
       F       F
#Block Obstruct= 2 , 0
                             8.4
Bank Sta=0,8.4
XS Rating Curve= 0
Exp/Cntr=.3,.1

Type RM Length L Ch R = 1 ,1100.00 ,50,50,50
BEGIN DESCRIPTION:
22
END DESCRIPTION:
#Sta/Elev= 11
    -3.5    89.7      -3    88.3       0    88.3     1.6    86.4     3.6      86
     4.2    85.7     5.3    85.7     7.7    87.4    11.7    88.3    15.4    89.1
    20.4    90.3
#Mann= 3 , 0 , 0
    -3.5    .035       0       0    .035       0    11.7    .035       0
#XS Ineff= 2 , 0
               0      90    11.7              90
Permanent Ineff=
       F       F
#Block Obstruct= 2 , 0
                            11.7
Bank Sta=0,11.7
XS Rating Curve= 0
Exp/Cntr=.3,.1

Type RM Length L Ch R = 1 ,1050.00 ,39,39,39
BEGIN DESCRIPTION:
21
END DESCRIPTION:
#Sta/Elev= 11
    -3.5   85.31      -3   83.91       0   83.91     1.6   82.61     3.6   82.21
     4.2   81.91     5.3   81.91     7.7   83.01    11.7   83.91    15.4   84.71
    20.4   85.91
#Mann= 3 , 0 , 0
    -3.5    .035       0       0    .035       0     7.7    .035       0
#XS Ineff= 2 , 0
               0      90     7.7              90
Permanent Ineff=
       F       F
#Block Obstruct= 2 , 0
                             7.7
Bank Sta=0,7.7
XS Rating Curve= 0
Exp/Cntr=.3,.1

Type RM Length L Ch R = 1 ,1011.00 ,11,11,11
BEGIN DESCRIPTION:
20.011
END DESCRIPTION:
#Sta/Elev= 8
     -10   80.23       0   80.23       0   78.63     4.1   78.63     4.1   80.23
     7.1   80.63    10.1   81.13    13.1   81.63
#Mann= 3 , 0 , 0
     -10    .035       0       0    .035       0     4.1    .035       0
#XS Ineff= 2 , 0
               0      90     4.1              90
Permanent Ineff=
       F       F
#Block Obstruct= 2 , 0
                             4.1
Bank Sta=0,4.1
XS Rating Curve= 0
Exp/Cntr=.3,.1

Type RM Length L Ch R = 1 ,1000.00 ,50,50,50
BEGIN DESCRIPTION:
20
END DESCRIPTION:
#Sta/Elev= 9
   -12.3   79.25    -2.3   79.25      -1   79.75       0   79.75       0   78.35
       3   78.35       5   80.55       9   80.55      12   82.05
#Mann= 3 , 0 , 0
   -12.3    .035       0       0    .035       0       5    .035       0
#XS Ineff= 2 , 0
               0      90       5              90
Permanent Ineff=
       F       F
#Block Obstruct= 2 , 0
                               5
Bank Sta=0,5
XS Rating Curve= 0
Exp/Cntr=.3,.1

Type RM Length L Ch R = 1 ,950.00  ,3,3,3
BEGIN DESCRIPTION:
19
END DESCRIPTION:
#Sta/Elev= 15
   -18.8   76.54    -8.8   76.54    -6.5   75.94      -5   75.94      -3   76.54
       0   76.54      .6   75.94     2.9   75.94     3.6   76.54     6.1   78.14
     7.6   79.84    10.6   81.34    13.6   82.74    18.1   84.74    28.1   84.74
#Mann= 3 , 0 , 0
   -18.8    .035       0       0    .035       0     3.6    .035       0
#XS Ineff= 2 , 0
               0      80     3.6              80
Permanent Ineff=
       F       F
#Block Obstruct= 2 , 0
                             3.6
Bank Sta=0,3.6
XS Rating Curve= 0
Exp/Cntr=.3,.1

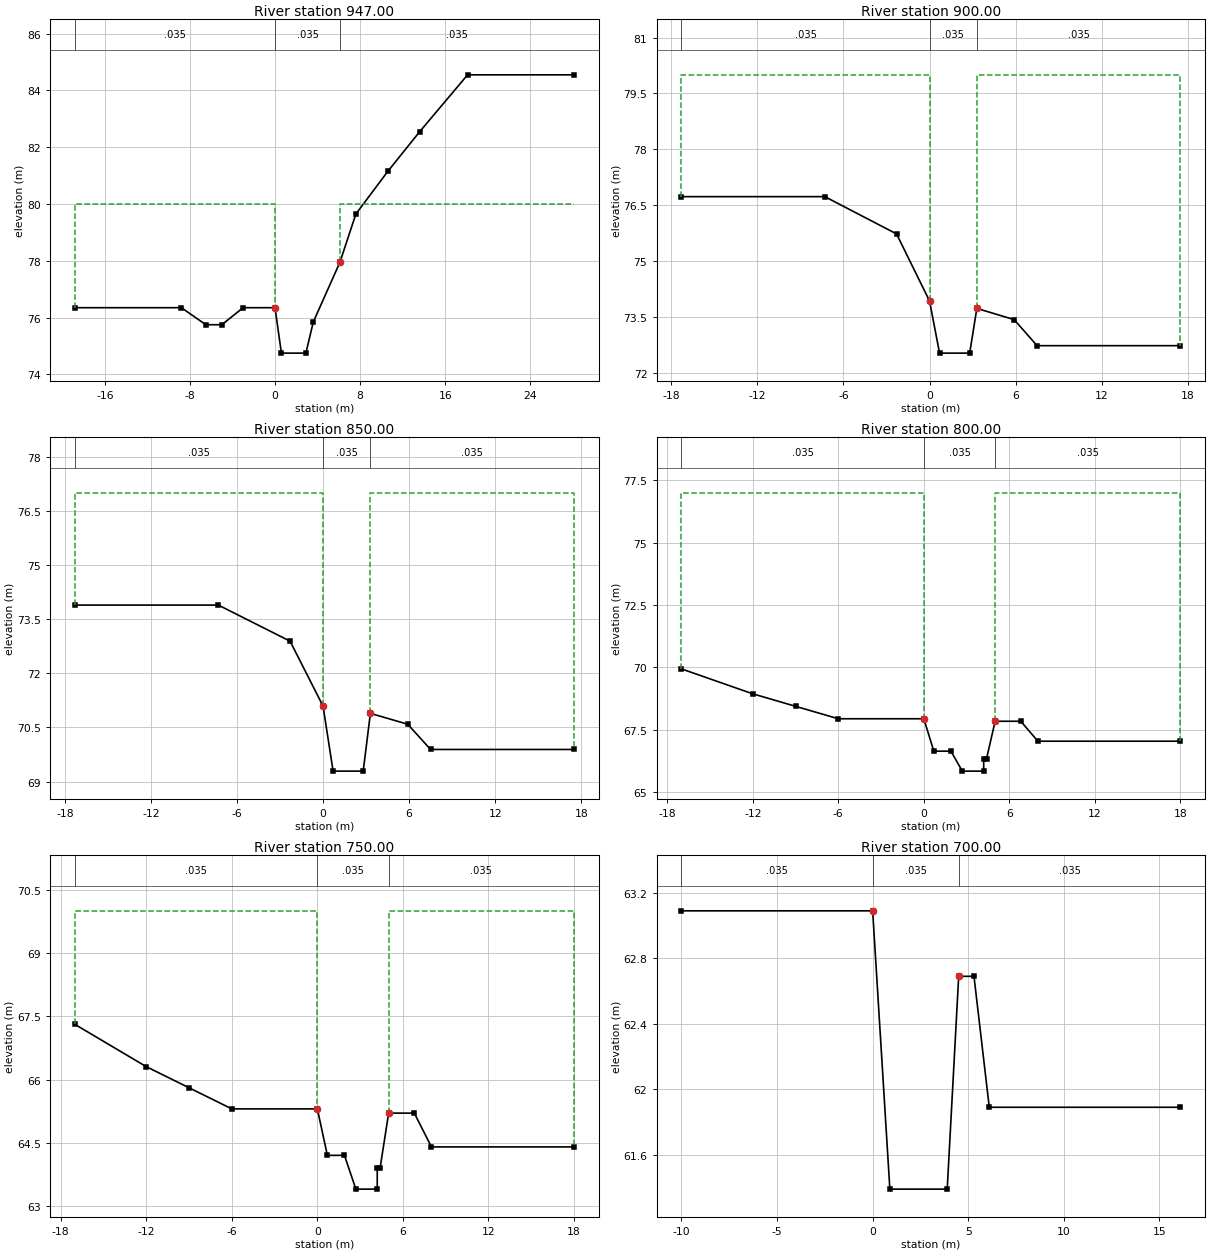
Type RM Length L Ch R = 1 ,947.00  ,47,47,47
BEGIN DESCRIPTION:
18.047
END DESCRIPTION:
#Sta/Elev= 15
   -18.8   76.35    -8.8   76.35    -6.5   75.75      -5   75.75      -3   76.35
       0   76.35      .6   74.75     2.9   74.75     3.6   75.85     6.1   77.95
     7.6   79.65    10.6   81.15    13.6   82.55    18.1   84.55    28.1   84.55
#Mann= 3 , 0 , 0
   -18.8    .035       0       0    .035       0     6.1    .035       0
#XS Ineff= 2 , 0
               0      80     6.1              80
Permanent Ineff=
       F       F
#Block Obstruct= 2 , 0
                             6.1
Bank Sta=0,6.1
XS Rating Curve= 0
Exp/Cntr=.3,.1

Type RM Length L Ch R = 1 ,900.00  ,50,50,50
BEGIN DESCRIPTION:
18
END DESCRIPTION:
#Sta/Elev= 10
   -17.3   76.73    -7.3   76.73    -2.3   75.73       0   73.93      .7   72.53
     2.8   72.53     3.3   73.73     5.9   73.43     7.5   72.73    17.5   72.73
#Mann= 3 , 0 , 0
   -17.3    .035       0       0    .035       0     3.3    .035       0
#XS Ineff= 2 , 0
               0      80     3.3              80
Permanent Ineff=
       F       F
#Block Obstruct= 2 , 0
                             3.3
Bank Sta=0,3.3
XS Rating Curve= 0
Exp/Cntr=.3,.1

Type RM Length L Ch R = 1 ,850.00  ,50,50,50
BEGIN DESCRIPTION:
17
END DESCRIPTION:
#Sta/Elev= 10
   -17.3   73.89    -7.3   73.89    -2.3   72.89       0   71.09      .7   69.29
     2.8   69.29     3.3   70.89     5.9   70.59     7.5   69.89    17.5   69.89
#Mann= 3 , 0 , 0
   -17.3    .035       0       0    .035       0     3.3    .035       0
#XS Ineff= 2 , 0
               0      77     3.3              77
Permanent Ineff=
       F       F
#Block Obstruct= 2 , 0
                             3.3
Bank Sta=0,3.3
XS Rating Curve= 0
Exp/Cntr=.3,.1

Type RM Length L Ch R = 1 ,800.00  ,50,50,50
BEGIN DESCRIPTION:
16
END DESCRIPTION:
#Sta/Elev= 15
     -17   69.94     -12   68.94      -9   68.44      -6   67.94       0   67.94
      .7   66.64     1.9   66.64     2.7   65.84     4.2   65.84     4.2   66.34
     4.4   66.34       5   67.84     6.8   67.84       8   67.04      18   67.04
#Mann= 3 , 0 , 0
     -17    .035       0       0    .035       0       5    .035       0
#XS Ineff= 2 , 0
               0      77       5              77
Permanent Ineff=
       F       F
#Block Obstruct= 2 , 0
                               5
Bank Sta=0,5
XS Rating Curve= 0
Exp/Cntr=.3,.1

Type RM Length L Ch R = 1 ,750.00  ,50,50,50
BEGIN DESCRIPTION:
15
END DESCRIPTION:
#Sta/Elev= 15
     -17   67.31     -12   66.31      -9   65.81      -6   65.31       0   65.31
      .7   64.21     1.9   64.21     2.7   63.41     4.2   63.41     4.2   63.91
     4.4   63.91       5   65.21     6.8   65.21       8   64.41      18   64.41
#Mann= 3 , 0 , 0
     -17    .035       0       0    .035       0       5    .035       0
#XS Ineff= 2 , 0
               0      70       5              70
Permanent Ineff=
       F       F
#Block Obstruct= 2 , 0
                               5
Bank Sta=0,5
XS Rating Curve= 0
Exp/Cntr=.3,.1

Type RM Length L Ch R = 1 ,700.00  ,19,19,19
BEGIN DESCRIPTION:
14
END DESCRIPTION:
#Sta/Elev= 8
     -10   63.09       0   63.09      .9   61.39     3.9   61.39     4.5   62.69
     5.3   62.69     6.1   61.89    16.1   61.89
#Mann= 3 , 0 , 0
     -10    .035       0       0    .035       0     4.5    .035       0
#XS Ineff= 2 , 0
               0      70     4.5              70
Permanent Ineff=
       F       F
#Block Obstruct= 2 , 0
                             4.5
Bank Sta=0,4.5
XS Rating Curve= 0
Exp/Cntr=.3,.1

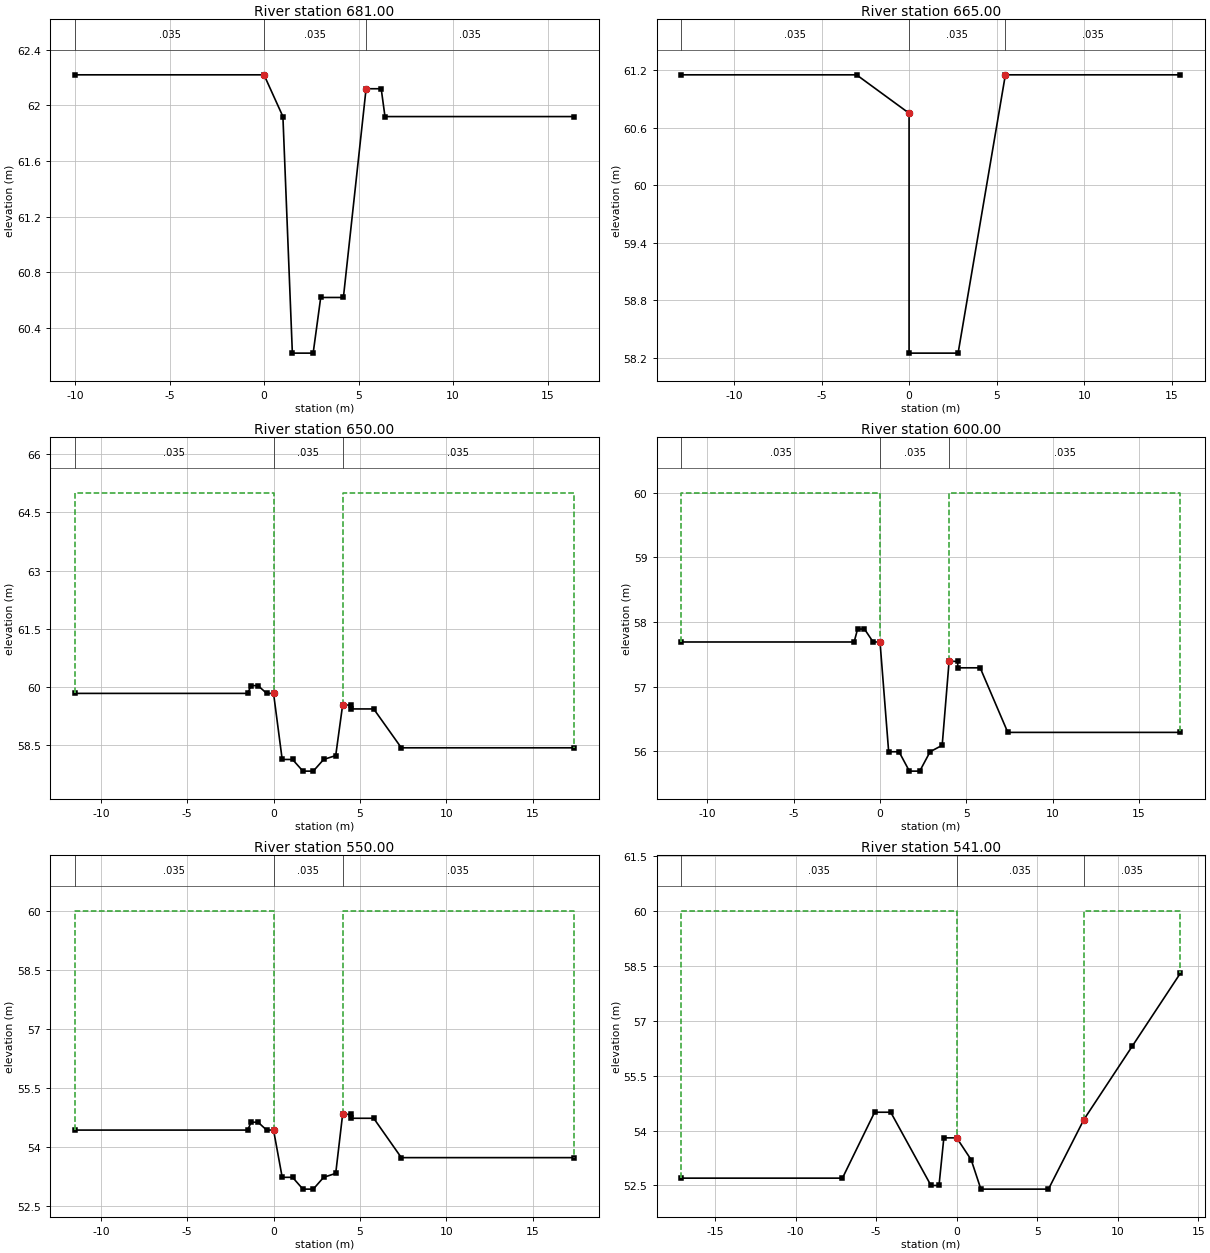
Type RM Length L Ch R = 1 ,681.00  ,16,16,16
BEGIN DESCRIPTION:
13.031
END DESCRIPTION:
#Sta/Elev= 11
     -10   62.22       0   62.22       1   61.92     1.5   60.22     2.6   60.22
       3   60.62     4.2   60.62     5.4   62.12     6.2   62.12     6.4   61.92
    16.4   61.92
#Mann= 3 , 0 , 0
     -10    .035       0       0    .035       0     5.4    .035       0
#XS Ineff= 2 , 0
               0      70     5.4              70
Permanent Ineff=
       F       F
#Block Obstruct= 2 , 0
                             5.4
Bank Sta=0,5.4
XS Rating Curve= 0
Exp/Cntr=.3,.1

Type RM Length L Ch R = 1 ,665.00  ,15,15,15
BEGIN DESCRIPTION:
13.015
END DESCRIPTION:
#Sta/Elev= 7
     -13   61.15      -3   61.15       0   60.75       0   58.25     2.8   58.25
     5.5   61.15    15.5   61.15
#Mann= 3 , 0 , 0
     -13    .035       0       0    .035       0     5.5    .035       0
#XS Ineff= 2 , 0
               0      70     5.5              70
Permanent Ineff=
       F       F
#Block Obstruct= 2 , 0
                             5.5
Bank Sta=0,5.5
XS Rating Curve= 0
Exp/Cntr=.3,.1

Type RM Length L Ch R = 1 ,650.00  ,50,50,50
BEGIN DESCRIPTION:
13
END DESCRIPTION:
#Sta/Elev= 18
   -11.5   59.84    -1.5   59.84    -1.3   60.04     -.9   60.04     -.4   59.84
       0   59.84      .5   58.14     1.1   58.14     1.7   57.84     2.3   57.84
     2.9   58.14     3.6   58.24       4   59.54     4.5   59.54     4.5   59.44
     5.8   59.44     7.4   58.44    17.4   58.44
#Mann= 3 , 0 , 0
   -11.5    .035       0       0    .035       0       4    .035       0
#XS Ineff= 2 , 0
               0      65       4              65
Permanent Ineff=
       F       F
#Block Obstruct= 2 , 0
                               4
Bank Sta=0,4
XS Rating Curve= 0
Exp/Cntr=.3,.1

Type RM Length L Ch R = 1 ,600.00  ,50,50,50
BEGIN DESCRIPTION:
12
END DESCRIPTION:
#Sta/Elev= 18
   -11.5   57.69    -1.5   57.69    -1.3   57.89     -.9   57.89     -.4   57.69
       0   57.69      .5   55.99     1.1   55.99     1.7   55.69     2.3   55.69
     2.9   55.99     3.6   56.09       4   57.39     4.5   57.39     4.5   57.29
     5.8   57.29     7.4   56.29    17.4   56.29
#Mann= 3 , 0 , 0
   -11.5    .035       0       0    .035       0       4    .035       0
#XS Ineff= 2 , 0
               0      60       4              60
Permanent Ineff=
       F       F
#Block Obstruct= 2 , 0
                               4
Bank Sta=0,4
XS Rating Curve= 0
Exp/Cntr=.3,.1

Type RM Length L Ch R = 1 ,550.00  ,9,9,9
BEGIN DESCRIPTION:
11
END DESCRIPTION:
#Sta/Elev= 18
   -11.5   54.43    -1.5   54.43    -1.3   54.63     -.9   54.63     -.4   54.43
       0   54.43      .5   53.23     1.1   53.23     1.7   52.93     2.3   52.93
     2.9   53.23     3.6   53.33       4   54.83     4.5   54.83     4.5   54.73
     5.8   54.73     7.4   53.73    17.4   53.73
#Mann= 3 , 0 , 0
   -11.5    .035       0       0    .035       0       4    .035       0
#XS Ineff= 2 , 0
               0      60       4              60
Permanent Ineff=
       F       F
#Block Obstruct= 2 , 0
                               4
Bank Sta=0,4
XS Rating Curve= 0
Exp/Cntr=.3,.1

Type RM Length L Ch R = 1 ,541.00  ,41,41,41
BEGIN DESCRIPTION:
10.041
END DESCRIPTION:
#Sta/Elev= 14
   -17.1    52.7    -7.1    52.7    -5.1    54.5    -4.1    54.5    -1.6    52.5
    -1.1    52.5     -.8    53.8       0    53.8      .9    53.2     1.5    52.4
     5.7    52.4     7.9    54.3    10.9    56.3    13.9    58.3
#Mann= 3 , 0 , 0
   -17.1    .035       0       0    .035       0     7.9    .035       0
#XS Ineff= 2 , 0
               0      60     7.9              60
Permanent Ineff=
       F       F
#Block Obstruct= 2 , 0
                             7.9
Bank Sta=0,7.9
XS Rating Curve= 0
Exp/Cntr=.3,.1

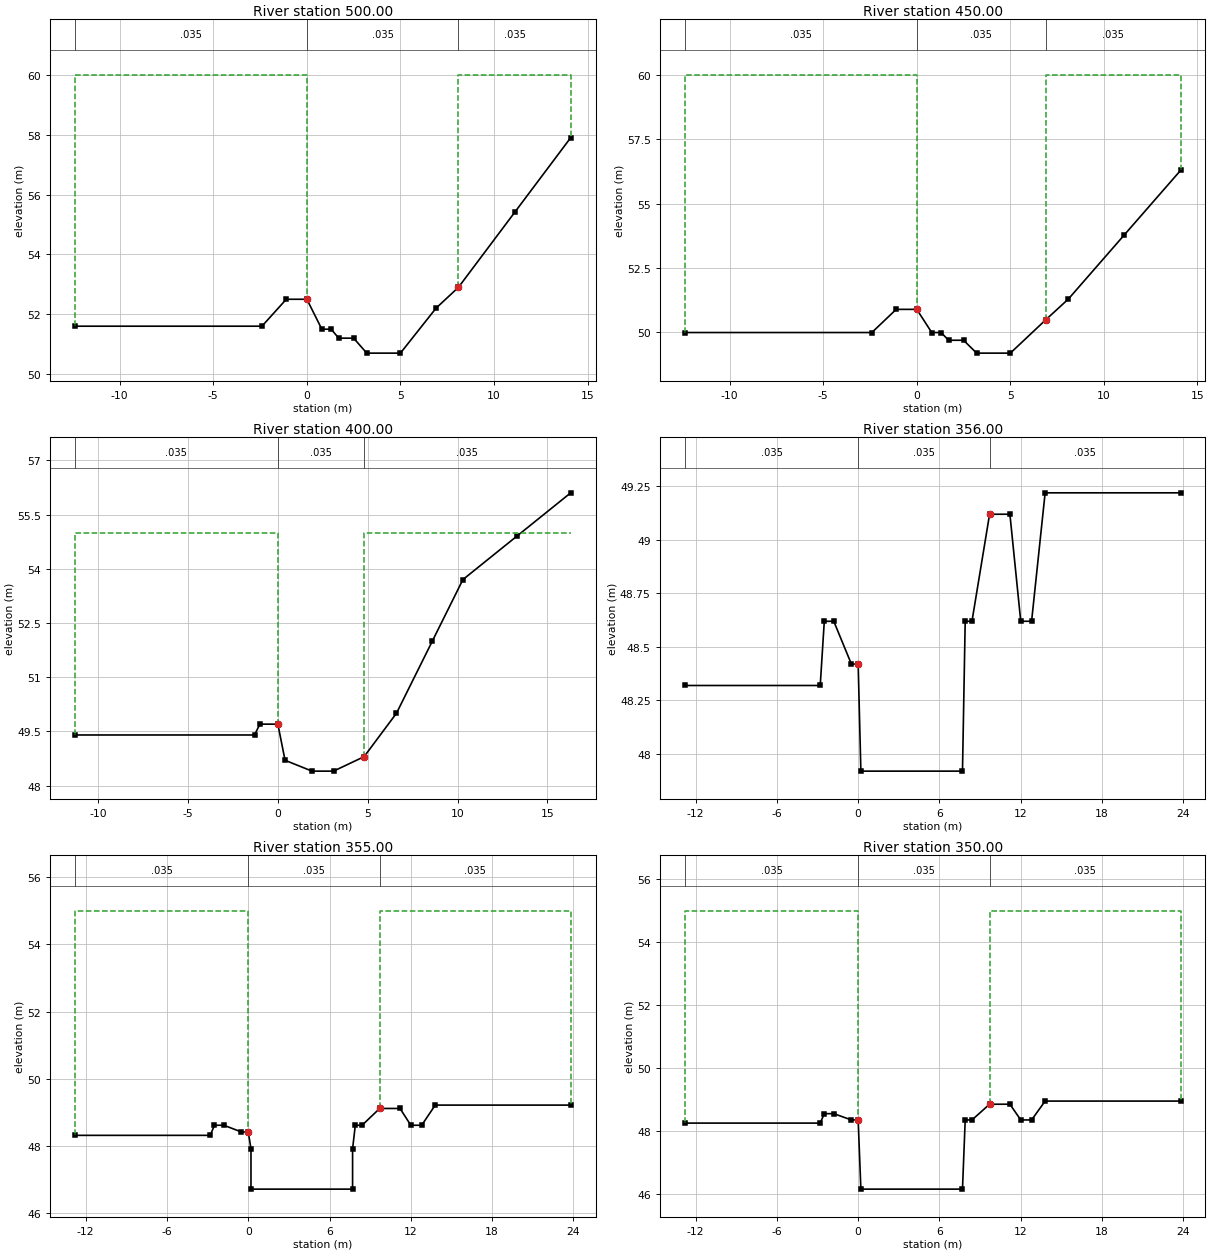
Type RM Length L Ch R = 1 ,500.00  ,50,50,50
BEGIN DESCRIPTION:
10
END DESCRIPTION:
#Sta/Elev= 14
   -12.4    51.6    -2.4    51.6    -1.1    52.5       0    52.5      .8    51.5
     1.3    51.5     1.7    51.2     2.5    51.2     3.2    50.7       5    50.7
     6.9    52.2     8.1    52.9    11.1    55.4    14.1    57.9
#Mann= 3 , 0 , 0
   -12.4    .035       0       0    .035       0     8.1    .035       0
#XS Ineff= 2 , 0
               0      60     8.1              60
Permanent Ineff=
       F       F
#Block Obstruct= 2 , 0
                             8.1
Bank Sta=0,8.1
XS Rating Curve= 0
Exp/Cntr=.3,.1

Type RM Length L Ch R = 1 ,450.00  ,50,50,50
BEGIN DESCRIPTION:
9
END DESCRIPTION:
#Sta/Elev= 14
   -12.4   49.99    -2.4   49.99    -1.1   50.89       0   50.89      .8   49.99
     1.3   49.99     1.7   49.69     2.5   49.69     3.2   49.19       5   49.19
     6.9   50.49     8.1   51.29    11.1   53.79    14.1   56.29
#Mann= 3 , 0 , 0
   -12.4    .035       0       0    .035       0     6.9    .035       0
#XS Ineff= 2 , 0
               0      60     6.9              60
Permanent Ineff=
       F       F
#Block Obstruct= 2 , 0
                             6.9
Bank Sta=0,6.9
XS Rating Curve= 0
Exp/Cntr=.3,.1

Type RM Length L Ch R = 1 ,400.00  ,44,44,44
BEGIN DESCRIPTION:
8
END DESCRIPTION:
#Sta/Elev= 13
   -11.3    49.4    -1.3    49.4      -1    49.7       0    49.7      .4    48.7
     1.9    48.4     3.1    48.4     4.8    48.8     6.6      50     8.6      52
    10.3    53.7    13.3    54.9    16.3    56.1
#Mann= 3 , 0 , 0
   -11.3    .035       0       0    .035       0     4.8    .035       0
#XS Ineff= 2 , 0
               0      55     4.8              55
Permanent Ineff=
       F       F
#Block Obstruct= 2 , 0
                             4.8
Bank Sta=0,4.8
XS Rating Curve= 0
Exp/Cntr=.3,.1

Type RM Length L Ch R = 1 ,356.00  ,1,1,1
BEGIN DESCRIPTION:
7.006
END DESCRIPTION:
#Sta/Elev= 16
   -12.8   48.32    -2.8   48.32    -2.5   48.62    -1.8   48.62     -.5   48.42
       0   48.42      .2   47.92     7.7   47.92     7.9   48.62     8.4   48.62
     9.7   49.12    11.2   49.12      12   48.62    12.8   48.62    13.8   49.22
    23.8   49.22
#Mann= 3 , 0 , 0
   -12.8    .035       0       0    .035       0     9.7    .035       0
#XS Ineff= 2 , 0
               0      55     9.7              55
Permanent Ineff=
       F       F
#Block Obstruct= 2 , 0
                             9.7
Bank Sta=0,9.7
XS Rating Curve= 0
Exp/Cntr=.3,.1

Type RM Length L Ch R = 1 ,355.00  ,5,5,5
BEGIN DESCRIPTION:
7.005
END DESCRIPTION:
#Sta/Elev= 18
   -12.8   48.32    -2.8   48.32    -2.5   48.62    -1.8   48.62     -.5   48.42
       0   48.42      .2   47.92      .2   46.72     7.7   46.72     7.7   47.92
     7.9   48.62     8.4   48.62     9.7   49.12    11.2   49.12      12   48.62
    12.8   48.62    13.8   49.22    23.8   49.22
#Mann= 3 , 0 , 0
   -12.8    .035       0       0    .035       0     9.7    .035       0
#XS Ineff= 2 , 0
               0      55     9.7              55
Permanent Ineff=
       F       F
#Block Obstruct= 2 , 0
                             9.7
Bank Sta=0,9.7
XS Rating Curve= 0
Exp/Cntr=.3,.1

Type RM Length L Ch R = 1 ,350.00  ,34,34,34
BEGIN DESCRIPTION:
7
END DESCRIPTION:
#Sta/Elev= 16
   -12.8   48.25    -2.8   48.25    -2.5   48.55    -1.8   48.55     -.5   48.35
       0   48.35      .2   46.15     7.7   46.15     7.9   48.35     8.4   48.35
     9.7   48.85    11.2   48.85      12   48.35    12.8   48.35    13.8   48.95
    23.8   48.95
#Mann= 3 , 0 , 0
   -12.8    .035       0       0    .035       0     9.7    .035       0
#XS Ineff= 2 , 0
               0      55     9.7              55
Permanent Ineff=
       F       F
#Block Obstruct= 2 , 0
                             9.7
Bank Sta=0,9.7
XS Rating Curve= 0
Exp/Cntr=.3,.1

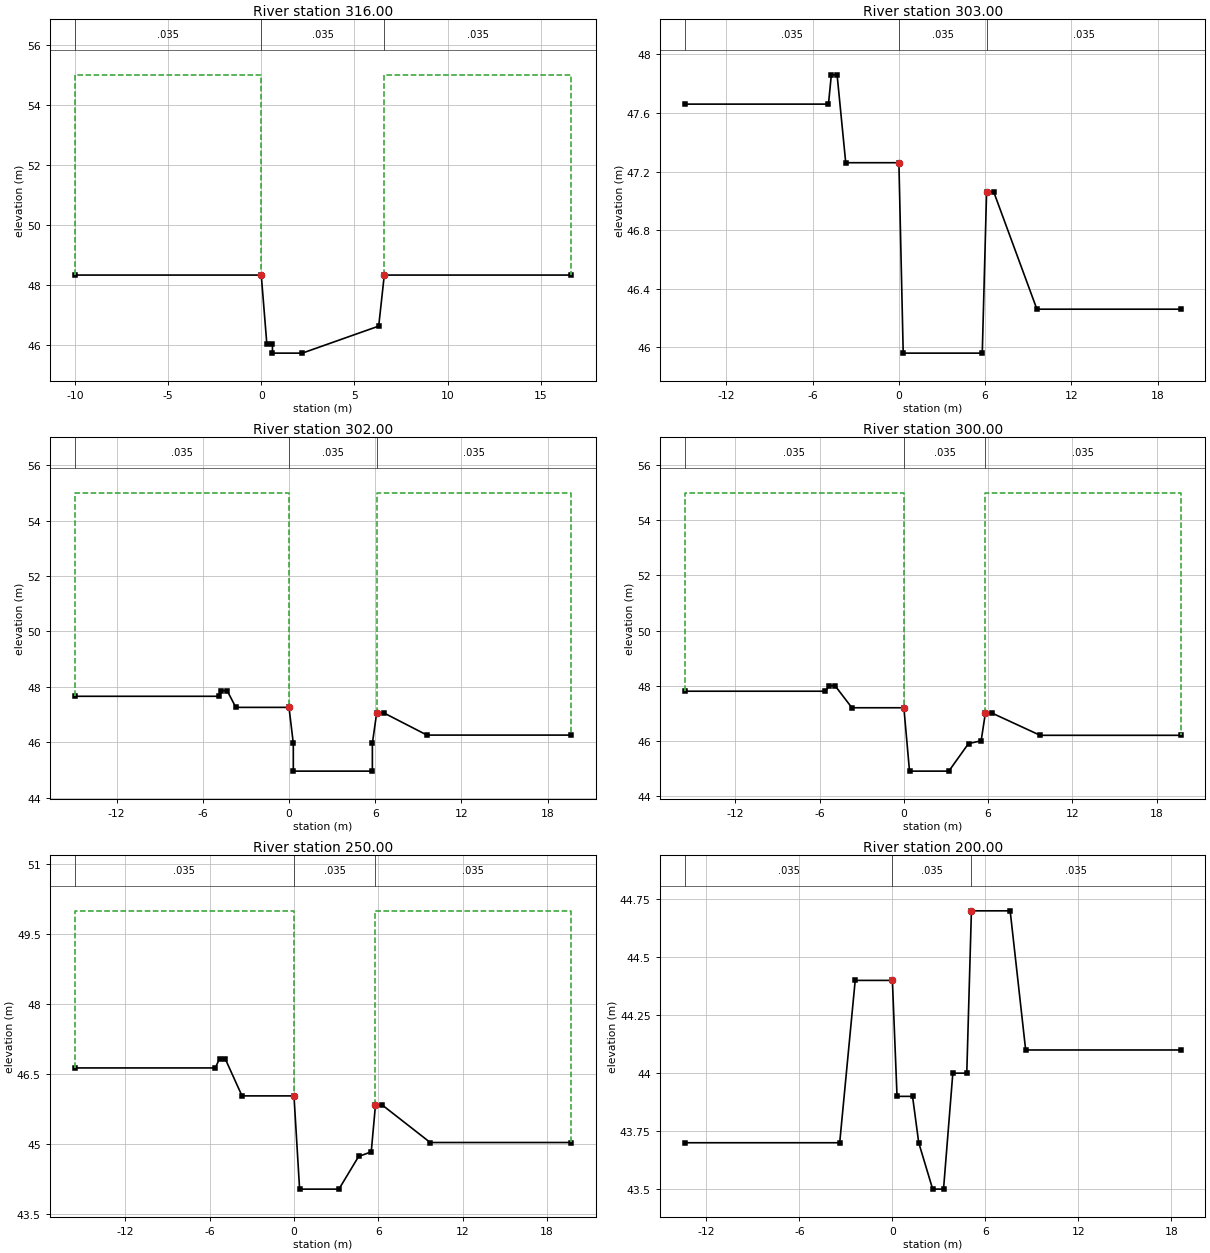
Type RM Length L Ch R = 1 ,316.00  ,13,13,13
BEGIN DESCRIPTION:
6.016
END DESCRIPTION:
#Sta/Elev= 9
     -10   48.33       0   48.33      .3   46.03      .6   46.03      .6   45.73
     2.2   45.73     6.3   46.63     6.6   48.33    16.6   48.33
#Mann= 3 , 0 , 0
     -10    .035       0       0    .035       0     6.6    .035       0
#XS Ineff= 2 , 0
               0      55     6.6              55
Permanent Ineff=
       F       F
#Block Obstruct= 2 , 0
                             6.6
Bank Sta=0,6.6
XS Rating Curve= 0
Exp/Cntr=.3,.1

Type RM Length L Ch R = 1 ,303.00  ,1,1,1
BEGIN DESCRIPTION:
6.003
END DESCRIPTION:
#Sta/Elev= 12
   -14.9   47.66    -4.9   47.66    -4.7   47.86    -4.3   47.86    -3.7   47.26
       0   47.26      .3   45.96     5.8   45.96     6.1   47.06     6.6   47.06
     9.6   46.26    19.6   46.26
#Mann= 3 , 0 , 0
   -14.9    .035       0       0    .035       0     6.1    .035       0
#XS Ineff= 2 , 0
               0      55     6.1              55
Permanent Ineff=
       F       F
#Block Obstruct= 2 , 0
                             6.1
Bank Sta=0,6.1
XS Rating Curve= 0
Exp/Cntr=.3,.1

Type RM Length L Ch R = 1 ,302.00  ,2,2,2
BEGIN DESCRIPTION:
6.002
END DESCRIPTION:
#Sta/Elev= 14
   -14.9   47.66    -4.9   47.66    -4.7   47.86    -4.3   47.86    -3.7   47.26
       0   47.26      .3   45.96      .3   44.96     5.8   44.96     5.8   45.96
     6.1   47.06     6.6   47.06     9.6   46.26    19.6   46.26
#Mann= 3 , 0 , 0
   -14.9    .035       0       0    .035       0     6.1    .035       0
#XS Ineff= 2 , 0
               0      55     6.1              55
Permanent Ineff=
       F       F
#Block Obstruct= 2 , 0
                             6.1
Bank Sta=0,6.1
XS Rating Curve= 0
Exp/Cntr=.3,.1

Type RM Length L Ch R = 1 ,300.00  ,50,50,50
BEGIN DESCRIPTION:
6
END DESCRIPTION:
#Sta/Elev= 14
   -15.6    47.8    -5.6    47.8    -5.3      48    -4.9      48    -3.7    47.2
       0    47.2      .4    44.9     3.2    44.9     4.6    45.9     5.5      46
     5.8      47     6.3      47     9.7    46.2    19.7    46.2
#Mann= 3 , 0 , 0
   -15.6    .035       0       0    .035       0     5.8    .035       0
#XS Ineff= 2 , 0
               0      55     5.8              55
Permanent Ineff=
       F       F
#Block Obstruct= 2 , 0
                             5.8
Bank Sta=0,5.8
XS Rating Curve= 0
Exp/Cntr=.3,.1

Type RM Length L Ch R = 1 ,250.00  ,50,50,50
BEGIN DESCRIPTION:
5
END DESCRIPTION:
#Sta/Elev= 14
   -15.6   46.63    -5.6   46.63    -5.3   46.83    -4.9   46.83    -3.7   46.03
       0   46.03      .4   44.03     3.2   44.03     4.6   44.73     5.5   44.83
     5.8   45.83     6.3   45.83     9.7   45.03    19.7   45.03
#Mann= 3 , 0 , 0
   -15.6    .035       0       0    .035       0     5.8    .035       0
#XS Ineff= 2 , 0
               0      50     5.8              50
Permanent Ineff=
       F       F
#Block Obstruct= 2 , 0
                             5.8
Bank Sta=0,5.8
XS Rating Curve= 0
Exp/Cntr=.3,.1

Type RM Length L Ch R = 1 ,200.00  ,36,36,36
BEGIN DESCRIPTION:
4
END DESCRIPTION:
#Sta/Elev= 15
   -13.4    43.7    -3.4    43.7    -2.4    44.4       0    44.4      .3    43.9
     1.3    43.9     1.7    43.7     2.6    43.5     3.3    43.5     3.9      44
     4.8      44     5.1    44.7     7.6    44.7     8.6    44.1    18.6    44.1
#Mann= 3 , 0 , 0
   -13.4    .035       0       0    .035       0     5.1    .035       0
#XS Ineff= 2 , 0
               0      50     5.1              50
Permanent Ineff=
       F       F
#Block Obstruct= 2 , 0
                             5.1
Bank Sta=0,5.1
XS Rating Curve= 0
Exp/Cntr=.3,.1

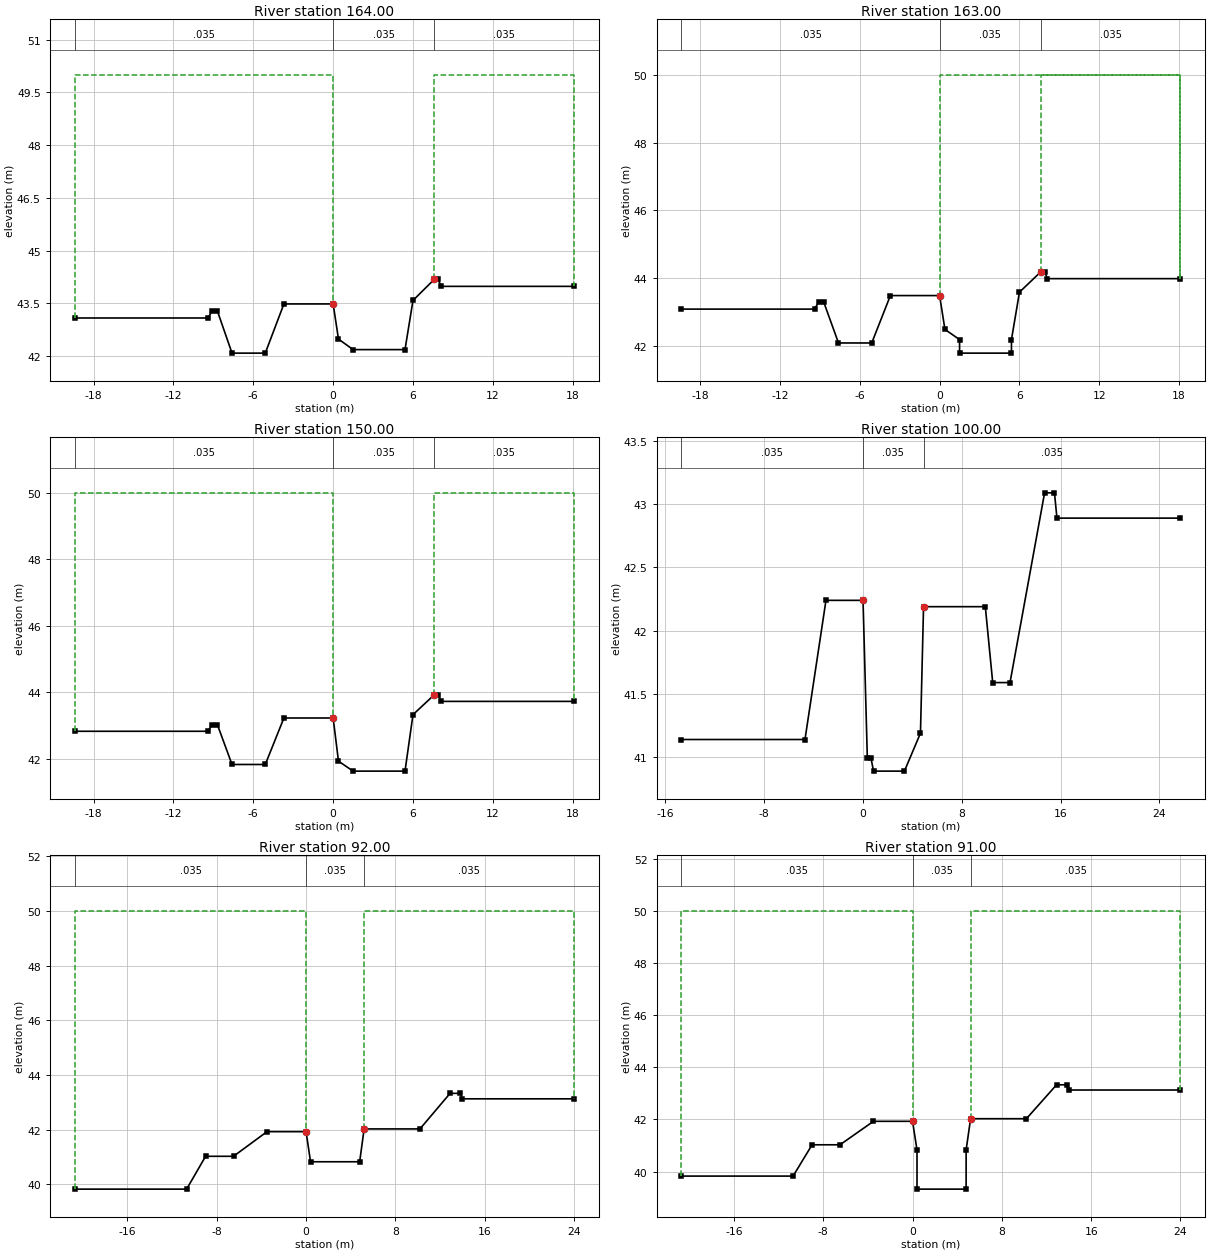
Type RM Length L Ch R = 1 ,164.00  ,1,1,1
BEGIN DESCRIPTION:
3.014
END DESCRIPTION:
#Sta/Elev= 16
   -19.4   43.08    -9.4   43.08    -9.1   43.28    -8.7   43.28    -7.6   42.08
    -5.1   42.08    -3.7   43.48       0   43.48      .4   42.48     1.5   42.18
     5.4   42.18       6   43.58     7.6   44.18     7.9   44.18     8.1   43.98
    18.1   43.98
#Mann= 3 , 0 , 0
   -19.4    .035       0       0    .035       0     7.6    .035       0
#XS Ineff= 2 , 0
               0      50     7.6              50
Permanent Ineff=
       F       F
#Block Obstruct= 2 , 0
                             7.6
Bank Sta=0,7.6
XS Rating Curve= 0
Exp/Cntr=.3,.1

Type RM Length L Ch R = 1 ,163.00  ,13,13,13
BEGIN DESCRIPTION:
3.013
END DESCRIPTION:
#Sta/Elev= 18
   -19.4   43.08    -9.4   43.08    -9.1   43.28    -8.7   43.28    -7.6   42.08
    -5.1   42.08    -3.7   43.48       0   43.48      .4   42.48     1.5   42.18
     1.5   41.78     5.4   41.78     5.4   42.18       6   43.58     7.6   44.18
     7.9   44.18     8.1   43.98    18.1   43.98
#Mann= 3 , 0 , 0
   -19.4    .035       0       0    .035       0     7.6    .035       0
#XS Ineff= 2 , 0
       0       0      50     7.6       0      50
Permanent Ineff=
       F       F
#Block Obstruct= 2 , 0
                             7.6
Bank Sta=0,7.6
XS Rating Curve= 0
Exp/Cntr=.3,.1

Type RM Length L Ch R = 1 ,150.00  ,50,50,50
BEGIN DESCRIPTION:
3
END DESCRIPTION:
#Sta/Elev= 16
   -19.4   42.82    -9.4   42.82    -9.1   43.02    -8.7   43.02    -7.6   41.82
    -5.1   41.82    -3.7   43.22       0   43.22      .4   41.92     1.5   41.62
     5.4   41.62       6   43.32     7.6   43.92     7.9   43.92     8.1   43.72
    18.1   43.72
#Mann= 3 , 0 , 0
   -19.4    .035       0       0    .035       0     7.6    .035       0
#XS Ineff= 2 , 0
               0      50     7.6              50
Permanent Ineff=
       F       F
#Block Obstruct= 2 , 0
                             7.6
Bank Sta=0,7.6
XS Rating Curve= 0
Exp/Cntr=.3,.1

Type RM Length L Ch R = 1 ,100.00  ,8,8,8
BEGIN DESCRIPTION:
2
END DESCRIPTION:
#Sta/Elev= 17
   -14.7   41.14    -4.7   41.14      -3   42.24       0   42.24     .35   40.99
     .65   40.99     .85   40.89    3.35   40.89    4.65   41.19     4.9   42.19
     9.9   42.19    10.5   41.59    11.9   41.59    14.7   43.09    15.5   43.09
    15.7   42.89    25.7   42.89
#Mann= 3 , 0 , 0
   -14.7    .035       0       0    .035       0     4.9    .035       0
#XS Ineff= 2 , 0
               0      50     4.9              50
Permanent Ineff=
       F       F
#Block Obstruct= 2 , 0
                             4.9
Bank Sta=0,4.9
XS Rating Curve= 0
Exp/Cntr=.3,.1

Type RM Length L Ch R = 1 ,92.00   ,1,1,1
BEGIN DESCRIPTION:
1.042
END DESCRIPTION:
#Sta/Elev= 14
   -20.7   39.83   -10.7   39.83      -9   41.03    -6.5   41.03    -3.5   41.93
       0   41.93      .4   40.83     4.8   40.83     5.2   42.03    10.2   42.03
    12.9   43.33    13.8   43.33      14   43.13      24   43.13
#Mann= 3 , 0 , 0
   -20.7    .035       0       0    .035       0     5.2    .035       0
#XS Ineff= 2 , 0
               0      50     5.2              50
Permanent Ineff=
       F       F
#Block Obstruct= 2 , 0
                             5.2
Bank Sta=0,5.2
XS Rating Curve= 0
Exp/Cntr=.3,.1

Type RM Length L Ch R = 1 ,91.00   ,41,41,41
BEGIN DESCRIPTION:
1.041
END DESCRIPTION:
#Sta/Elev= 16
   -20.7   39.83   -10.7   39.83      -9   41.03    -6.5   41.03    -3.5   41.93
       0   41.93      .4   40.83      .4   39.33     4.8   39.33     4.8   40.83
     5.2   42.03    10.2   42.03    12.9   43.33    13.8   43.33      14   43.13
      24   43.13
#Mann= 3 , 0 , 0
   -20.7    .035       0       0    .035       0     5.2    .035       0
#XS Ineff= 2 , 0
               0      50     5.2              50
Permanent Ineff=
       F       F
#Block Obstruct= 2 , 0
                             5.2
Bank Sta=0,5.2
XS Rating Curve= 0
Exp/Cntr=.3,.1

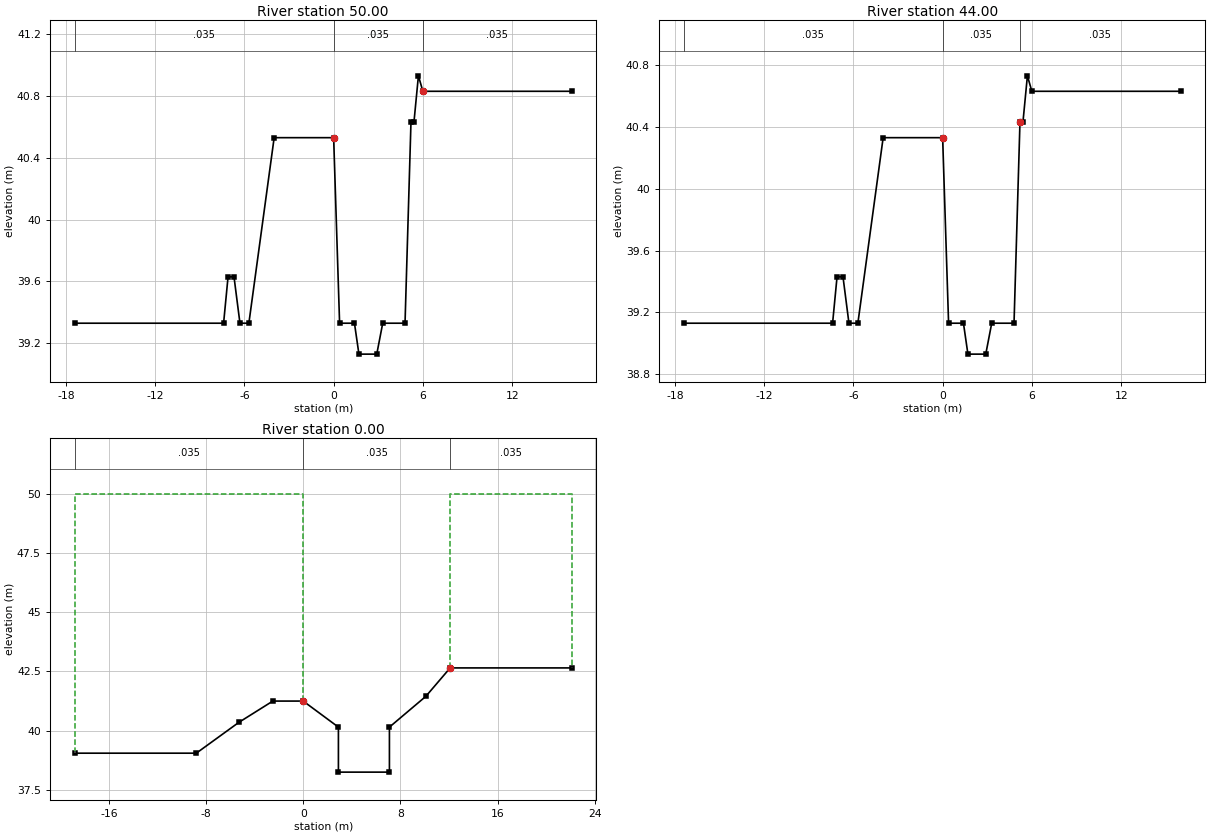
Type RM Length L Ch R = 1 ,50.00   ,6,6,6
BEGIN DESCRIPTION:
1
END DESCRIPTION:
#Sta/Elev= 19
   -17.4   39.33    -7.4   39.33    -7.1   39.63    -6.7   39.63    -6.3   39.33
    -5.7   39.33      -4   40.53       0   40.53      .4   39.33     1.4   39.33
     1.7   39.13     2.9   39.13     3.3   39.33     4.8   39.33     5.2   40.63
     5.4   40.63     5.7   40.93       6   40.83      16   40.83
#Mann= 3 , 0 , 0
   -17.4    .035       0       0    .035       0       6    .035       0
#XS Ineff= 2 , 0
               0      50       6              50
Permanent Ineff=
       F       F
#Block Obstruct= 2 , 0
                               6
Bank Sta=0,6
XS Rating Curve= 0
Exp/Cntr=.3,.1

Type RM Length L Ch R = 1 ,44.00   ,44,44,44
BEGIN DESCRIPTION:
0.044
END DESCRIPTION:
#Sta/Elev= 19
   -17.4   39.13    -7.4   39.13    -7.1   39.43    -6.7   39.43    -6.3   39.13
    -5.7   39.13      -4   40.33       0   40.33      .4   39.13     1.4   39.13
     1.7   38.93     2.9   38.93     3.3   39.13     4.8   39.13     5.2   40.43
     5.4   40.43     5.7   40.73       6   40.63      16   40.63
#Mann= 3 , 0 , 0
   -17.4    .035       0       0    .035       0     5.2    .035       0
#XS Ineff= 2 , 0
               0      50     5.2              50
Permanent Ineff=
       F       F
#Block Obstruct= 2 , 0
                             5.2
Bank Sta=0,5.2
XS Rating Curve= 0
Exp/Cntr=.3,.1

Type RM Length L Ch R = 1 ,0.00    ,0,0,0
BEGIN DESCRIPTION:
0
END DESCRIPTION:
#Sta/Elev= 12
   -18.8   39.05    -8.8   39.05    -5.3   40.35    -2.5   41.25       0   41.25
     2.9   40.15     2.9   38.25     7.1   38.25     7.1   40.15    10.1   41.45
    12.1   42.65    22.1   42.65
#Mann= 3 , 0 , 0
   -18.8    .035       0       0    .035       0    12.1    .035       0
#XS Ineff= 2 , 0
               0      50    12.1              50
Permanent Ineff=
       F       F
#Block Obstruct= 2 , 0
                            12.1
Bank Sta=0,12.1
XS Rating Curve= 0
Exp/Cntr=.3,.1

Chan Stop Cuts=-1