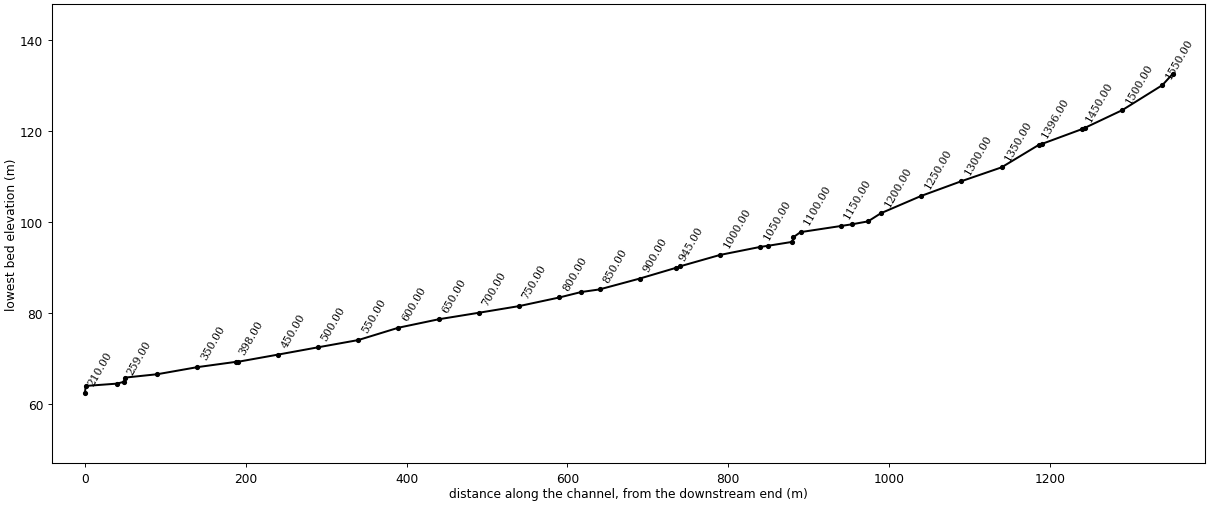
--- IM.prj (project) ---

Proj Title=IM
Current Plan=p01
Default Exp/Contr=.3,.1
SI Units
Geom File=g01
Flow File=f01
Plan File=p01
Y Axis Title=Elevation
X Axis Title(PF)=Main Channel Distance
X Axis Title(XS)=Station
BEGIN DESCRIPTION:
           BACK WATER COMPUTATION
      APPLICATION OF HEC-2 BY Samju Construction Engineering
      emchun-ch: 10,20,30,50,80 yr
END DESCRIPTION:
DSS Export Rating Curves= 0
DSS Export Rating Curve Sorted= 0
DSS Export Volume Flow Curves= 0
DXF OffsetX= 0
DXF OffsetY= 0
DXF ScaleX= 1
DXF ScaleY= 10

--- IM.p01 (plan) ---

Plan Title=Imported Plan 01
Version=Version 3.0.1  Mar 2001
Short Identifier=Imported Pla
Geom File=g01
Flow File=f01
Subcritical Flow
K Sum by GR= 0
Std Step Tol= 0.01
Critical Tol= 0.01
Num of Std Step Trials= 20
Max Error Tol= 0.3
Flow Tol Ratio= 0.001
Split Flow NTrial= 30
Split Flow Tol= 0.02
Split Flow Ratio= 0.02
Log Output Level= 0
Friction Slope Method= 1
Unsteady Friction Slope Method= 2
Parabolic Critical Depth
Global Vel Dist= 0 , 0 , 0
Global Log Level= 0
CheckData=True
Encroach Param=-1 ,0,0, 0
Computation Interval=1HOUR
Output Interval=1HOUR
Run HTab= 0
Run UNet= 0
Run PostProcess= 0
UNET Theta= 1
UNET ZTol= 0.02
UNET ZSATol= 0.1
UNET MxIter= 20
UNET MaxInSteps= 20
UNET DtIC= 0
UNET DtMin= 0
UNET MaxCRTS= 20
UNET WFStab= 2
UNET SFStab= 1
UNET WFX= 1
UNET SFX= 1
UNET Convert EG Bridges=-1
UNET Use Existing IB Tables=-1
Instantaneous Interval=1HOUR
Write IC File= 0
Write Velocity= 0
Write Detailed= 0

--- IM.f01 (steady flow) ---

Flow Title=Imported Flow 01
Version=Version 3.0.1  Mar 2001
Number of Profiles= 5
Profile Names=10YR,20YR,30YR,50YR,80YR
River Rch & RM=RIVER-1,Reach-1         ,1563.00
    6.66    7.34    7.73    8.23    8.69
River Rch & RM=RIVER-1,Reach-1         ,950.00
   10.85   11.96   12.61   13.42   14.17
Boundary for River Rch & Prof#=RIVER-1,Reach-1         , 1
Up Type= 0
Dn Type= 3
Dn Slope=.064
Boundary for River Rch & Prof#=RIVER-1,Reach-1         , 2
Up Type= 0
Dn Type= 3
Dn Slope=.064
Boundary for River Rch & Prof#=RIVER-1,Reach-1         , 3
Up Type= 0
Dn Type= 3
Dn Slope=.064
Boundary for River Rch & Prof#=RIVER-1,Reach-1         , 4
Up Type= 0
Dn Type= 3
Dn Slope=.064
Boundary for River Rch & Prof#=RIVER-1,Reach-1         , 5
Up Type= 0
Dn Type= 3
Dn Slope=.064
DSS Import GetInterval= 0
DSS Import GetPeak= 0
DSS Import FillOption= 0

--- IM.g01 (geometry) ---

Geom Title=Imported Geom 01
Version=Version 3.0.1  Mar 2001

River Reach=RIVER-1         ,Reach-1
Reach XY= 2
              .5             .95              .5             .05

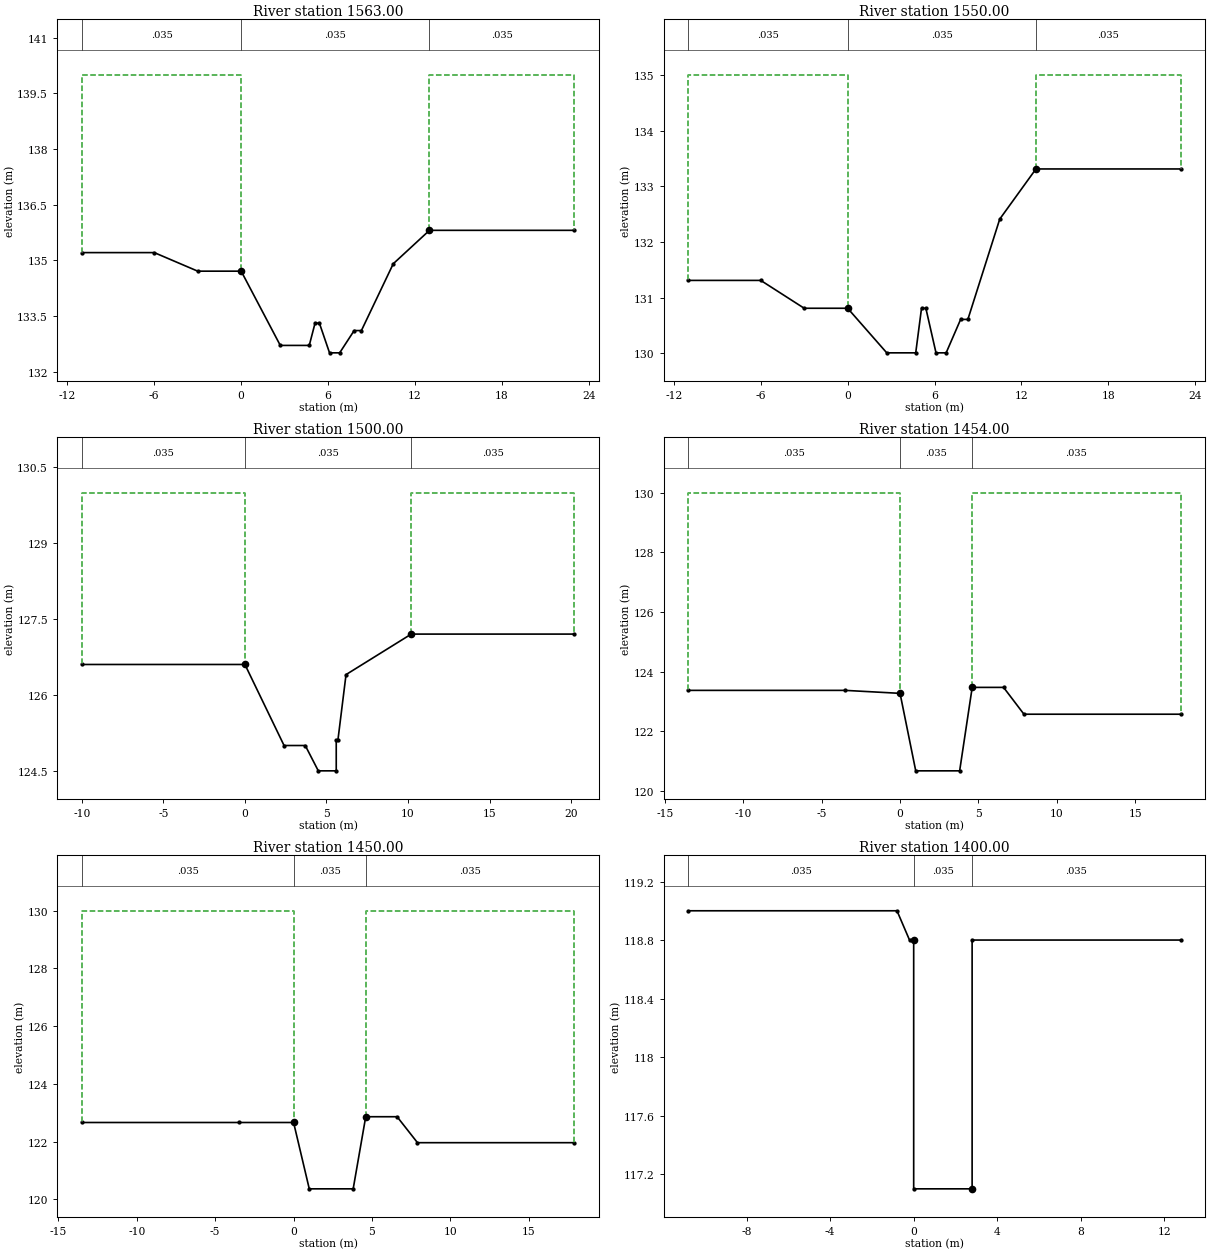
Type RM Length L Ch R = 1 ,1563.00 ,13,13,13
BEGIN DESCRIPTION:
31.013
END DESCRIPTION:
#Sta/Elev= 15
     -11  135.21      -6  135.21      -3  134.71       0  134.71     2.7  132.71
     4.7  132.71     5.1  133.31     5.4  133.31     6.1  132.51     6.8  132.51
     7.8  133.11     8.3  133.11    10.5  134.91      13  135.81      23  135.81
#Mann= 3 , 0 , 0
     -11    .035       0       0    .035       0      13    .035       0
#XS Ineff= 2 , 0
               0     140      13             140
Permanent Ineff=
       F       F
#Block Obstruct= 2 , 0
                              13
Bank Sta=0,13
XS Rating Curve= 0
Exp/Cntr=.3,.1

Type RM Length L Ch R = 1 ,1550.00 ,50,50,50
BEGIN DESCRIPTION:
31
END DESCRIPTION:
#Sta/Elev= 15
     -11  131.31      -6  131.31      -3  130.81       0  130.81     2.7  130.01
     4.7  130.01     5.1  130.81     5.4  130.81     6.1  130.01     6.8  130.01
     7.8  130.61     8.3  130.61    10.5  132.41      13  133.31      23  133.31
#Mann= 3 , 0 , 0
     -11    .035       0       0    .035       0      13    .035       0
#XS Ineff= 2 , 0
               0     135      13             135
Permanent Ineff=
       F       F
#Block Obstruct= 2 , 0
                              13
Bank Sta=0,13
XS Rating Curve= 0
Exp/Cntr=.3,.1

Type RM Length L Ch R = 1 ,1500.00 ,46,46,46
BEGIN DESCRIPTION:
30
END DESCRIPTION:
#Sta/Elev= 11
     -10  126.61       0  126.61     2.4  125.01     3.7  125.01     4.5  124.51
     5.6  124.51     5.6  125.11     5.7  125.11     6.2  126.41    10.2  127.21
    20.2  127.21
#Mann= 3 , 0 , 0
     -10    .035       0       0    .035       0    10.2    .035       0
#XS Ineff= 2 , 0
               0     130    10.2             130
Permanent Ineff=
       F       F
#Block Obstruct= 2 , 0
                            10.2
Bank Sta=0,10.2
XS Rating Curve= 0
Exp/Cntr=.3,.1

Type RM Length L Ch R = 1 ,1454.00 ,4,4,4
BEGIN DESCRIPTION:
29.004
END DESCRIPTION:
#Sta/Elev= 9
   -13.5  123.37    -3.5  123.37       0  123.27       1  120.67     3.8  120.67
     4.6  123.47     6.6  123.47     7.9  122.57    17.9  122.57
#Mann= 3 , 0 , 0
   -13.5    .035       0       0    .035       0     4.6    .035       0
#XS Ineff= 2 , 0
               0     130     4.6             130
Permanent Ineff=
       F       F
#Block Obstruct= 2 , 0
                             4.6
Bank Sta=0,4.6
XS Rating Curve= 0
Exp/Cntr=.3,.1

Type RM Length L Ch R = 1 ,1450.00 ,50,50,50
BEGIN DESCRIPTION:
29
END DESCRIPTION:
#Sta/Elev= 9
   -13.5  122.66    -3.5  122.66       0  122.66       1  120.36     3.8  120.36
     4.6  122.86     6.6  122.86     7.9  121.96    17.9  121.96
#Mann= 3 , 0 , 0
   -13.5    .035       0       0    .035       0     4.6    .035       0
#XS Ineff= 2 , 0
               0     130     4.6             130
Permanent Ineff=
       F       F
#Block Obstruct= 2 , 0
                             4.6
Bank Sta=0,4.6
XS Rating Curve= 0
Exp/Cntr=.3,.1

Type RM Length L Ch R = 1 ,1400.00 ,4,4,4
BEGIN DESCRIPTION:
28
END DESCRIPTION:
#Sta/Elev= 8
   -10.8     119     -.8     119     -.2   118.8       0   118.8       0   117.1
     2.8   117.1     2.8   118.8    12.8   118.8
#Mann= 3 , 0 , 0
   -10.8    .035       0       0    .035       0     2.8    .035       0
#XS Ineff= 2 , 0
               0     130     2.8             130
Permanent Ineff=
       F       F
#Block Obstruct= 2 , 0
                             2.8
Bank Sta=0,2.8
XS Rating Curve= 0
Exp/Cntr=.3,.1

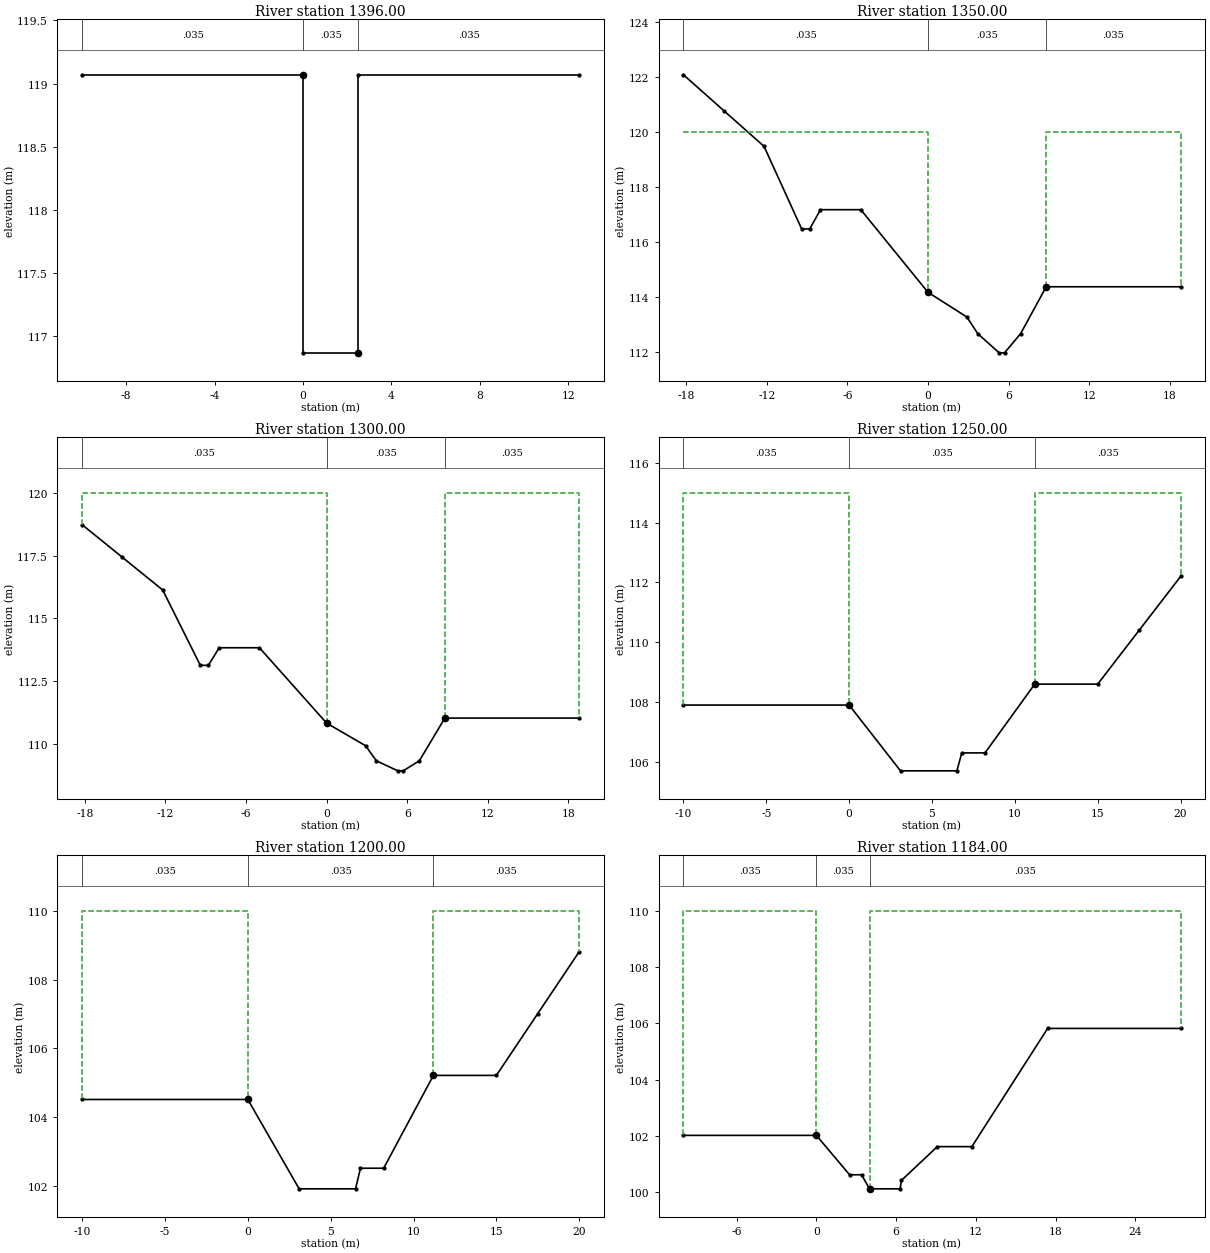
Type RM Length L Ch R = 1 ,1396.00 ,46,46,46
BEGIN DESCRIPTION:
27.046
END DESCRIPTION:
#Sta/Elev= 6
     -10  119.07       0  119.07       0  116.87     2.5  116.87     2.5  119.07
    12.5  119.07
#Mann= 3 , 0 , 0
     -10    .035       0       0    .035       0     2.5    .035       0
#XS Ineff= 2 , 0
               0     130     2.5             130
Permanent Ineff=
       F       F
#Block Obstruct= 2 , 0
                             2.5
Bank Sta=0,2.5
XS Rating Curve= 0
Exp/Cntr=.3,.1

Type RM Length L Ch R = 1 ,1350.00 ,50,50,50
BEGIN DESCRIPTION:
27
END DESCRIPTION:
#Sta/Elev= 15
   -18.2  122.07   -15.2  120.77   -12.2  119.47    -9.4  116.47    -8.8  116.47
      -8  117.17      -5  117.17       0  114.17     2.9  113.27     3.7  112.67
     5.3  111.97     5.7  111.97     6.9  112.67     8.8  114.37    18.8  114.37
#Mann= 3 , 0 , 0
   -18.2    .035       0       0    .035       0     8.8    .035       0
#XS Ineff= 2 , 0
               0     120     8.8             120
Permanent Ineff=
       F       F
#Block Obstruct= 2 , 0
                             8.8
Bank Sta=0,8.8
XS Rating Curve= 0
Exp/Cntr=.3,.1

Type RM Length L Ch R = 1 ,1300.00 ,50,50,50
BEGIN DESCRIPTION:
26
END DESCRIPTION:
#Sta/Elev= 15
   -18.2  118.73   -15.2  117.43   -12.2  116.13    -9.4  113.13    -8.8  113.13
      -8  113.83      -5  113.83       0  110.83     2.9  109.93     3.7  109.33
     5.3  108.93     5.7  108.93     6.9  109.33     8.8  111.03    18.8  111.03
#Mann= 3 , 0 , 0
   -18.2    .035       0       0    .035       0     8.8    .035       0
#XS Ineff= 2 , 0
               0     120     8.8             120
Permanent Ineff=
       F       F
#Block Obstruct= 2 , 0
                             8.8
Bank Sta=0,8.8
XS Rating Curve= 0
Exp/Cntr=.3,.1

Type RM Length L Ch R = 1 ,1250.00 ,50,50,50
BEGIN DESCRIPTION:
25
END DESCRIPTION:
#Sta/Elev= 10
     -10   107.9       0   107.9     3.1   105.7     6.5   105.7     6.8   106.3
     8.2   106.3    11.2   108.6      15   108.6    17.5   110.4      20   112.2
#Mann= 3 , 0 , 0
     -10    .035       0       0    .035       0    11.2    .035       0
#XS Ineff= 2 , 0
               0     115    11.2             115
Permanent Ineff=
       F       F
#Block Obstruct= 2 , 0
                            11.2
Bank Sta=0,11.2
XS Rating Curve= 0
Exp/Cntr=.3,.1

Type RM Length L Ch R = 1 ,1200.00 ,16,16,16
BEGIN DESCRIPTION:
24
END DESCRIPTION:
#Sta/Elev= 10
     -10  104.51       0  104.51     3.1  101.91     6.5  101.91     6.8  102.51
     8.2  102.51    11.2  105.21      15  105.21    17.5  107.01      20  108.81
#Mann= 3 , 0 , 0
     -10    .035       0       0    .035       0    11.2    .035       0
#XS Ineff= 2 , 0
               0     110    11.2             110
Permanent Ineff=
       F       F
#Block Obstruct= 2 , 0
                            11.2
Bank Sta=0,11.2
XS Rating Curve= 0
Exp/Cntr=.3,.1

Type RM Length L Ch R = 1 ,1184.00 ,20,20,20
BEGIN DESCRIPTION:
23.034
END DESCRIPTION:
#Sta/Elev= 11
     -10  102.02       0  102.02     2.5  100.62     3.4  100.62       4  100.12
     6.3  100.12     6.4  100.42     9.1  101.62    11.7  101.62    17.4  105.82
    27.4  105.82
#Mann= 3 , 0 , 0
     -10    .035       0       0    .035       0       4    .035       0
#XS Ineff= 2 , 0
               0     110       4             110
Permanent Ineff=
       F       F
#Block Obstruct= 2 , 0
                               4
Bank Sta=0,4
XS Rating Curve= 0
Exp/Cntr=.3,.1

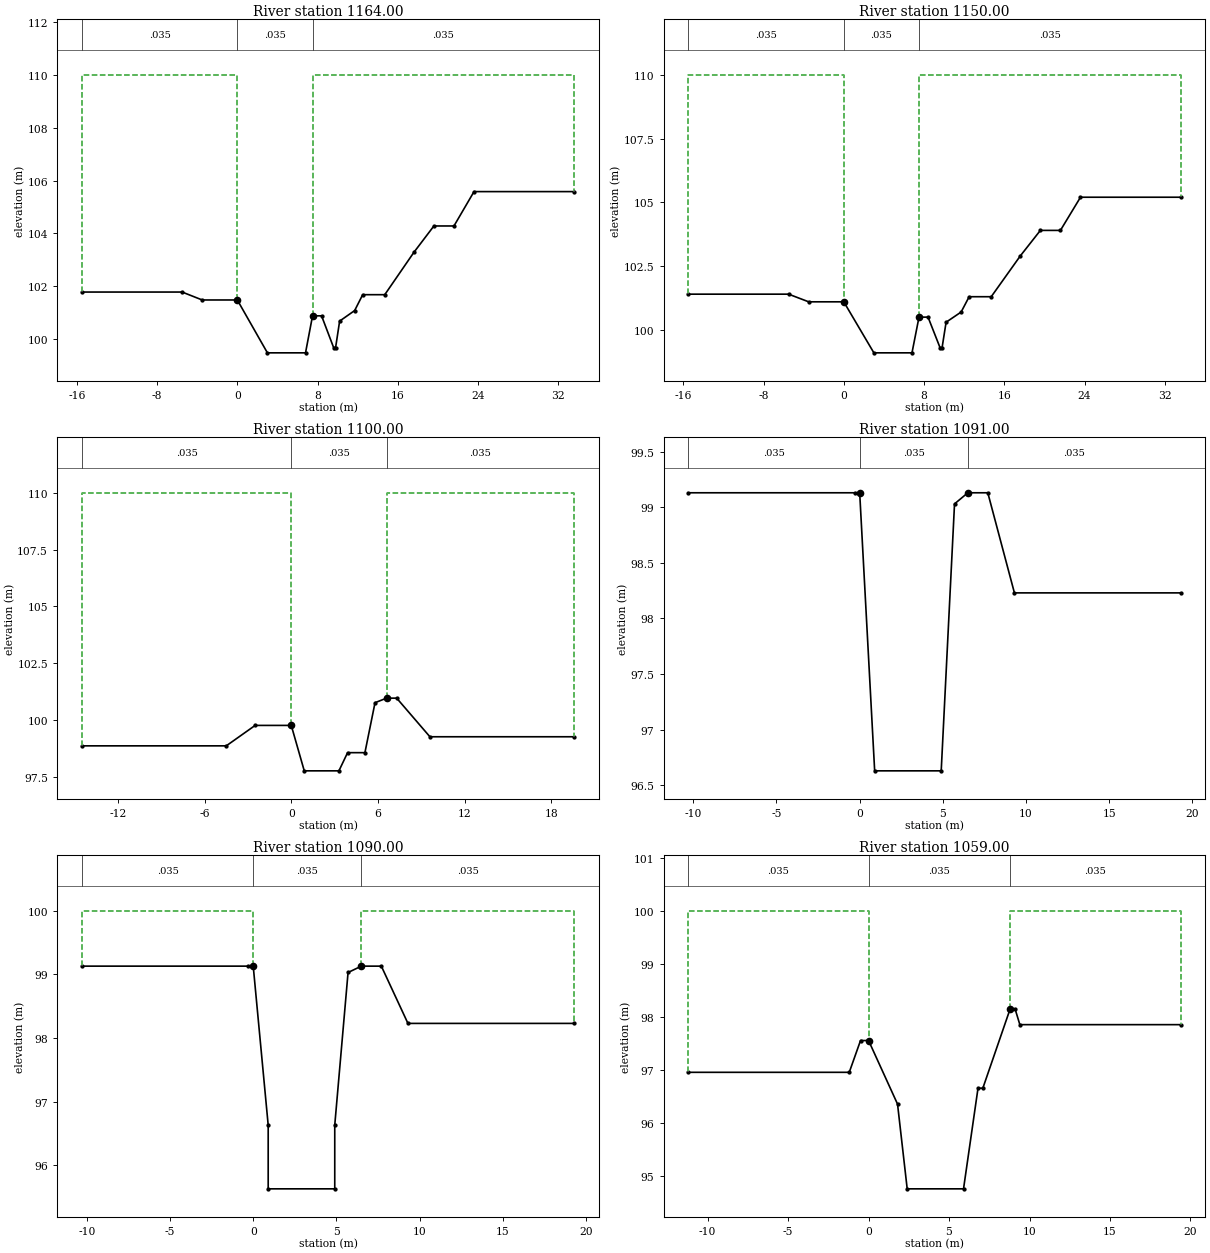
Type RM Length L Ch R = 1 ,1164.00 ,14,14,14
BEGIN DESCRIPTION:
23.014
END DESCRIPTION:
#Sta/Elev= 19
   -15.5  101.78    -5.5  101.78    -3.5  101.48       0  101.48       3   99.48
     6.8   99.48     7.5  100.88     8.4  100.88     9.6   99.68     9.8   99.68
    10.2  100.68    11.7  101.08    12.5  101.68    14.7  101.68    17.6  103.28
    19.6  104.28    21.6  104.28    23.6  105.58    33.6  105.58
#Mann= 3 , 0 , 0
   -15.5    .035       0       0    .035       0     7.5    .035       0
#XS Ineff= 2 , 0
               0     110     7.5             110
Permanent Ineff=
       F       F
#Block Obstruct= 2 , 0
                             7.5
Bank Sta=0,7.5
XS Rating Curve= 0
Exp/Cntr=.3,.1

Type RM Length L Ch R = 1 ,1150.00 ,50,50,50
BEGIN DESCRIPTION:
23
END DESCRIPTION:
#Sta/Elev= 19
   -15.5   101.4    -5.5   101.4    -3.5   101.1       0   101.1       3    99.1
     6.8    99.1     7.5   100.5     8.4   100.5     9.6    99.3     9.8    99.3
    10.2   100.3    11.7   100.7    12.5   101.3    14.7   101.3    17.6   102.9
    19.6   103.9    21.6   103.9    23.6   105.2    33.6   105.2
#Mann= 3 , 0 , 0
   -15.5    .035       0       0    .035       0     7.5    .035       0
#XS Ineff= 2 , 0
               0     110     7.5             110
Permanent Ineff=
       F       F
#Block Obstruct= 2 , 0
                             7.5
Bank Sta=0,7.5
XS Rating Curve= 0
Exp/Cntr=.3,.1

Type RM Length L Ch R = 1 ,1100.00 ,9,9,9
BEGIN DESCRIPTION:
22
END DESCRIPTION:
#Sta/Elev= 13
   -14.5   98.86    -4.5   98.86    -2.5   99.76       0   99.76      .9   97.76
     3.3   97.76     3.9   98.56     5.1   98.56     5.8  100.76     6.6  100.96
     7.3  100.96     9.6   99.26    19.6   99.26
#Mann= 3 , 0 , 0
   -14.5    .035       0       0    .035       0     6.6    .035       0
#XS Ineff= 2 , 0
               0     110     6.6             110
Permanent Ineff=
       F       F
#Block Obstruct= 2 , 0
                             6.6
Bank Sta=0,6.6
XS Rating Curve= 0
Exp/Cntr=.3,.1

Type RM Length L Ch R = 1 ,1091.00 ,1,1,1
BEGIN DESCRIPTION:
21.041
END DESCRIPTION:
#Sta/Elev= 10
   -10.3   99.13     -.3   99.13       0   99.13      .9   96.63     4.9   96.63
     5.7   99.03     6.5   99.13     7.7   99.13     9.3   98.23    19.3   98.23
#Mann= 3 , 0 , 0
   -10.3    .035       0       0    .035       0     6.5    .035       0
#XS Ineff= 2 , 0
               0     110     6.5             110
Permanent Ineff=
       F       F
#Block Obstruct= 2 , 0
                             6.5
Bank Sta=0,6.5
XS Rating Curve= 0
Exp/Cntr=.3,.1

Type RM Length L Ch R = 1 ,1090.00 ,31,31,31
BEGIN DESCRIPTION:
21.04
END DESCRIPTION:
#Sta/Elev= 12
   -10.3   99.13     -.3   99.13       0   99.13      .9   96.63      .9   95.63
     4.9   95.63     4.9   96.63     5.7   99.03     6.5   99.13     7.7   99.13
     9.3   98.23    19.3   98.23
#Mann= 3 , 0 , 0
   -10.3    .035       0       0    .035       0     6.5    .035       0
#XS Ineff= 2 , 0
               0     100     6.5             100
Permanent Ineff=
       F       F
#Block Obstruct= 2 , 0
                             6.5
Bank Sta=0,6.5
XS Rating Curve= 0
Exp/Cntr=.3,.1

Type RM Length L Ch R = 1 ,1059.00 ,9,9,9
BEGIN DESCRIPTION:
21.009
END DESCRIPTION:
#Sta/Elev= 13
   -11.2   96.95    -1.2   96.95     -.5   97.55       0   97.55     1.8   96.35
     2.4   94.75     5.9   94.75     6.8   96.65     7.1   96.65     8.8   98.15
     9.1   98.15     9.4   97.85    19.4   97.85
#Mann= 3 , 0 , 0
   -11.2    .035       0       0    .035       0     8.8    .035       0
#XS Ineff= 2 , 0
               0     100     8.8             100
Permanent Ineff=
       F       F
#Block Obstruct= 2 , 0
                             8.8
Bank Sta=0,8.8
XS Rating Curve= 0
Exp/Cntr=.3,.1

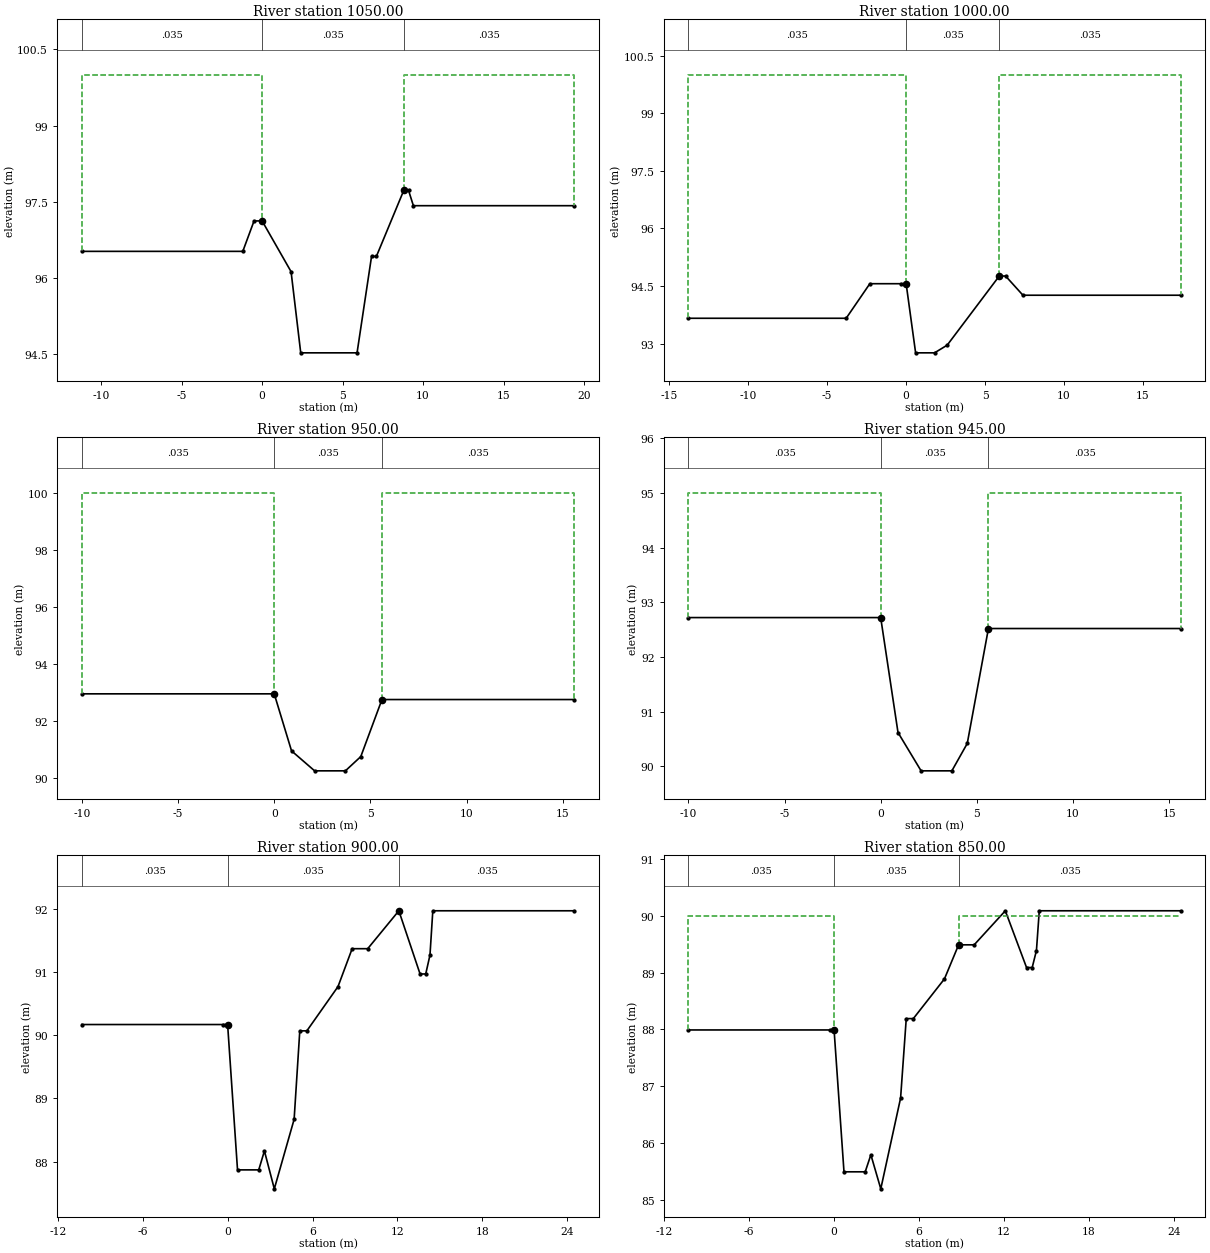
Type RM Length L Ch R = 1 ,1050.00 ,50,50,50
BEGIN DESCRIPTION:
21
END DESCRIPTION:
#Sta/Elev= 13
   -11.2   96.52    -1.2   96.52     -.5   97.12       0   97.12     1.8   96.12
     2.4   94.52     5.9   94.52     6.8   96.42     7.1   96.42     8.8   97.72
     9.1   97.72     9.4   97.42    19.4   97.42
#Mann= 3 , 0 , 0
   -11.2    .035       0       0    .035       0     8.8    .035       0
#XS Ineff= 2 , 0
               0     100     8.8             100
Permanent Ineff=
       F       F
#Block Obstruct= 2 , 0
                             8.8
Bank Sta=0,8.8
XS Rating Curve= 0
Exp/Cntr=.3,.1

Type RM Length L Ch R = 1 ,1000.00 ,50,50,50
BEGIN DESCRIPTION:
20
END DESCRIPTION:
#Sta/Elev= 12
   -13.8   93.66    -3.8   93.66    -2.3   94.56     -.3   94.56       0   94.56
      .6   92.76     1.8   92.76     2.6   92.96     5.9   94.76     6.3   94.76
     7.4   94.26    17.4   94.26
#Mann= 3 , 0 , 0
   -13.8    .035       0       0    .035       0     5.9    .035       0
#XS Ineff= 2 , 0
               0     100     5.9             100
Permanent Ineff=
       F       F
#Block Obstruct= 2 , 0
                             5.9
Bank Sta=0,5.9
XS Rating Curve= 0
Exp/Cntr=.3,.1

Type RM Length L Ch R = 1 ,950.00  ,5,5,5
BEGIN DESCRIPTION:
19
END DESCRIPTION:
#Sta/Elev= 8
     -10   92.95       0   92.95      .9   90.95     2.1   90.25     3.7   90.25
     4.5   90.75     5.6   92.75    15.6   92.75
#Mann= 3 , 0 , 0
     -10    .035       0       0    .035       0     5.6    .035       0
#XS Ineff= 2 , 0
               0     100     5.6             100
Permanent Ineff=
       F       F
#Block Obstruct= 2 , 0
                             5.5
Bank Sta=0,5.6
XS Rating Curve= 0
Exp/Cntr=.3,.1

Type RM Length L Ch R = 1 ,945.00  ,45,45,45
BEGIN DESCRIPTION:
18.045
END DESCRIPTION:
#Sta/Elev= 8
     -10   92.72       0   92.72      .9   90.62     2.1   89.92     3.7   89.92
     4.5   90.42     5.6   92.52    15.6   92.52
#Mann= 3 , 0 , 0
     -10    .035       0       0    .035       0     5.6    .035       0
#XS Ineff= 2 , 0
               0      95     5.6              95
Permanent Ineff=
       F       F
#Block Obstruct= 2 , 0
                             5.6
Bank Sta=0,5.6
XS Rating Curve= 0
Exp/Cntr=.3,.1

Type RM Length L Ch R = 1 ,900.00  ,50,50,50
BEGIN DESCRIPTION:
18
END DESCRIPTION:
#Sta/Elev= 19
   -10.3   90.17     -.3   90.17       0   90.17      .7   87.87     2.2   87.87
     2.6   88.17     3.3   87.57     4.7   88.67     5.1   90.07     5.6   90.07
     7.8   90.77     8.8   91.37     9.9   91.37    12.1   91.97    13.6   90.97
      14   90.97    14.3   91.27    14.5   91.97    24.5   91.97
#Mann= 3 , 0 , 0
   -10.3    .035       0       0    .035       0    12.1    .035       0
#XS Ineff= 2 , 0
               0      90    12.1              90
Permanent Ineff=
       F       F
#Block Obstruct= 2 , 0
                            12.1
Bank Sta=0,12.1
XS Rating Curve= 0
Exp/Cntr=.3,.1

Type RM Length L Ch R = 1 ,850.00  ,23,23,23
BEGIN DESCRIPTION:
17
END DESCRIPTION:
#Sta/Elev= 19
   -10.3   87.99     -.3   87.99       0   87.99      .7   85.49     2.2   85.49
     2.6   85.79     3.3   85.19     4.7   86.79     5.1   88.19     5.6   88.19
     7.8   88.89     8.8   89.49     9.9   89.49    12.1   90.09    13.6   89.09
      14   89.09    14.3   89.39    14.5   90.09    24.5   90.09
#Mann= 3 , 0 , 0
   -10.3    .035       0       0    .035       0     8.8    .035       0
#XS Ineff= 2 , 0
               0      90     8.8              90
Permanent Ineff=
       F       F
#Block Obstruct= 2 , 0
                             8.8
Bank Sta=0,8.8
XS Rating Curve= 0
Exp/Cntr=.3,.1

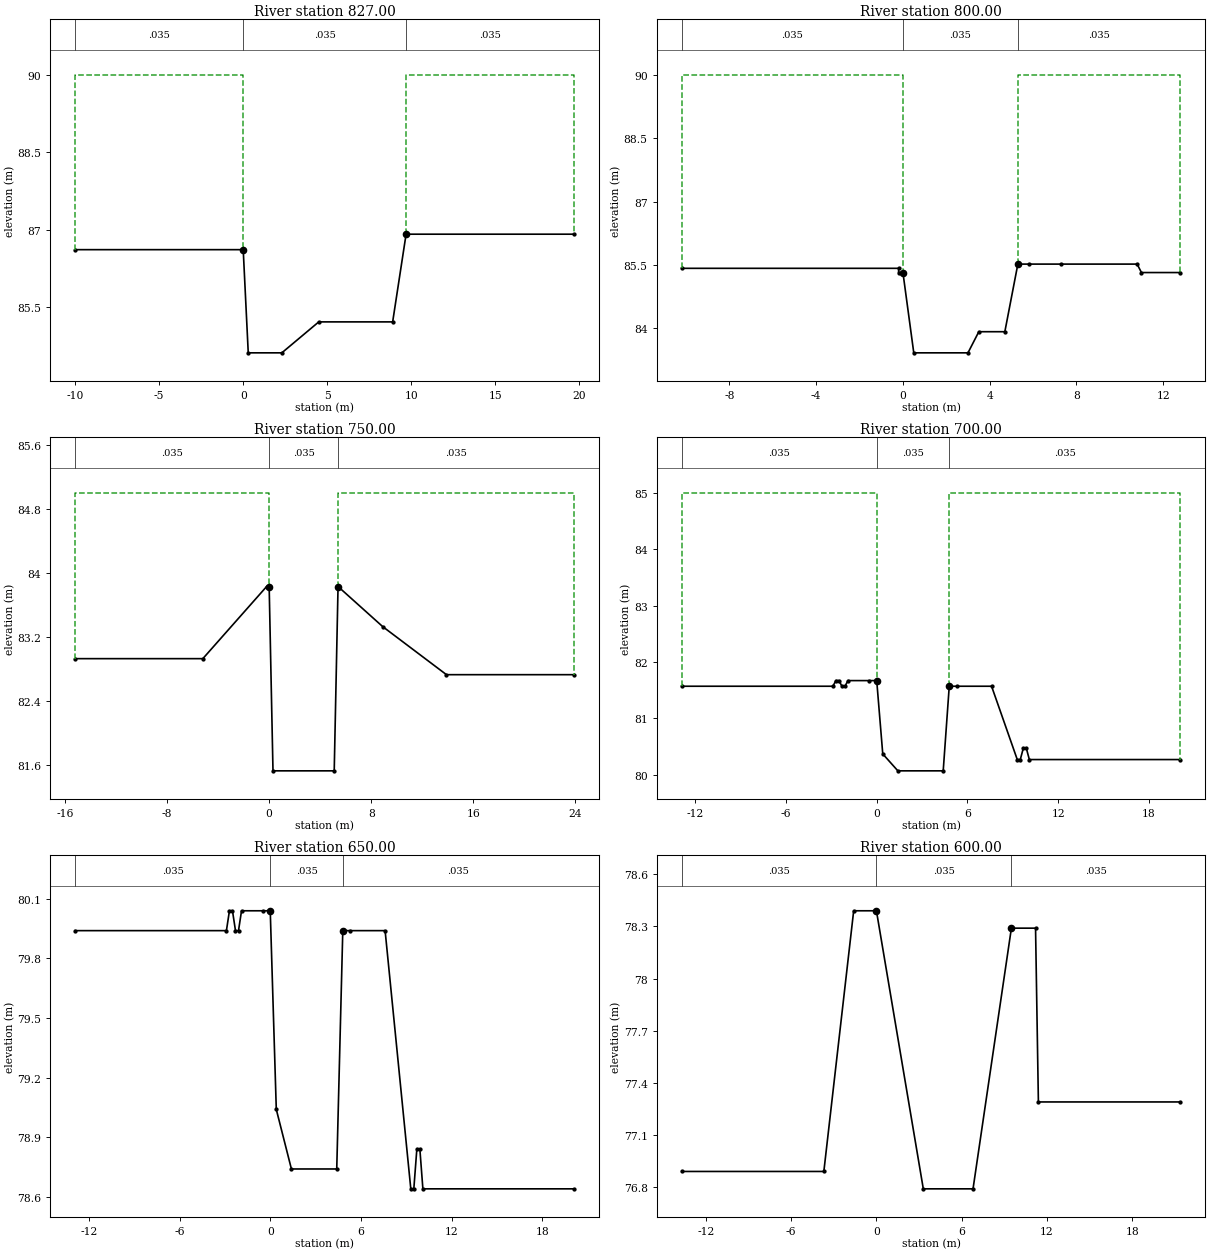
Type RM Length L Ch R = 1 ,827.00  ,27,27,27
BEGIN DESCRIPTION:
16.027
END DESCRIPTION:
#Sta/Elev= 8
     -10   86.61       0   86.61      .3   84.61     2.3   84.61     4.5   85.21
     8.9   85.21     9.7   86.91    19.7   86.91
#Mann= 3 , 0 , 0
     -10    .035       0       0    .035       0     9.7    .035       0
#XS Ineff= 2 , 0
               0      90     9.7              90
Permanent Ineff=
       F       F
#Block Obstruct= 2 , 0
                             9.7
Bank Sta=0,9.7
XS Rating Curve= 0
Exp/Cntr=.3,.1

Type RM Length L Ch R = 1 ,800.00  ,50,50,50
BEGIN DESCRIPTION:
16
END DESCRIPTION:
#Sta/Elev= 14
   -10.2   85.42     -.2   85.42     -.2   85.32       0   85.32      .5   83.42
       3   83.42     3.5   83.92     4.7   83.92     5.3   85.52     5.8   85.52
     7.3   85.52    10.8   85.52      11   85.32    12.8   85.32
#Mann= 3 , 0 , 0
   -10.2    .035       0       0    .035       0     5.3    .035       0
#XS Ineff= 2 , 0
               0      90     5.3              90
Permanent Ineff=
       F       F
#Block Obstruct= 2 , 0
                             5.3
Bank Sta=0,5.3
XS Rating Curve= 0
Exp/Cntr=.3,.1

Type RM Length L Ch R = 1 ,750.00  ,50,50,50
BEGIN DESCRIPTION:
15
END DESCRIPTION:
#Sta/Elev= 10
   -15.2   82.93    -5.2   82.93     -.2   83.83       0   83.83      .3   81.53
     5.1   81.53     5.4   83.83     8.9   83.33    13.9   82.73    23.9   82.73
#Mann= 3 , 0 , 0
   -15.2    .035       0       0    .035       0     5.4    .035       0
#XS Ineff= 2 , 0
               0      85     5.4              85
Permanent Ineff=
       F       F
#Block Obstruct= 2 , 0
                             5.4
Bank Sta=0,5.4
XS Rating Curve= 0
Exp/Cntr=.3,.1

Type RM Length L Ch R = 1 ,700.00  ,50,50,50
BEGIN DESCRIPTION:
14
END DESCRIPTION:
#Sta/Elev= 21
   -12.9   81.57    -2.9   81.57    -2.7   81.67    -2.5   81.67    -2.3   81.57
    -2.1   81.57    -1.9   81.67     -.5   81.67       0   81.67      .4   80.37
     1.4   80.07     4.4   80.07     4.8   81.57     5.3   81.57     7.6   81.57
     9.3   80.27     9.5   80.27     9.7   80.47     9.9   80.47    10.1   80.27
    20.1   80.27
#Mann= 3 , 0 , 0
   -12.9    .035       0       0    .035       0     4.8    .035       0
#XS Ineff= 2 , 0
               0      85     4.8              85
Permanent Ineff=
       F       F
#Block Obstruct= 2 , 0
                             4.8
Bank Sta=0,4.8
XS Rating Curve= 0
Exp/Cntr=.3,.1

Type RM Length L Ch R = 1 ,650.00  ,50,50,50
BEGIN DESCRIPTION:
13
END DESCRIPTION:
#Sta/Elev= 21
   -12.9   79.94    -2.9   79.94    -2.7   80.04    -2.5   80.04    -2.3   79.94
    -2.1   79.94    -1.9   80.04     -.5   80.04       0   80.04      .4   79.04
     1.4   78.74     4.4   78.74     4.8   79.94     5.3   79.94     7.6   79.94
     9.3   78.64     9.5   78.64     9.7   78.84     9.9   78.84    10.1   78.64
    20.1   78.64
#Mann= 3 , 0 , 0
   -12.9    .035       0       0    .035       0     4.8    .035       0
#XS Ineff= 2 , 0
               0      85     4.8              85
Permanent Ineff=
       F       F
#Block Obstruct= 2 , 0
                             4.8
Bank Sta=0,4.8
XS Rating Curve= 0
Exp/Cntr=.3,.1

Type RM Length L Ch R = 1 ,600.00  ,50,50,50
BEGIN DESCRIPTION:
12
END DESCRIPTION:
#Sta/Elev= 10
   -13.7   76.89    -3.7   76.89    -1.6   78.39       0   78.39     3.3   76.79
     6.8   76.79     9.5   78.29    11.2   78.29    11.4   77.29    21.4   77.29
#Mann= 3 , 0 , 0
   -13.7    .035       0       0    .035       0     9.5    .035       0
#XS Ineff= 2 , 0
               0      85     9.5              85
Permanent Ineff=
       F       F
#Block Obstruct= 2 , 0
                             9.5
Bank Sta=0,9.5
XS Rating Curve= 0
Exp/Cntr=.3,.1

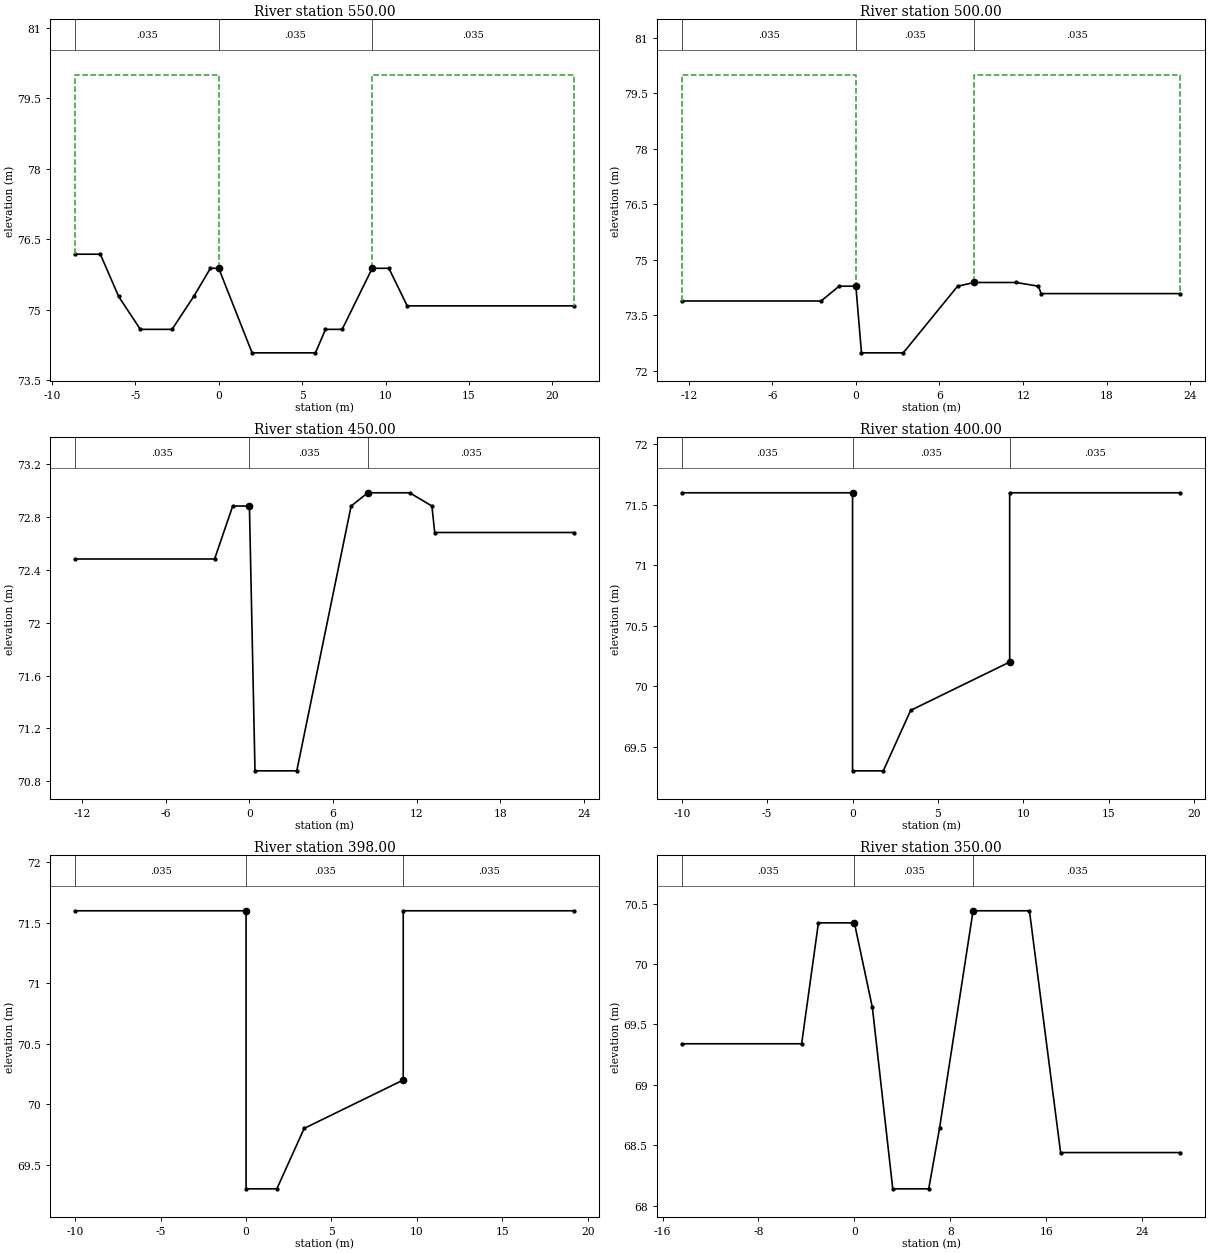
Type RM Length L Ch R = 1 ,550.00  ,50,50,50
BEGIN DESCRIPTION:
11
END DESCRIPTION:
#Sta/Elev= 16
    -8.6   76.18    -7.1   76.18      -6   75.28    -4.7   74.58    -2.8   74.58
    -1.5   75.28     -.5   75.88       0   75.88       2   74.08     5.8   74.08
     6.4   74.58     7.4   74.58     9.2   75.88    10.2   75.88    11.3   75.08
    21.3   75.08
#Mann= 3 , 0 , 0
    -8.6    .035       0       0    .035       0     9.2    .035       0
#XS Ineff= 2 , 0
               0      80     9.2              80
Permanent Ineff=
       F       F
#Block Obstruct= 2 , 0
                             9.2
Bank Sta=0,9.2
XS Rating Curve= 0
Exp/Cntr=.3,.1

Type RM Length L Ch R = 1 ,500.00  ,50,50,50
BEGIN DESCRIPTION:
10
END DESCRIPTION:
#Sta/Elev= 12
   -12.5   73.89    -2.5   73.89    -1.2   74.29       0   74.29      .4   72.49
     3.4   72.49     7.3   74.29     8.5   74.39    11.5   74.39    13.1   74.29
    13.3   74.09    23.3   74.09
#Mann= 3 , 0 , 0
   -12.5    .035       0       0    .035       0     8.5    .035       0
#XS Ineff= 2 , 0
               0      80     8.5              80
Permanent Ineff=
       F       F
#Block Obstruct= 2 , 0
                             8.5
Bank Sta=0,8.5
XS Rating Curve= 0
Exp/Cntr=.3,.1

Type RM Length L Ch R = 1 ,450.00  ,50,50,50
BEGIN DESCRIPTION:
9
END DESCRIPTION:
#Sta/Elev= 12
   -12.5   72.48    -2.5   72.48    -1.2   72.88       0   72.88      .4   70.88
     3.4   70.88     7.3   72.88     8.5   72.98    11.5   72.98    13.1   72.88
    13.3   72.68    23.3   72.68
#Mann= 3 , 0 , 0
   -12.5    .035       0       0    .035       0     8.5    .035       0
#XS Ineff= 2 , 0
               0      80     8.5              80
Permanent Ineff=
       F       F
#Block Obstruct= 2 , 0
                             8.5
Bank Sta=0,8.5
XS Rating Curve= 0
Exp/Cntr=.3,.1

Type RM Length L Ch R = 1 ,400.00  ,2,2,2
BEGIN DESCRIPTION:
8
END DESCRIPTION:
#Sta/Elev= 8
     -10    71.6       0    71.6       0    69.3     1.8    69.3     3.4    69.8
     9.2    70.2     9.2    71.6    19.2    71.6
#Mann= 3 , 0 , 0
     -10    .035       0       0    .035       0     9.2    .035       0
#XS Ineff= 2 , 0
               0      80     9.2              80
Permanent Ineff=
       F       F
#Block Obstruct= 2 , 0
                             9.2
Bank Sta=0,9.2
XS Rating Curve= 0
Exp/Cntr=.3,.1

Type RM Length L Ch R = 1 ,398.00  ,48,48,48
BEGIN DESCRIPTION:
7.048
END DESCRIPTION:
#Sta/Elev= 8
     -10    71.6       0    71.6       0    69.3     1.8    69.3     3.4    69.8
     9.2    70.2     9.2    71.6    19.2    71.6
#Mann= 3 , 0 , 0
     -10    .035       0       0    .035       0     9.2    .035       0
#XS Ineff= 2 , 0
               0      80     9.2              80
Permanent Ineff=
       F       F
#Block Obstruct= 2 , 0
                             9.2
Bank Sta=0,9.2
XS Rating Curve= 0
Exp/Cntr=.3,.1

Type RM Length L Ch R = 1 ,350.00  ,50,50,50
BEGIN DESCRIPTION:
7
END DESCRIPTION:
#Sta/Elev= 12
   -14.4   69.34    -4.4   69.34      -3   70.34       0   70.34     1.5   69.64
     3.2   68.14     6.2   68.14     7.1   68.64     9.9   70.44    14.6   70.44
    17.2   68.44    27.2   68.44
#Mann= 3 , 0 , 0
   -14.4    .035       0       0    .035       0     9.9    .035       0
#XS Ineff= 2 , 0
               0      80     9.9              80
Permanent Ineff=
       F       F
#Block Obstruct= 2 , 0
                             9.9
Bank Sta=0,9.9
XS Rating Curve= 0
Exp/Cntr=.3,.1

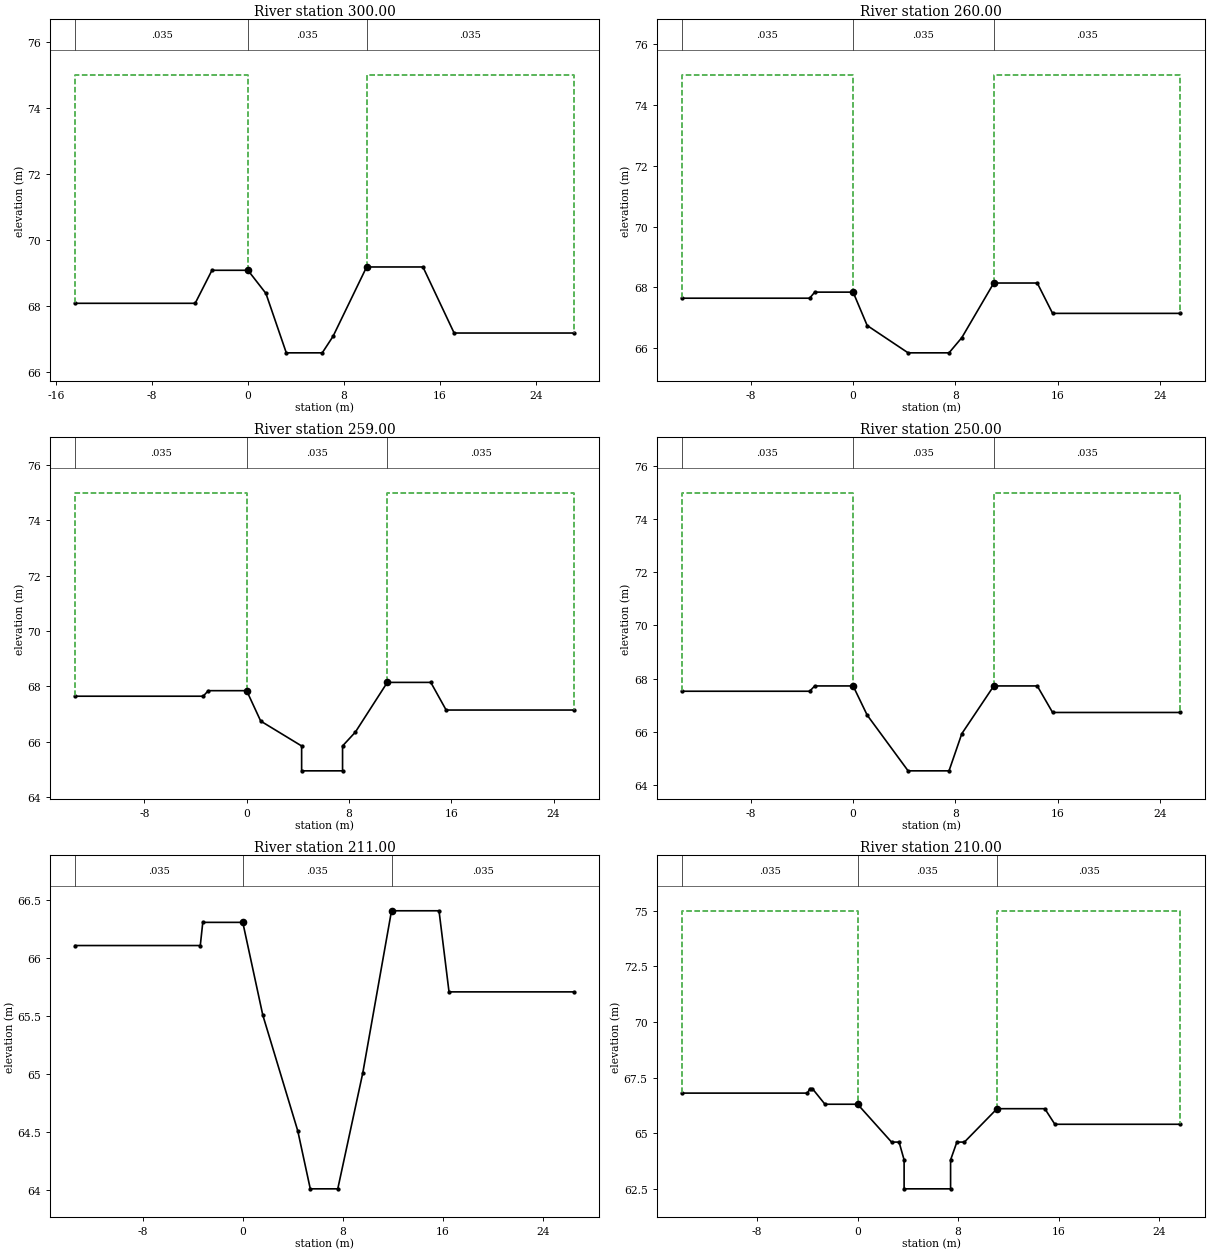
Type RM Length L Ch R = 1 ,300.00  ,40,40,40
BEGIN DESCRIPTION:
6
END DESCRIPTION:
#Sta/Elev= 12
   -14.4   68.08    -4.4   68.08      -3   69.08       0   69.08     1.5   68.38
     3.2   66.58     6.2   66.58     7.1   67.08     9.9   69.18    14.6   69.18
    17.2   67.18    27.2   67.18
#Mann= 3 , 0 , 0
   -14.4    .035       0       0    .035       0     9.9    .035       0
#XS Ineff= 2 , 0
               0      75     9.9              75
Permanent Ineff=
       F       F
#Block Obstruct= 2 , 0
                             9.9
Bank Sta=0,9.9
XS Rating Curve= 0
Exp/Cntr=.3,.1

Type RM Length L Ch R = 1 ,260.00  ,1,1,1
BEGIN DESCRIPTION:
5.01
END DESCRIPTION:
#Sta/Elev= 12
   -13.4   67.64    -3.4   67.64      -3   67.84       0   67.84     1.1   66.74
     4.3   65.84     7.5   65.84     8.5   66.34      11   68.14    14.4   68.14
    15.6   67.14    25.6   67.14
#Mann= 3 , 0 , 0
   -13.4    .035       0       0    .035       0      11    .035       0
#XS Ineff= 2 , 0
               0      75      11              75
Permanent Ineff=
       F       F
#Block Obstruct= 2 , 0
                              11
Bank Sta=0,11
XS Rating Curve= 0
Exp/Cntr=.3,.1

Type RM Length L Ch R = 1 ,259.00  ,9,9,9
BEGIN DESCRIPTION:
5.009
END DESCRIPTION:
#Sta/Elev= 14
   -13.4   67.64    -3.4   67.64      -3   67.84       0   67.84     1.1   66.74
     4.3   65.84     4.3   64.94     7.5   64.94     7.5   65.84     8.5   66.34
      11   68.14    14.4   68.14    15.6   67.14    25.6   67.14
#Mann= 3 , 0 , 0
   -13.4    .035       0       0    .035       0      11    .035       0
#XS Ineff= 2 , 0
               0      75      11              75
Permanent Ineff=
       F       F
#Block Obstruct= 2 , 0
                              11
Bank Sta=0,11
XS Rating Curve= 0
Exp/Cntr=.3,.1

Type RM Length L Ch R = 1 ,250.00  ,39,39,39
BEGIN DESCRIPTION:
5
END DESCRIPTION:
#Sta/Elev= 12
   -13.4   67.52    -3.4   67.52      -3   67.72       0   67.72     1.1   66.62
     4.3   64.52     7.5   64.52     8.5   65.92      11   67.72    14.4   67.72
    15.6   66.72    25.6   66.72
#Mann= 3 , 0 , 0
   -13.4    .035       0       0    .035       0      11    .035       0
#XS Ineff= 2 , 0
               0      75      11              75
Permanent Ineff=
       F       F
#Block Obstruct= 2 , 0
                              11
Bank Sta=0,11
XS Rating Curve= 0
Exp/Cntr=.3,.1

Type RM Length L Ch R = 1 ,211.00  ,1,1,1
BEGIN DESCRIPTION:
4.011
END DESCRIPTION:
#Sta/Elev= 13
   -13.4   66.11    -3.4   66.11    -3.2   66.31       0   66.31     1.6   65.51
     4.4   64.51     5.4   64.01     7.6   64.01     9.6   65.01    11.9   66.41
    15.7   66.41    16.5   65.71    26.5   65.71
#Mann= 3 , 0 , 0
   -13.4    .035       0       0    .035       0    11.9    .035       0
#XS Ineff= 2 , 0
               0      75    11.9              75
Permanent Ineff=
       F       F
#Block Obstruct= 2 , 0
                            11.9
Bank Sta=0,11.9
XS Rating Curve= 0
Exp/Cntr=.3,.1

Type RM Length L Ch R = 1 ,210.00  ,10,10,10
BEGIN DESCRIPTION:
4.01
END DESCRIPTION:
#Sta/Elev= 18
     -14   66.81      -4   66.81    -3.8   67.01    -3.6   67.01    -2.6   66.31
       0   66.31     2.7   64.61     3.3   64.61     3.7   63.81     3.7   62.51
     7.4   62.51     7.4   63.81     7.9   64.61     8.5   64.61    11.1   66.11
    14.9   66.11    15.7   65.41    25.7   65.41
#Mann= 3 , 0 , 0
     -14    .035       0       0    .035       0    11.1    .035       0
#XS Ineff= 2 , 0
               0      75    11.1              75
Permanent Ineff=
       F       F
#Block Obstruct= 2 , 0
                            11.1
Bank Sta=0,11.1
XS Rating Curve= 0
Exp/Cntr=.3,.1