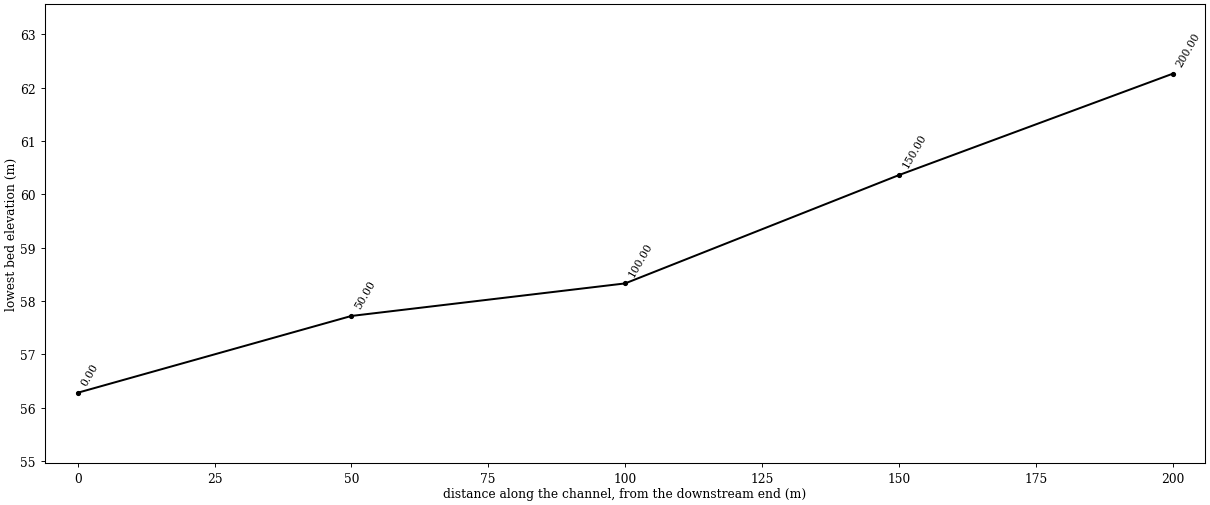
HEC-RAS study IM.prj: IM

--- IM.g01 (geometry) --- (continued)

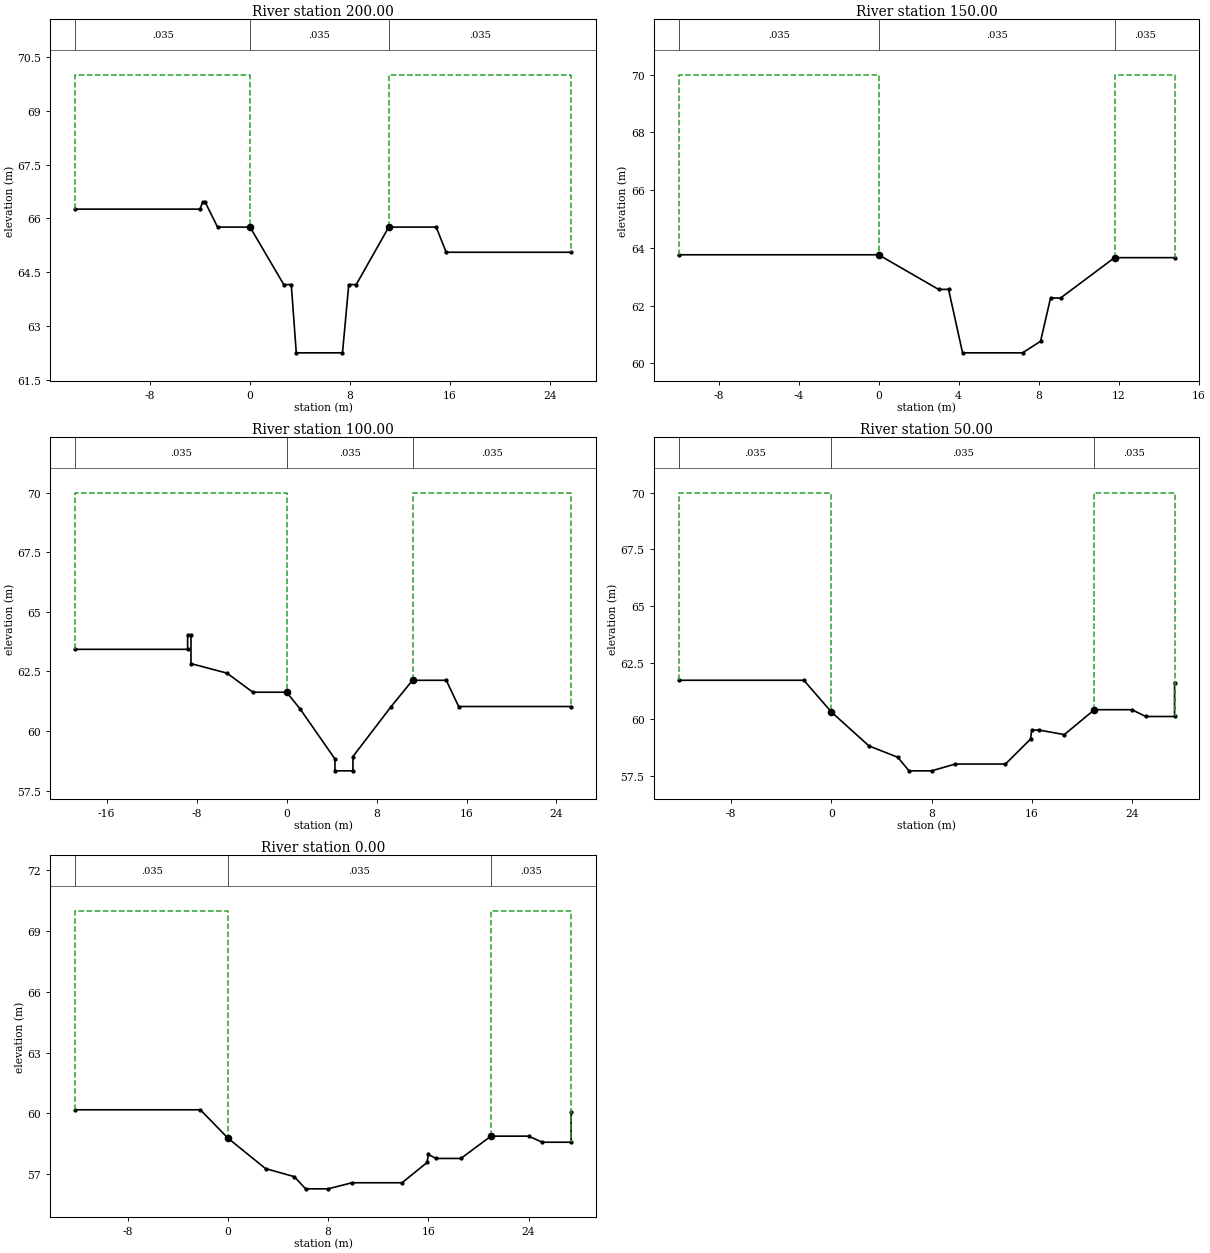
Type RM Length L Ch R = 1 ,200.00  ,50,50,50
BEGIN DESCRIPTION:
4
END DESCRIPTION:
#Sta/Elev= 16
     -14   66.26      -4   66.26    -3.8   66.46    -3.6   66.46    -2.6   65.76
       0   65.76     2.7   64.16     3.3   64.16     3.7   62.26     7.4   62.26
     7.9   64.16     8.5   64.16    11.1   65.76    14.9   65.76    15.7   65.06
    25.7   65.06
#Mann= 3 , 0 , 0
     -14    .035       0       0    .035       0    11.1    .035       0
#XS Ineff= 2 , 0
               0      70    11.1              70
Permanent Ineff=
       F       F
#Block Obstruct= 2 , 0
                            11.1
Bank Sta=0,11.1
XS Rating Curve= 0
Exp/Cntr=.3,.1

Type RM Length L Ch R = 1 ,150.00  ,50,50,50
BEGIN DESCRIPTION:
3
END DESCRIPTION:
#Sta/Elev= 11
     -10   63.76       0   63.76       3   62.56     3.5   62.56     4.2   60.36
     7.2   60.36     8.1   60.76     8.6   62.26     9.1   62.26    11.8   63.66
    14.8   63.66
#Mann= 3 , 0 , 0
     -10    .035       0       0    .035       0    11.8    .035       0
#XS Ineff= 2 , 0
               0      70    11.8              70
Permanent Ineff=
       F       F
#Block Obstruct= 2 , 0
                            11.8
Bank Sta=0,11.8
XS Rating Curve= 0
Exp/Cntr=.3,.1

Type RM Length L Ch R = 1 ,100.00  ,50,50,50
BEGIN DESCRIPTION:
2
END DESCRIPTION:
#Sta/Elev= 18
   -18.8   63.43    -8.8   63.43    -8.8   64.03    -8.5   64.03    -8.5   62.83
    -5.3   62.43      -3   61.63       0   61.63     1.2   60.93     4.3   58.83
     4.3   58.33     5.9   58.33     5.9   58.93     9.3   61.03    11.2   62.13
    14.2   62.13    15.3   61.03    25.3   61.03
#Mann= 3 , 0 , 0
   -18.8    .035       0       0    .035       0    11.2    .035       0
#XS Ineff= 2 , 0
               0      70    11.2              70
Permanent Ineff=
       F       F
#Block Obstruct= 2 , 0
                            11.2
Bank Sta=0,11.2
XS Rating Curve= 0
Exp/Cntr=.3,.1

Type RM Length L Ch R = 1 ,50.00   ,50,50,50
BEGIN DESCRIPTION:
1
END DESCRIPTION:
#Sta/Elev= 18
   -12.2   61.72    -2.2   61.72       0   60.32       3   58.82     5.3   58.32
     6.2   57.72       8   57.72     9.9   58.02    13.9   58.02    15.9   59.12
      16   59.52    16.6   59.52    18.6   59.32      21   60.42      24   60.42
    25.1   60.12    27.4   60.12    27.4   61.62
#Mann= 3 , 0 , 0
   -12.2    .035       0       0    .035       0      21    .035       0
#XS Ineff= 2 , 0
               0      70      21              70
Permanent Ineff=
       F       F
#Block Obstruct= 2 , 0
                              21
Bank Sta=0,21
XS Rating Curve= 0
Exp/Cntr=.3,.1

Type RM Length L Ch R = 1 ,0.00    ,0,0,0
BEGIN DESCRIPTION:
0
END DESCRIPTION:
#Sta/Elev= 18
   -12.2   60.18    -2.2   60.18       0   58.78       3   57.28     5.3   56.88
     6.2   56.28       8   56.28     9.9   56.58    13.9   56.58    15.9   57.58
      16   57.98    16.6   57.78    18.6   57.78      21   58.88      24   58.88
    25.1   58.58    27.4   58.58    27.4   60.08
#Mann= 3 , 0 , 0
   -12.2    .035       0       0    .035       0      21    .035       0
#XS Ineff= 2 , 0
               0      70      21              70
Permanent Ineff=
       F       F
#Block Obstruct= 2 , 0
                              21
Bank Sta=0,21
XS Rating Curve= 0
Exp/Cntr=.3,.1

Chan Stop Cuts=-1