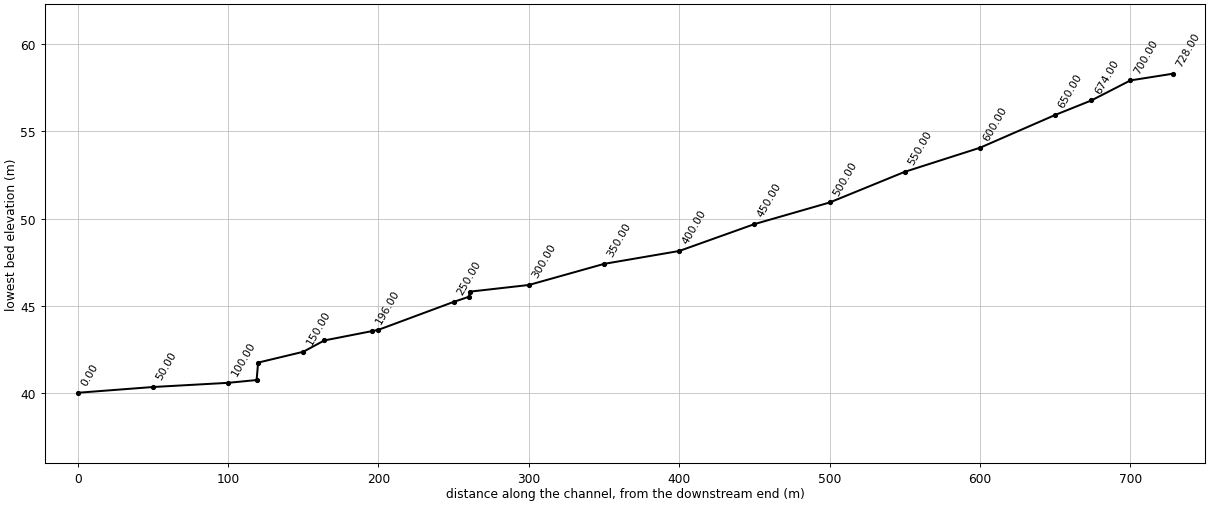
--- SI.prj (project) ---

Proj Title=SI
Current Plan=p01
Default Exp/Contr=.3,.1
SI Units
Geom File=g01
Flow File=f01
Plan File=p01
Y Axis Title=Elevation
X Axis Title(PF)=Main Channel Distance
X Axis Title(XS)=Station
BEGIN DESCRIPTION:
           BACK WATER COMPUTATION
      APPLICATION OF HEC-2 BY Samju Construction Engineering
      sidong-ch: 10,20,30,50,80 yr
END DESCRIPTION:
DSS Export Rating Curves= 0
DSS Export Rating Curve Sorted= 0
DSS Export Volume Flow Curves= 0
DXF OffsetX= 0
DXF OffsetY= 0
DXF ScaleX= 1
DXF ScaleY= 10

--- SI.p01 (plan) ---

Plan Title=Imported Plan 01
Version=Version 3.0.1  Mar 2001
Short Identifier=Imported Pla
Geom File=g01
Flow File=f01
Subcritical Flow
K Sum by GR= 0
Std Step Tol= 0.003
Critical Tol= 0.003
Num of Std Step Trials= 20
Max Error Tol= 0.1
Flow Tol Ratio= 0.001
Split Flow NTrial= 30
Split Flow Tol= 0.02
Split Flow Ratio= 0.02
Log Output Level= 0
Friction Slope Method= 1
Unsteady Friction Slope Method= 2
Parabolic Critical Depth
Global Vel Dist= 0 , 0 , 0
Global Log Level= 0
CheckData=True
Encroach Param=-1 ,0,0, 0
Computation Interval=1HOUR
Output Interval=1HOUR
Run HTab= 0
Run UNet= 0
Run PostProcess= 0
UNET Theta= 1
UNET ZTol= 0.02
UNET ZSATol= 0.1
UNET MxIter= 20
UNET MaxInSteps= 20
UNET DtIC= 0
UNET DtMin= 0
UNET MaxCRTS= 20
UNET WFStab= 2
UNET SFStab= 1
UNET WFX= 1
UNET SFX= 1
UNET Convert EG Bridges=-1
UNET Use Existing IB Tables=-1
Instantaneous Interval=1HOUR
Write IC File= 0
Write Velocity= 0
Write Detailed= 0

--- SI.f01 (steady flow) ---

Flow Title=Imported Flow 01
Version=Version 3.0.1  Mar 2001
Number of Profiles= 5
Profile Names=10YR,20YR,30YR,50YR,80YR
River Rch & RM=RIVER-1,Reach-1         ,728.00
    8.67    9.55   10.07   10.72   11.32
Boundary for River Rch & Prof#=RIVER-1,Reach-1         , 1
Up Type= 0
Dn Type= 3
Dn Slope=.07
Boundary for River Rch & Prof#=RIVER-1,Reach-1         , 2
Up Type= 0
Dn Type= 3
Dn Slope=.07
Boundary for River Rch & Prof#=RIVER-1,Reach-1         , 3
Up Type= 0
Dn Type= 3
Dn Slope=.07
Boundary for River Rch & Prof#=RIVER-1,Reach-1         , 4
Up Type= 0
Dn Type= 3
Dn Slope=.07
Boundary for River Rch & Prof#=RIVER-1,Reach-1         , 5
Up Type= 0
Dn Type= 3
Dn Slope=.07
DSS Import GetInterval= 0
DSS Import GetPeak= 0
DSS Import FillOption= 0

--- SI.g01 (geometry) ---

Geom Title=Imported Geom 01
Version=Version 3.0.1  Mar 2001

River Reach=RIVER-1         ,Reach-1
Reach XY= 2
              .5             .95              .5             .05

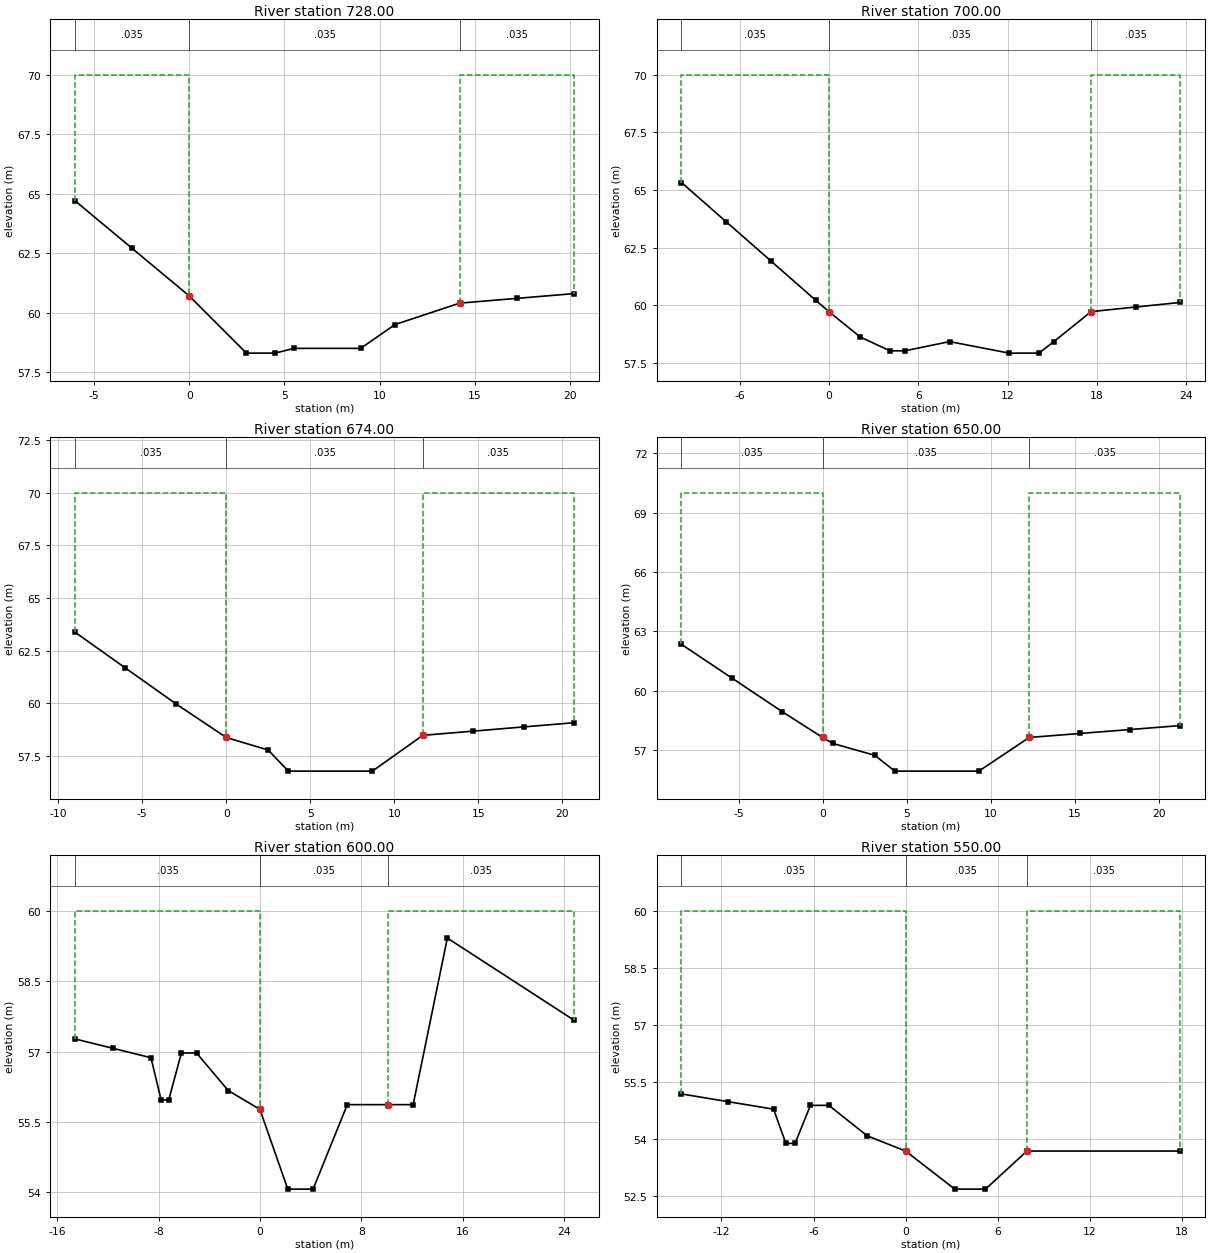
Type RM Length L Ch R = 1 ,728.00  ,28,28,28
BEGIN DESCRIPTION:
14.028
END DESCRIPTION:
#Sta/Elev= 11
      -6   64.71      -3   62.71       0   60.71       3   58.31     4.5   58.31
     5.5   58.51       9   58.51    10.8   59.51    14.2   60.41    17.2   60.61
    20.2   60.81
#Mann= 3 , 0 , 0
      -6    .035       0       0    .035       0    14.2    .035       0
#XS Ineff= 2 , 0
               0      70    14.2              70
Permanent Ineff=
       F       F
#Block Obstruct= 2 , 0
                            14.2
Bank Sta=0,14.2
XS Rating Curve= 0
Exp/Cntr=.3,.1

Type RM Length L Ch R = 1 ,700.00  ,26,26,26
BEGIN DESCRIPTION:
14
END DESCRIPTION:
#Sta/Elev= 15
    -9.9   65.33    -6.9   63.63    -3.9   61.93     -.9   60.23       0   59.73
     2.1   58.63     4.1   58.03     5.1   58.03     8.1   58.43    12.1   57.93
    14.1   57.93    15.1   58.43    17.6   59.73    20.6   59.93    23.6   60.13
#Mann= 3 , 0 , 0
    -9.9    .035       0       0    .035       0    17.6    .035       0
#XS Ineff= 2 , 0
               0      70    17.6              70
Permanent Ineff=
       F       F
#Block Obstruct= 2 , 0
                            17.6
Bank Sta=0,17.6
XS Rating Curve= 0
Exp/Cntr=.3,.1

Type RM Length L Ch R = 1 ,674.00  ,24,24,24
BEGIN DESCRIPTION:
13.024
END DESCRIPTION:
#Sta/Elev= 11
      -9   63.38      -6   61.68      -3   59.98       0   58.38     2.5   57.78
     3.7   56.78     8.7   56.78    11.7   58.48    14.7   58.68    17.7   58.88
    20.7   59.08
#Mann= 3 , 0 , 0
      -9    .035       0       0    .035       0    11.7    .035       0
#XS Ineff= 2 , 0
               0      70    11.7              70
Permanent Ineff=
       F       F
#Block Obstruct= 2 , 0
                            11.7
Bank Sta=0,11.7
XS Rating Curve= 0
Exp/Cntr=.3,.1

Type RM Length L Ch R = 1 ,650.00  ,50,50,50
BEGIN DESCRIPTION:
13
END DESCRIPTION:
#Sta/Elev= 12
    -8.4   62.35    -5.4   60.65    -2.4   58.95       0   57.65      .6   57.35
     3.1   56.75     4.3   55.95     9.3   55.95    12.3   57.65    15.3   57.85
    18.3   58.05    21.3   58.25
#Mann= 3 , 0 , 0
    -8.4    .035       0       0    .035       0    12.3    .035       0
#XS Ineff= 2 , 0
               0      70    12.3              70
Permanent Ineff=
       F       F
#Block Obstruct= 2 , 0
                            12.3
Bank Sta=0,12.3
XS Rating Curve= 0
Exp/Cntr=.3,.1

Type RM Length L Ch R = 1 ,600.00  ,50,50,50
BEGIN DESCRIPTION:
12
END DESCRIPTION:
#Sta/Elev= 16
   -14.6   57.27   -11.6   57.07    -8.6   56.87    -7.8   55.97    -7.2   55.97
    -6.2   56.97      -5   56.97    -2.5   56.17       0   55.77     2.2   54.07
     4.2   54.07     6.9   55.87    10.1   55.87    12.1   55.87    14.8   59.42
    24.8   57.67
#Mann= 3 , 0 , 0
   -14.6    .035       0       0    .035       0    10.1    .035       0
#XS Ineff= 2 , 0
               0      60    10.1              60
Permanent Ineff=
       F       F
#Block Obstruct= 2 , 0
                            10.1
Bank Sta=0,10.1
XS Rating Curve= 0
Exp/Cntr=.3,.1

Type RM Length L Ch R = 1 ,550.00  ,50,50,50
BEGIN DESCRIPTION:
11
END DESCRIPTION:
#Sta/Elev= 13
   -14.6   55.19   -11.6   54.99    -8.6   54.79    -7.8   53.89    -7.2   53.89
    -6.2   54.89      -5   54.89    -2.5   54.09       0   53.69     3.2   52.69
     5.2   52.69     7.9   53.69    17.9   53.69
#Mann= 3 , 0 , 0
   -14.6    .035       0       0    .035       0     7.9    .035       0
#XS Ineff= 2 , 0
               0      60     7.9              60
Permanent Ineff=
       F       F
#Block Obstruct= 2 , 0
                             7.9
Bank Sta=0,7.9
XS Rating Curve= 0
Exp/Cntr=.3,.1

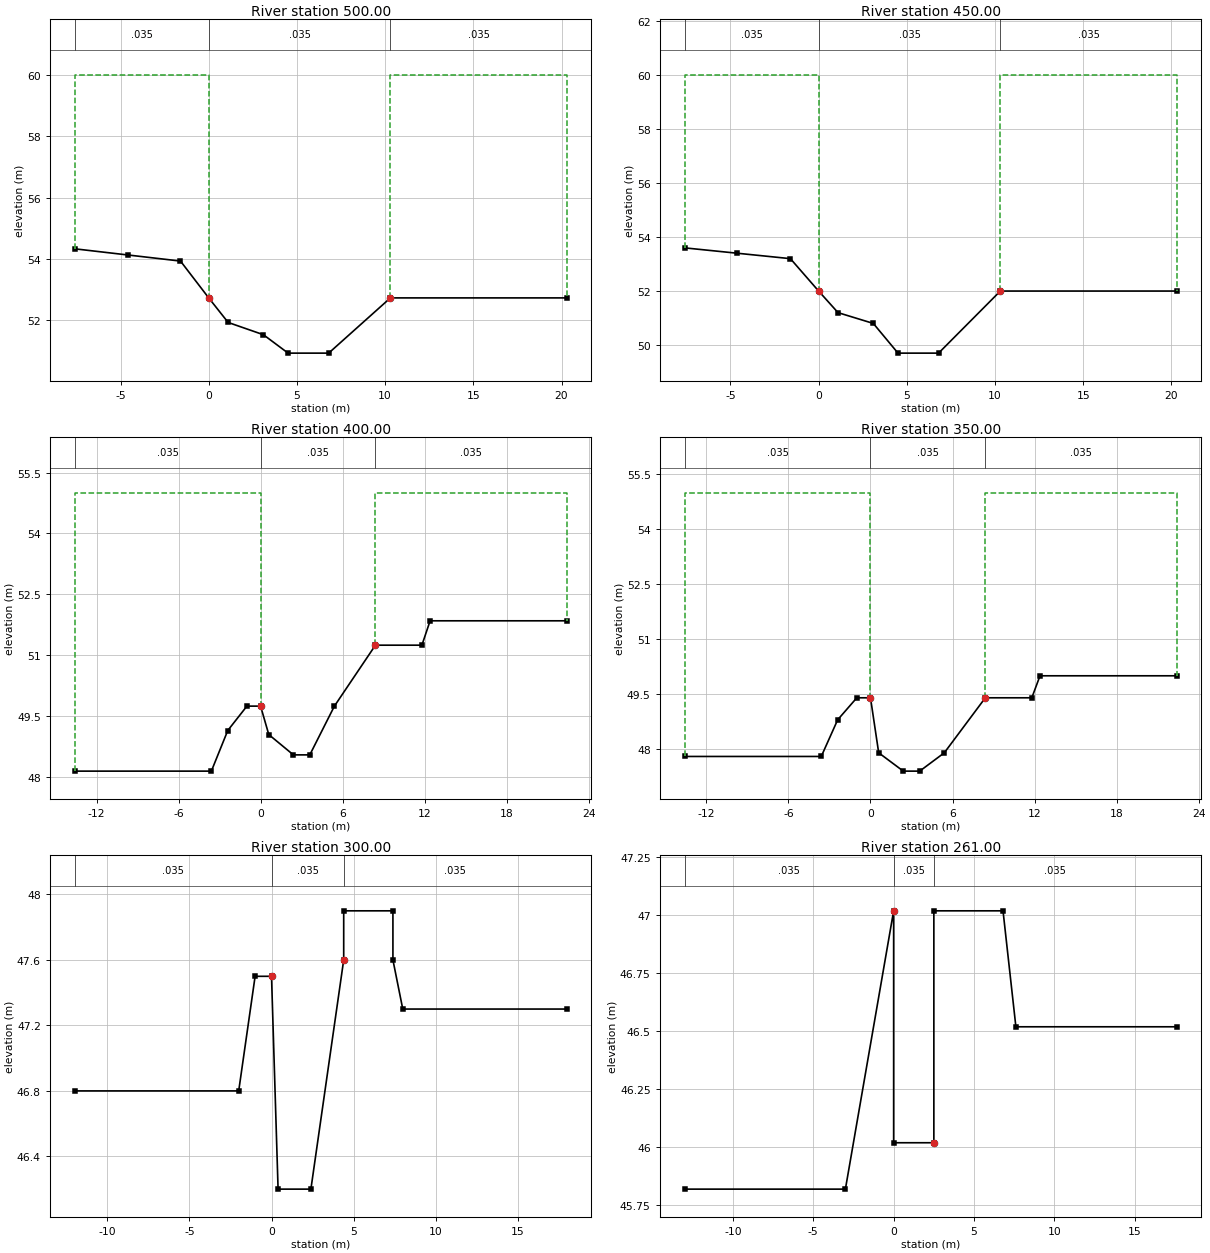
Type RM Length L Ch R = 1 ,500.00  ,50,50,50
BEGIN DESCRIPTION:
10
END DESCRIPTION:
#Sta/Elev= 10
    -7.6   54.33    -4.6   54.13    -1.6   53.93       0   52.73     1.1   51.93
     3.1   51.53     4.5   50.93     6.8   50.93    10.3   52.73    20.3   52.73
#Mann= 3 , 0 , 0
    -7.6    .035       0       0    .035       0    10.3    .035       0
#XS Ineff= 2 , 0
               0      60    10.3              60
Permanent Ineff=
       F       F
#Block Obstruct= 2 , 0
                            10.3
Bank Sta=0,10.3
XS Rating Curve= 0
Exp/Cntr=.3,.1

Type RM Length L Ch R = 1 ,450.00  ,50,50,50
BEGIN DESCRIPTION:
9
END DESCRIPTION:
#Sta/Elev= 10
    -7.6   53.59    -4.6   53.39    -1.6   53.19       0   51.99     1.1   51.19
     3.1   50.79     4.5   49.69     6.8   49.69    10.3   51.99    20.3   51.99
#Mann= 3 , 0 , 0
    -7.6    .035       0       0    .035       0    10.3    .035       0
#XS Ineff= 2 , 0
               0      60    10.3              60
Permanent Ineff=
       F       F
#Block Obstruct= 2 , 0
                            10.3
Bank Sta=0,10.3
XS Rating Curve= 0
Exp/Cntr=.3,.1

Type RM Length L Ch R = 1 ,400.00  ,50,50,50
BEGIN DESCRIPTION:
8
END DESCRIPTION:
#Sta/Elev= 13
   -13.6   48.15    -3.6   48.15    -2.4   49.15      -1   49.75       0   49.75
      .6   49.05     2.4   48.55     3.6   48.55     5.4   49.75     8.4   51.25
    11.8   51.25    12.4   51.85    22.4   51.85
#Mann= 3 , 0 , 0
   -13.6    .035       0       0    .035       0     8.4    .035       0
#XS Ineff= 2 , 0
               0      55     8.4              55
Permanent Ineff=
       F       F
#Block Obstruct= 2 , 0
                             8.4
Bank Sta=0,8.4
XS Rating Curve= 0
Exp/Cntr=.3,.1

Type RM Length L Ch R = 1 ,350.00  ,50,50,50
BEGIN DESCRIPTION:
7
END DESCRIPTION:
#Sta/Elev= 13
   -13.6   47.81    -3.6   47.81    -2.4   48.81      -1   49.41       0   49.41
      .6   47.91     2.4   47.41     3.6   47.41     5.4   47.91     8.4   49.41
    11.8   49.41    12.4   50.01    22.4   50.01
#Mann= 3 , 0 , 0
   -13.6    .035       0       0    .035       0     8.4    .035       0
#XS Ineff= 2 , 0
               0      55     8.4              55
Permanent Ineff=
       F       F
#Block Obstruct= 2 , 0
                             8.4
Bank Sta=0,8.4
XS Rating Curve= 0
Exp/Cntr=.3,.1

Type RM Length L Ch R = 1 ,300.00  ,39,39,39
BEGIN DESCRIPTION:
6
END DESCRIPTION:
#Sta/Elev= 12
     -12    46.8      -2    46.8      -1    47.5       0    47.5      .4    46.2
     2.4    46.2     4.4    47.6     4.4    47.9     7.4    47.9     7.4    47.6
       8    47.3      18    47.3
#Mann= 3 , 0 , 0
     -12    .035       0       0    .035       0     4.4    .035       0
#XS Ineff= 2 , 0
               0      55     4.4              55
Permanent Ineff=
       F       F
#Block Obstruct= 2 , 0
                             4.4
Bank Sta=0,4.4
XS Rating Curve= 0
Exp/Cntr=.3,.1

Type RM Length L Ch R = 1 ,261.00  ,1,1,1
BEGIN DESCRIPTION:
5.011
END DESCRIPTION:
#Sta/Elev= 9
     -13   45.82      -3   45.82       0   47.02       0   46.02     2.5   46.02
     2.5   47.02     6.8   47.02     7.6   46.52    17.6   46.52
#Mann= 3 , 0 , 0
     -13    .035       0       0    .035       0     2.5    .035       0
#XS Ineff= 2 , 0
               0      55     2.5              55
Permanent Ineff=
       F       F
#Block Obstruct= 2 , 0
                             2.5
Bank Sta=0,2.5
XS Rating Curve= 0
Exp/Cntr=.3,.1

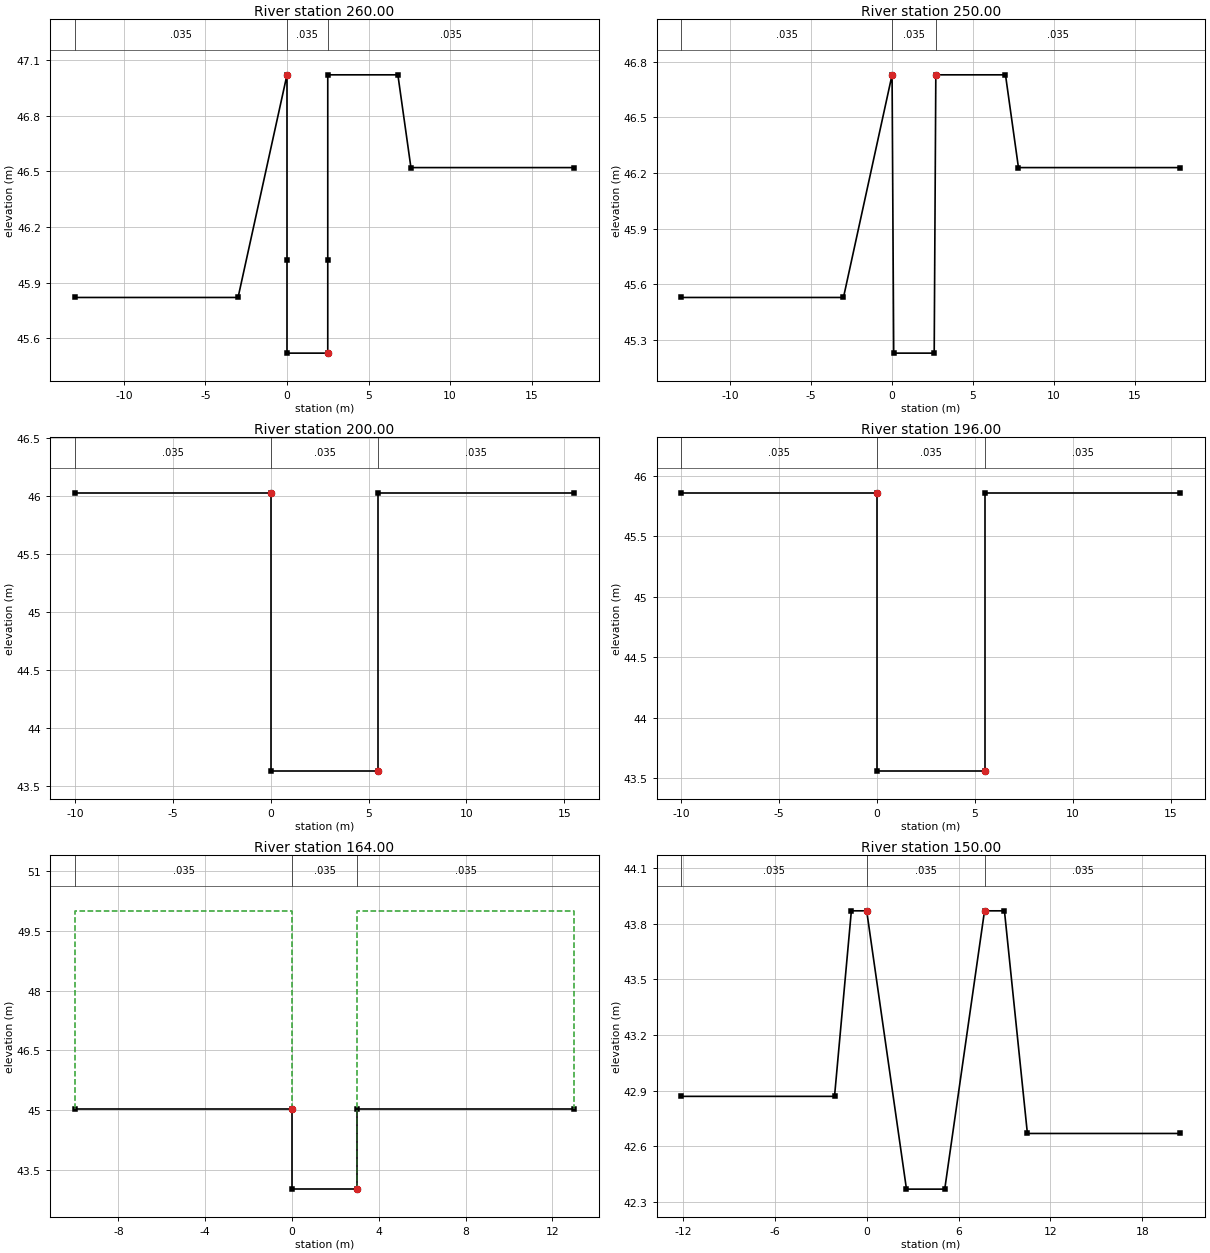
Type RM Length L Ch R = 1 ,260.00  ,10,10,10
BEGIN DESCRIPTION:
5.01
END DESCRIPTION:
#Sta/Elev= 11
     -13   45.82      -3   45.82       0   47.02       0   46.02       0   45.52
     2.5   45.52     2.5   46.02     2.5   47.02     6.8   47.02     7.6   46.52
    17.6   46.52
#Mann= 3 , 0 , 0
     -13    .035       0       0    .035       0     2.5    .035       0
#XS Ineff= 2 , 0
               0      55     2.5              55
Permanent Ineff=
       F       F
#Block Obstruct= 2 , 0
                             2.5
Bank Sta=0,2.5
XS Rating Curve= 0
Exp/Cntr=.3,.1

Type RM Length L Ch R = 1 ,250.00  ,50,50,50
BEGIN DESCRIPTION:
5
END DESCRIPTION:
#Sta/Elev= 9
     -13   45.53      -3   45.53       0   46.73      .1   45.23     2.6   45.23
     2.7   46.73       7   46.73     7.8   46.23    17.8   46.23
#Mann= 3 , 0 , 0
     -13    .035       0       0    .035       0     2.7    .035       0
#XS Ineff= 2 , 0
               0      55     2.7              55
Permanent Ineff=
       F       F
#Block Obstruct= 2 , 0
                             2.7
Bank Sta=0,2.7
XS Rating Curve= 0
Exp/Cntr=.3,.1

Type RM Length L Ch R = 1 ,200.00  ,4,4,4
BEGIN DESCRIPTION:
4
END DESCRIPTION:
#Sta/Elev= 6
     -10   46.03       0   46.03       0   43.63     5.5   43.63     5.5   46.03
    15.5   46.03
#Mann= 3 , 0 , 0
     -10    .035       0       0    .035       0     5.5    .035       0
#XS Ineff= 2 , 0
               0      55     5.5              55
Permanent Ineff=
       F       F
#Block Obstruct= 2 , 0
                             5.5
Bank Sta=0,5.5
XS Rating Curve= 0
Exp/Cntr=.3,.1

Type RM Length L Ch R = 1 ,196.00  ,32,32,32
BEGIN DESCRIPTION:
3.046
END DESCRIPTION:
#Sta/Elev= 6
     -10   45.86       0   45.86       0   43.56     5.5   43.56     5.5   45.86
    15.5   45.86
#Mann= 3 , 0 , 0
     -10    .035       0       0    .035       0     5.5    .035       0
#XS Ineff= 2 , 0
               0      55     5.5              55
Permanent Ineff=
       F       F
#Block Obstruct= 2 , 0
                             5.5
Bank Sta=0,5.5
XS Rating Curve= 0
Exp/Cntr=.3,.1

Type RM Length L Ch R = 1 ,164.00  ,14,14,14
BEGIN DESCRIPTION:
3.014
END DESCRIPTION:
#Sta/Elev= 6
     -10   45.02       0   45.02       0   43.02       3   43.02       3   45.02
      13   45.02
#Mann= 3 , 0 , 0
     -10    .035       0       0    .035       0       3    .035       0
#XS Ineff= 2 , 0
               0      50       3              50
Permanent Ineff=
       F       F
#Block Obstruct= 2 , 0
                               3
Bank Sta=0,3
XS Rating Curve= 0
Exp/Cntr=.3,.1

Type RM Length L Ch R = 1 ,150.00  ,30,30,30
BEGIN DESCRIPTION:
3
END DESCRIPTION:
#Sta/Elev= 10
   -12.1   42.87    -2.1   42.87      -1   43.87       0   43.87     2.6   42.37
     5.1   42.37     7.7   43.87       9   43.87    10.5   42.67    20.5   42.67
#Mann= 3 , 0 , 0
   -12.1    .035       0       0    .035       0     7.7    .035       0
#XS Ineff= 2 , 0
               0      50     7.7              50
Permanent Ineff=
       F       F
#Block Obstruct= 2 , 0
                             7.7
Bank Sta=0,7.7
XS Rating Curve= 0
Exp/Cntr=.3,.1

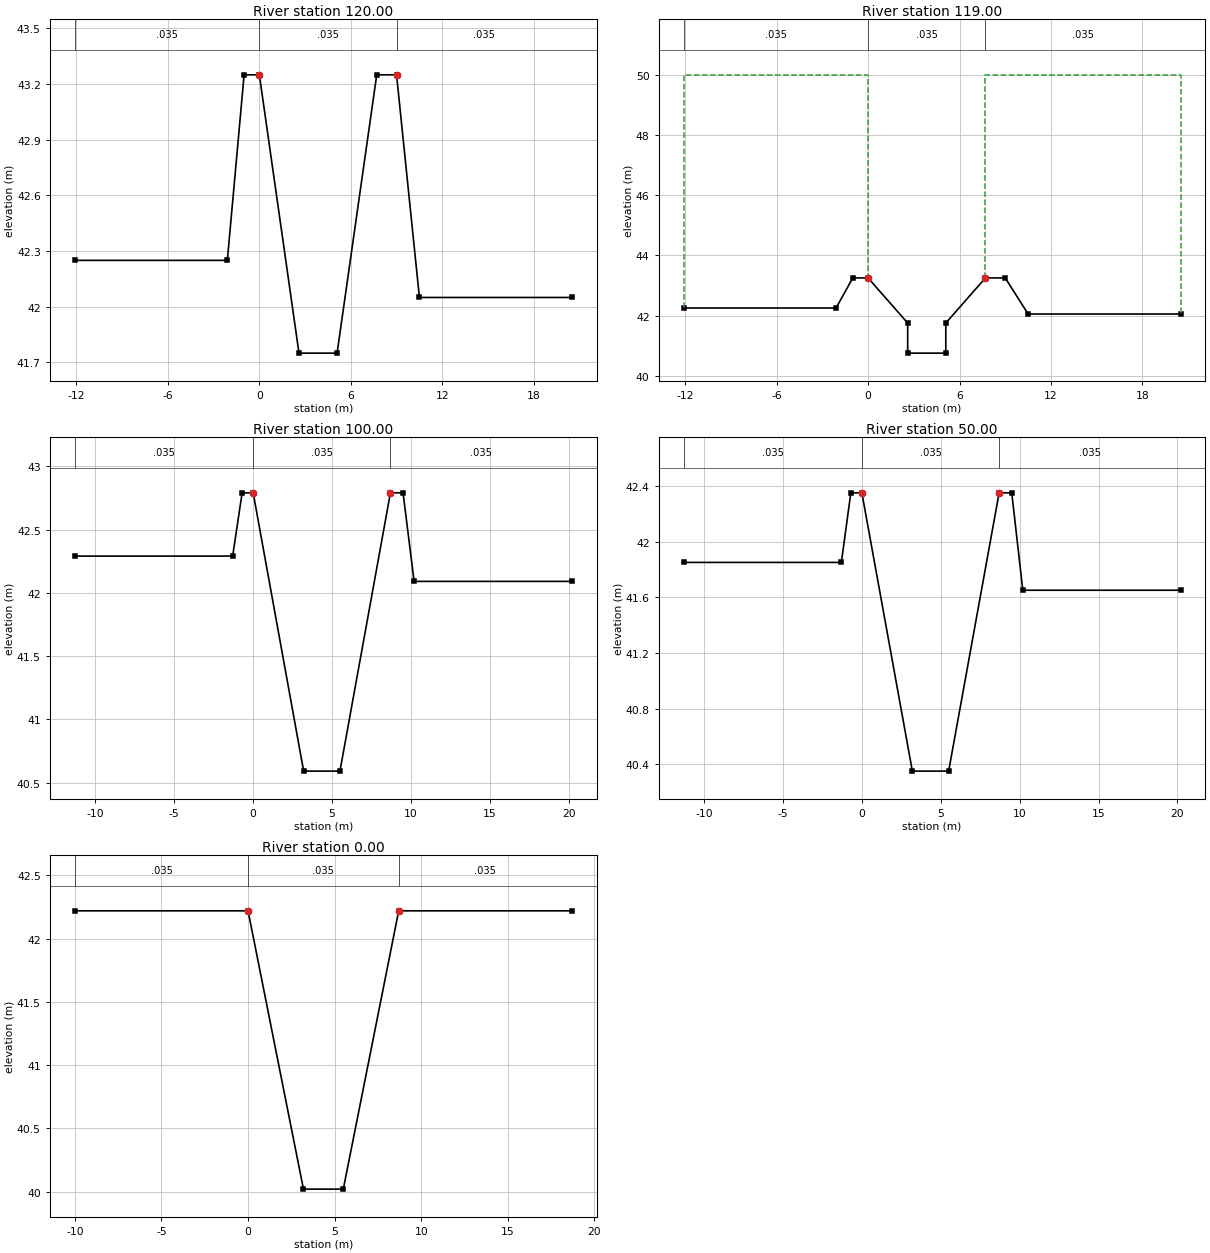
Type RM Length L Ch R = 1 ,120.00  ,1,1,1
BEGIN DESCRIPTION:
2.02
END DESCRIPTION:
#Sta/Elev= 10
   -12.1   42.25    -2.1   42.25      -1   43.25       0   43.25     2.6   41.75
     5.1   41.75     7.7   43.25       9   43.25    10.5   42.05    20.5   42.05
#Mann= 3 , 0 , 0
   -12.1    .035       0       0    .035       0       9    .035       0
#XS Ineff= 2 , 0
               0      50       9              50
Permanent Ineff=
       F       F
#Block Obstruct= 2 , 0
                               9
Bank Sta=0,9
XS Rating Curve= 0
Exp/Cntr=.3,.1

Type RM Length L Ch R = 1 ,119.00  ,19,19,19
BEGIN DESCRIPTION:
2.019
END DESCRIPTION:
#Sta/Elev= 12
   -12.1   42.25    -2.1   42.25      -1   43.25       0   43.25     2.6   41.75
     2.6   40.75     5.1   40.75     5.1   41.75     7.7   43.25       9   43.25
    10.5   42.05    20.5   42.05
#Mann= 3 , 0 , 0
   -12.1    .035       0       0    .035       0     7.7    .035       0
#XS Ineff= 2 , 0
               0      50     7.7              50
Permanent Ineff=
       F       F
#Block Obstruct= 2 , 0
                             7.7
Bank Sta=0,7.7
XS Rating Curve= 0
Exp/Cntr=.3,.1

Type RM Length L Ch R = 1 ,100.00  ,50,50,50
BEGIN DESCRIPTION:
2
END DESCRIPTION:
#Sta/Elev= 10
   -11.3   42.29    -1.3   42.29     -.7   42.79       0   42.79     3.2   40.59
     5.5   40.59     8.7   42.79     9.5   42.79    10.2   42.09    20.2   42.09
#Mann= 3 , 0 , 0
   -11.3    .035       0       0    .035       0     8.7    .035       0
#XS Ineff= 2 , 0
               0      50     8.7              50
Permanent Ineff=
       F       F
#Block Obstruct= 2 , 0
                             8.7
Bank Sta=0,8.7
XS Rating Curve= 0
Exp/Cntr=.3,.1

Type RM Length L Ch R = 1 ,50.00   ,50,50,50
BEGIN DESCRIPTION:
1
END DESCRIPTION:
#Sta/Elev= 10
   -11.3   41.85    -1.3   41.85     -.7   42.35       0   42.35     3.2   40.35
     5.5   40.35     8.7   42.35     9.5   42.35    10.2   41.65    20.2   41.65
#Mann= 3 , 0 , 0
   -11.3    .035       0       0    .035       0     8.7    .035       0
#XS Ineff= 2 , 0
               0      50     8.7              50
Permanent Ineff=
       F       F
#Block Obstruct= 2 , 0
                             8.7
Bank Sta=0,8.7
XS Rating Curve= 0
Exp/Cntr=.3,.1

Type RM Length L Ch R = 1 ,0.00    ,0,0,0
BEGIN DESCRIPTION:
0
END DESCRIPTION:
#Sta/Elev= 6
     -10   42.22       0   42.22     3.2   40.02     5.5   40.02     8.7   42.22
    18.7   42.22
#Mann= 3 , 0 , 0
     -10    .035       0       0    .035       0     8.7    .035       0
#XS Ineff= 2 , 0
               0      50     8.7              50
Permanent Ineff=
       F       F
#Block Obstruct= 2 , 0
                             8.7
Bank Sta=0,8.7
XS Rating Curve= 0
Exp/Cntr=.3,.1

Chan Stop Cuts=-1