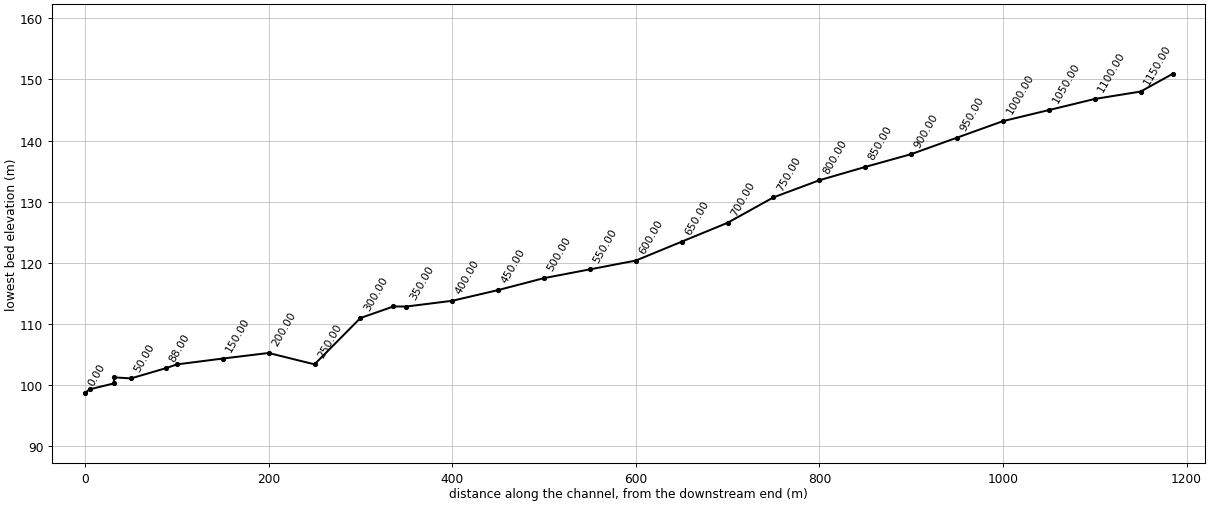
--- BMC.prj (project) ---

Proj Title=BYUNG
Current Plan=p01
Default Exp/Contr=.3,.1
SI Units
Geom File=g01
Flow File=f01
Plan File=p01
Y Axis Title=Elevation
X Axis Title(PF)=Main Channel Distance
X Axis Title(XS)=Station
BEGIN DESCRIPTION:
           BACK WATER COMPUTATION
      APPLICATION OF HEC-2 BY Samju Construction Engineering
      bungmok-ch: 10,20,30,50,80 yr
END DESCRIPTION:
DSS Export Rating Curves= 0
DSS Export Rating Curve Sorted= 0
DSS Export Volume Flow Curves= 0
DXF OffsetX= 0
DXF OffsetY= 0
DXF ScaleX= 1
DXF ScaleY= 10

--- BMC.p01 (plan) ---

Plan Title=Imported Plan 01
Version=Version 3.0.1  Mar 2001
Short Identifier=Imported Pla
Geom File=g01
Flow File=f01
Subcritical Flow
K Sum by GR= 0
Std Step Tol= 0.003
Critical Tol= 0.003
Num of Std Step Trials= 20
Max Error Tol= 0.1
Flow Tol Ratio= 0.001
Split Flow NTrial= 30
Split Flow Tol= 0.02
Split Flow Ratio= 0.02
Log Output Level= 0
Friction Slope Method= 1
Unsteady Friction Slope Method= 2
Parabolic Critical Depth
Global Vel Dist= 0 , 0 , 0
Global Log Level= 0
CheckData=True
Encroach Param=-1 ,0,0, 0
Computation Interval=1HOUR
Output Interval=1HOUR
Run HTab= 0
Run UNet= 0
Run PostProcess= 0
UNET Theta= 1
UNET ZTol= 0.02
UNET ZSATol= 0.1
UNET MxIter= 20
UNET MaxInSteps= 20
UNET DtIC= 0
UNET DtMin= 0
UNET MaxCRTS= 20
UNET WFStab= 2
UNET SFStab= 1
UNET WFX= 1
UNET SFX= 1
UNET Convert EG Bridges=-1
UNET Use Existing IB Tables=-1
Instantaneous Interval=1HOUR
Write IC File= 0
Write Velocity= 0
Write Detailed= 0

--- BMC.f01 (steady flow) ---

Flow Title=Imported Flow 01
Version=Version 3.0.1  Mar 2001
Number of Profiles= 5
Profile Names=10YR,20YR,30YR,50YR,80YR
River Rch & RM=RIVER-1,Reach-1         ,1185.00
   25.77   28.41   29.95   31.89   33.68
Boundary for River Rch & Prof#=RIVER-1,Reach-1         , 1
Up Type= 0
Dn Type= 3
Dn Slope=.05
Boundary for River Rch & Prof#=RIVER-1,Reach-1         , 2
Up Type= 0
Dn Type= 3
Dn Slope=.05
Boundary for River Rch & Prof#=RIVER-1,Reach-1         , 3
Up Type= 0
Dn Type= 3
Dn Slope=.05
Boundary for River Rch & Prof#=RIVER-1,Reach-1         , 4
Up Type= 0
Dn Type= 3
Dn Slope=.05
Boundary for River Rch & Prof#=RIVER-1,Reach-1         , 5
Up Type= 0
Dn Type= 3
Dn Slope=.05
DSS Import GetInterval= 0
DSS Import GetPeak= 0
DSS Import FillOption= 0

--- BMC.g01 (geometry) ---

Geom Title=Imported Geom 01
Version=Version 3.0.1  Mar 2001

River Reach=RIVER-1         ,Reach-1
Reach XY= 2
              .5             .95              .5             .05

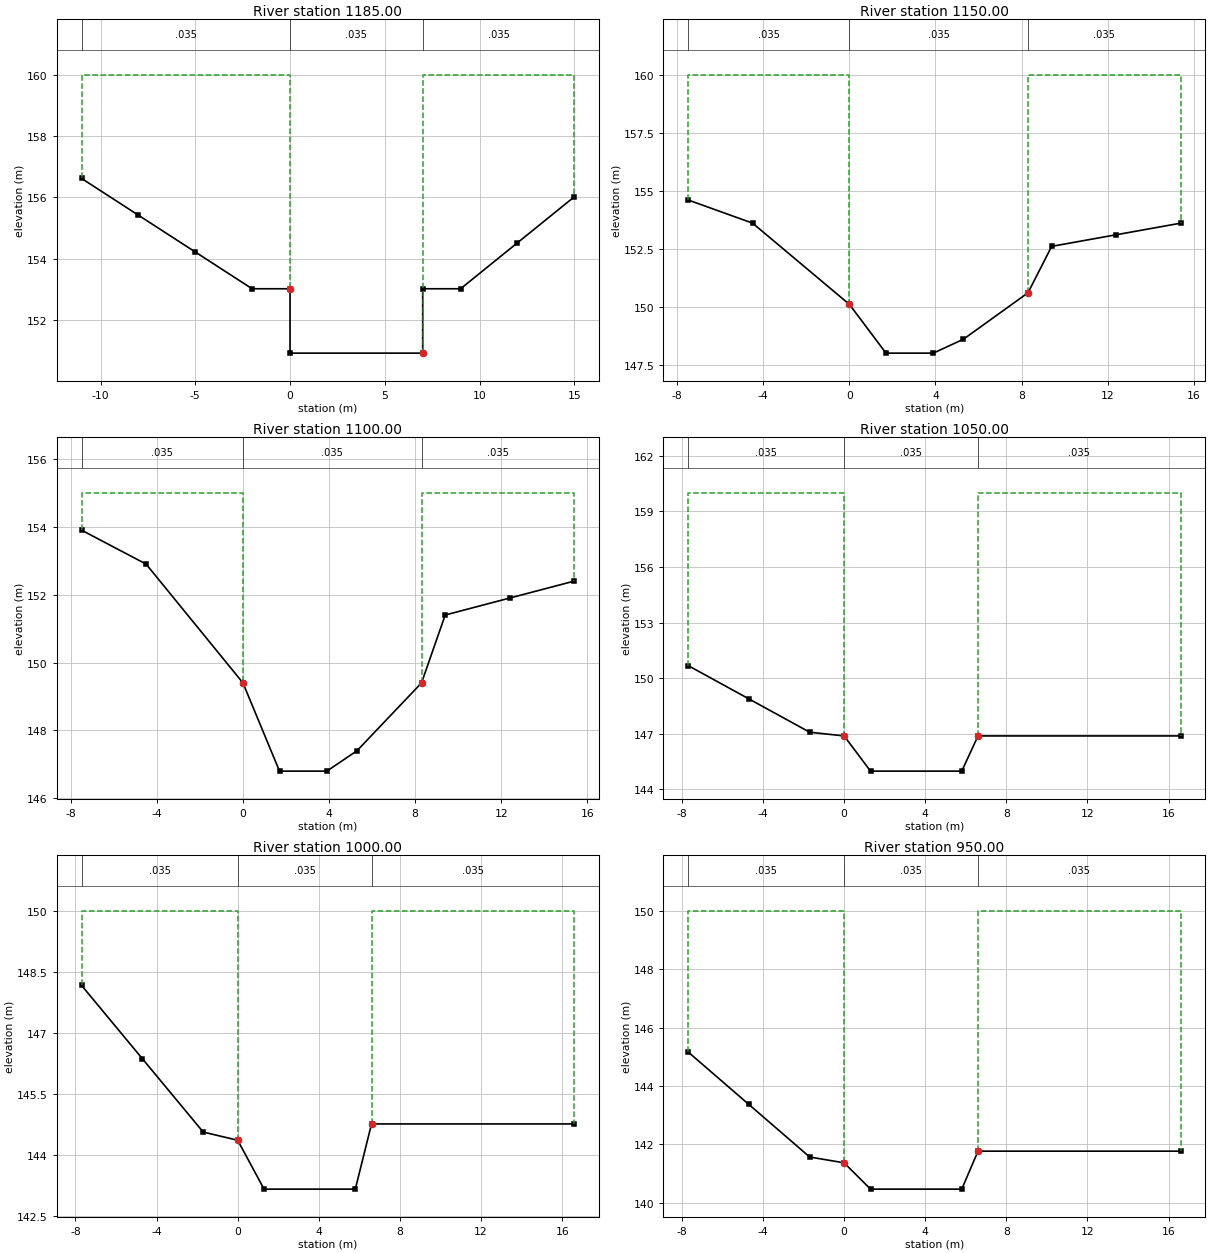
Type RM Length L Ch R = 1 ,1185.00 ,35,35,35
BEGIN DESCRIPTION:
22.044
END DESCRIPTION:
#Sta/Elev= 11
     -11  156.62      -8  155.42      -5  154.22      -2  153.02       0  153.02
       0  150.92       7  150.92       7  153.02       9  153.02      12  154.52
      15  156.02
#Mann= 3 , 0 , 0
     -11    .035       0       0    .035       0       7    .035       0
#XS Ineff= 2 , 0
               0     160       7             160
Permanent Ineff=
       F       F
#Block Obstruct= 2 , 0
                               7
Bank Sta=0,7
XS Rating Curve= 0
Exp/Cntr=.3,.1

Type RM Length L Ch R = 1 ,1150.00 ,50,50,50
BEGIN DESCRIPTION:
22.009
END DESCRIPTION:
#Sta/Elev= 10
    -7.5  154.61    -4.5  153.61       0  150.11     1.7  148.01     3.9  148.01
     5.3  148.61     8.3  150.61     9.4  152.61    12.4  153.11    15.4  153.61
#Mann= 3 , 0 , 0
    -7.5    .035       0       0    .035       0     8.3    .035       0
#XS Ineff= 2 , 0
               0     160     8.3             160
Permanent Ineff=
       F       F
#Block Obstruct= 2 , 0
                             8.3
Bank Sta=0,8.3
XS Rating Curve= 0
Exp/Cntr=.3,.1

Type RM Length L Ch R = 1 ,1100.00 ,50,50,50
BEGIN DESCRIPTION:
22
END DESCRIPTION:
#Sta/Elev= 10
    -7.5   153.9    -4.5   152.9       0   149.4     1.7   146.8     3.9   146.8
     5.3   147.4     8.3   149.4     9.4   151.4    12.4   151.9    15.4   152.4
#Mann= 3 , 0 , 0
    -7.5    .035       0       0    .035       0     8.3    .035       0
#XS Ineff= 2 , 0
               0     155     8.3             155
Permanent Ineff=
       F       F
#Block Obstruct= 2 , 0
                             8.3
Bank Sta=0,8.3
XS Rating Curve= 0
Exp/Cntr=.3,.1

Type RM Length L Ch R = 1 ,1050.00 ,50,50,50
BEGIN DESCRIPTION:
21
END DESCRIPTION:
#Sta/Elev= 8
    -7.7  150.68    -4.7  148.88    -1.7  147.08       0  146.88     1.3  144.98
     5.8  144.98     6.6  146.88    16.6  146.88
#Mann= 3 , 0 , 0
    -7.7    .035       0       0    .035       0     6.6    .035       0
#XS Ineff= 2 , 0
               0     160     6.6             160
Permanent Ineff=
       F       F
#Block Obstruct= 2 , 0
                             6.6
Bank Sta=0,6.6
XS Rating Curve= 0
Exp/Cntr=.3,.1

Type RM Length L Ch R = 1 ,1000.00 ,50,50,50
BEGIN DESCRIPTION:
20
END DESCRIPTION:
#Sta/Elev= 8
    -7.7  148.17    -4.7  146.37    -1.7  144.57       0  144.37     1.3  143.17
     5.8  143.17     6.6  144.77    16.6  144.77
#Mann= 3 , 0 , 0
    -7.7    .035       0       0    .035       0     6.6    .035       0
#XS Ineff= 2 , 0
               0     150     6.6             150
Permanent Ineff=
       F       F
#Block Obstruct= 2 , 0
                             6.6
Bank Sta=0,6.6
XS Rating Curve= 0
Exp/Cntr=.3,.1

Type RM Length L Ch R = 1 ,950.00  ,50,50,50
BEGIN DESCRIPTION:
19
END DESCRIPTION:
#Sta/Elev= 8
    -7.7  145.17    -4.7  143.37    -1.7  141.57       0  141.37     1.3  140.47
     5.8  140.47     6.6  141.77    16.6  141.77
#Mann= 3 , 0 , 0
    -7.7    .035       0       0    .035       0     6.6    .035       0
#XS Ineff= 2 , 0
               0     150     6.6             150
Permanent Ineff=
       F       F
#Block Obstruct= 2 , 0
                             6.6
Bank Sta=0,6.6
XS Rating Curve= 0
Exp/Cntr=.3,.1

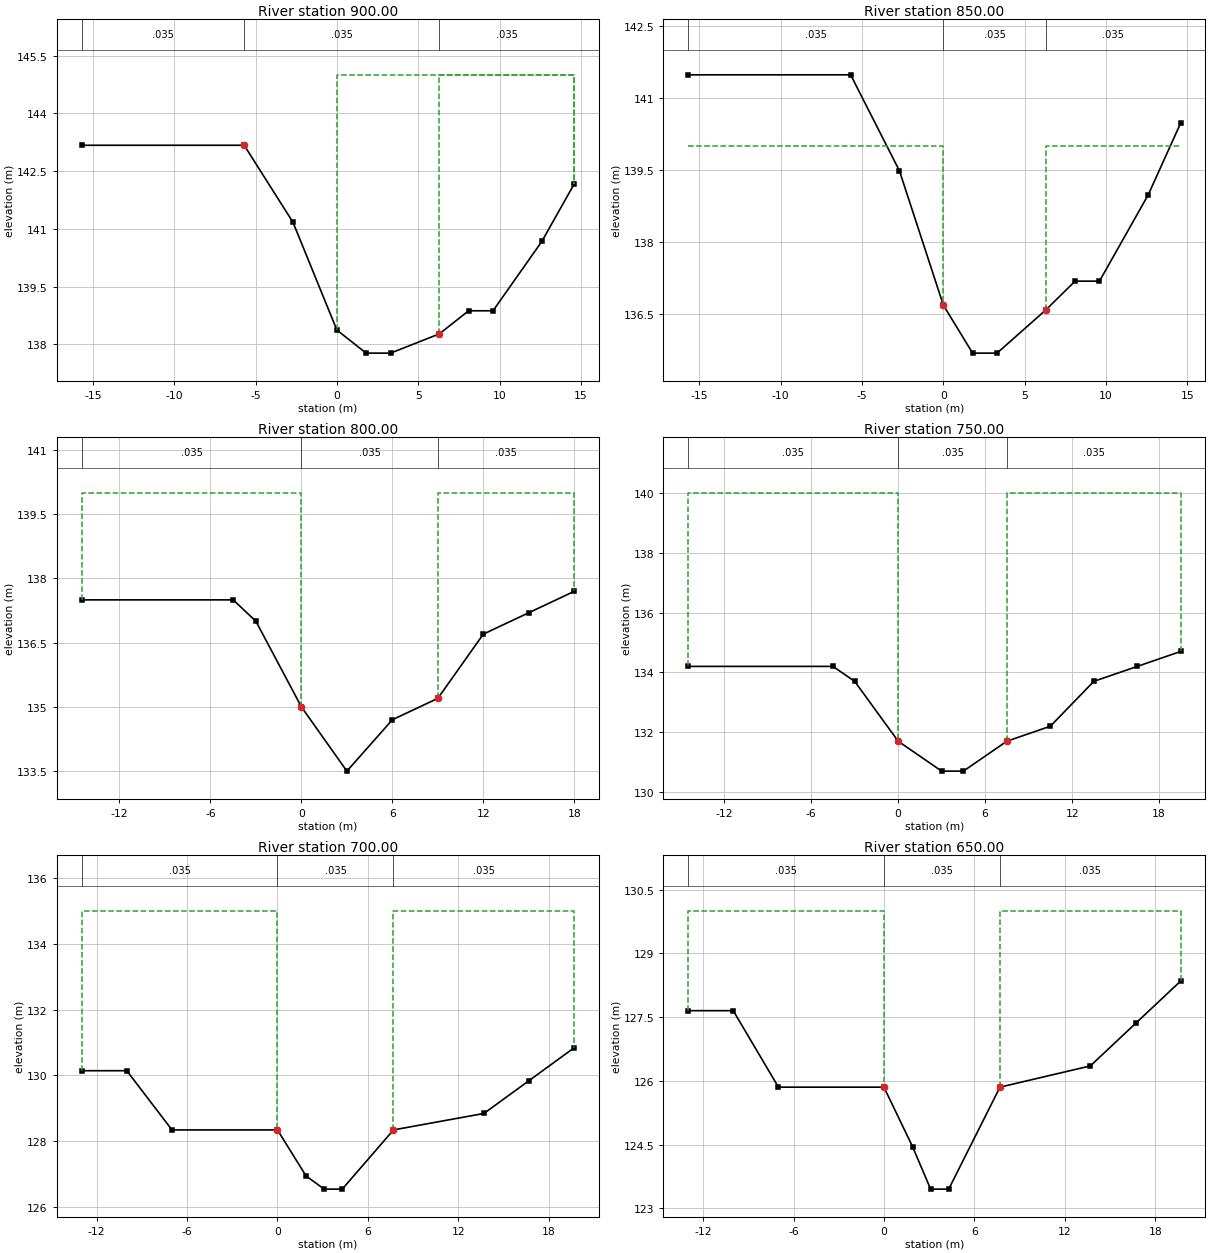
Type RM Length L Ch R = 1 ,900.00  ,50,50,50
BEGIN DESCRIPTION:
18
END DESCRIPTION:
#Sta/Elev= 11
   -15.7  143.17    -5.7  143.17    -2.7  141.17       0  138.37     1.8  137.77
     3.3  137.77     6.3  138.27     8.1  138.87     9.6  138.87    12.6  140.67
    14.6  142.17
#Mann= 3 , 0 , 0
   -15.7    .035       0    -5.7    .035       0     6.3    .035       0
#XS Ineff= 2 , 0
       0    -5.7     145     6.3       0     145
Permanent Ineff=
       F       F
#Block Obstruct= 2 , 0
                             6.3
Bank Sta=-5.7,6.3
XS Rating Curve= 0
Exp/Cntr=.3,.1

Type RM Length L Ch R = 1 ,850.00  ,50,50,50
BEGIN DESCRIPTION:
17
END DESCRIPTION:
#Sta/Elev= 11
   -15.7  141.48    -5.7  141.48    -2.7  139.48       0  136.68     1.8  135.68
     3.3  135.68     6.3  136.58     8.1  137.18     9.6  137.18    12.6  138.98
    14.6  140.48
#Mann= 3 , 0 , 0
   -15.7    .035       0       0    .035       0     6.3    .035       0
#XS Ineff= 2 , 0
               0     140     6.3             140
Permanent Ineff=
       F       F
#Block Obstruct= 2 , 0
                             6.3
Bank Sta=0,6.3
XS Rating Curve= 0
Exp/Cntr=.3,.1

Type RM Length L Ch R = 1 ,800.00  ,50,50,50
BEGIN DESCRIPTION:
16
END DESCRIPTION:
#Sta/Elev= 10
   -14.5   137.5    -4.5   137.5      -3     137       0     135       3   133.5
       6   134.7       9   135.2      12   136.7      15   137.2      18   137.7
#Mann= 3 , 0 , 0
   -14.5    .035       0       0    .035       0       9    .035       0
#XS Ineff= 2 , 0
               0     140       9             140
Permanent Ineff=
       F       F
#Block Obstruct= 2 , 0
                               9
Bank Sta=0,9
XS Rating Curve= 0
Exp/Cntr=.3,.1

Type RM Length L Ch R = 1 ,750.00  ,50,50,50
BEGIN DESCRIPTION:
15
END DESCRIPTION:
#Sta/Elev= 11
   -14.5   134.2    -4.5   134.2      -3   133.7       0   131.7       3   130.7
     4.5   130.7     7.5   131.7    10.5   132.2    13.5   133.7    16.5   134.2
    19.5   134.7
#Mann= 3 , 0 , 0
   -14.5    .035       0       0    .035       0     7.5    .035       0
#XS Ineff= 2 , 0
               0     140     7.5             140
Permanent Ineff=
       F       F
#Block Obstruct= 2 , 0
                             7.5
Bank Sta=0,7.5
XS Rating Curve= 0
Exp/Cntr=.3,.1

Type RM Length L Ch R = 1 ,700.00  ,50,50,50
BEGIN DESCRIPTION:
14
END DESCRIPTION:
#Sta/Elev= 11
     -13  130.14     -10  130.14      -7  128.34       0  128.34     1.9  126.94
     3.1  126.54     4.3  126.54     7.7  128.34    13.7  128.84    16.7  129.84
    19.7  130.84
#Mann= 3 , 0 , 0
     -13    .035       0       0    .035       0     7.7    .035       0
#XS Ineff= 2 , 0
               0     135     7.7             135
Permanent Ineff=
       F       F
#Block Obstruct= 2 , 0
                             7.7
Bank Sta=0,7.7
XS Rating Curve= 0
Exp/Cntr=.3,.1

Type RM Length L Ch R = 1 ,650.00  ,50,50,50
BEGIN DESCRIPTION:
13
END DESCRIPTION:
#Sta/Elev= 11
     -13  127.65     -10  127.65      -7  125.85       0  125.85     1.9  124.45
     3.1  123.45     4.3  123.45     7.7  125.85    13.7  126.35    16.7  127.35
    19.7  128.35
#Mann= 3 , 0 , 0
     -13    .035       0       0    .035       0     7.7    .035       0
#XS Ineff= 2 , 0
               0     130     7.7             130
Permanent Ineff=
       F       F
#Block Obstruct= 2 , 0
                             7.7
Bank Sta=0,7.7
XS Rating Curve= 0
Exp/Cntr=.3,.1

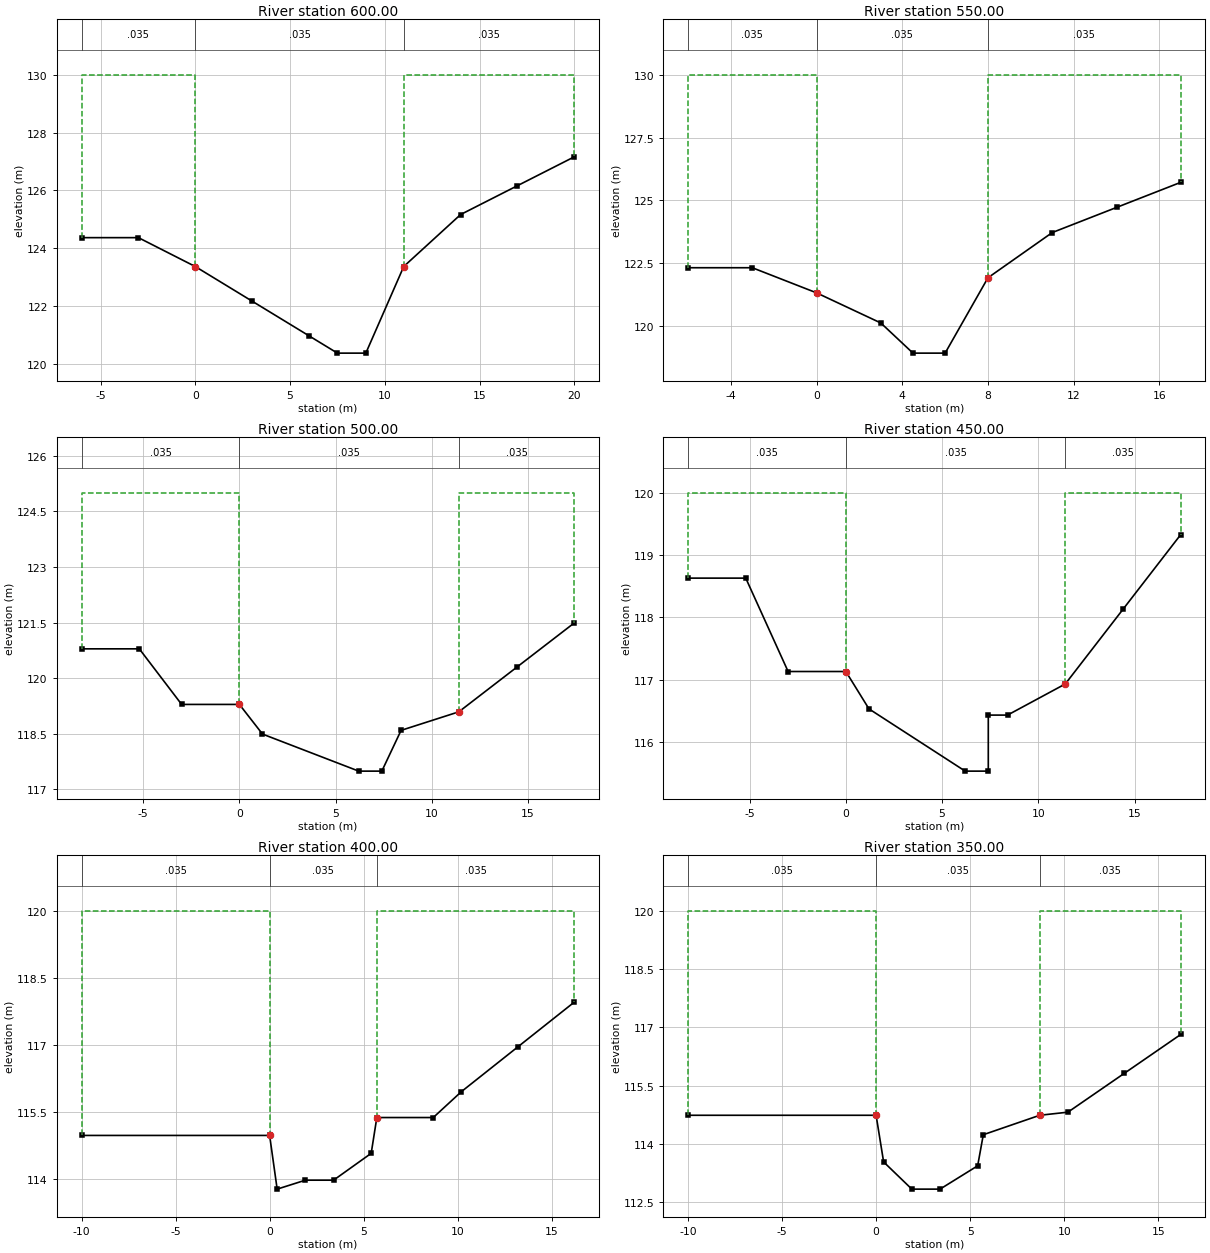
Type RM Length L Ch R = 1 ,600.00  ,50,50,50
BEGIN DESCRIPTION:
12
END DESCRIPTION:
#Sta/Elev= 11
      -6  124.36      -3  124.36       0  123.36       3  122.16       6  120.96
     7.5  120.36       9  120.36      11  123.36      14  125.16      17  126.16
      20  127.16
#Mann= 3 , 0 , 0
      -6    .035       0       0    .035       0      11    .035       0
#XS Ineff= 2 , 0
               0     130      11             130
Permanent Ineff=
       F       F
#Block Obstruct= 2 , 0
                              11
Bank Sta=0,11
XS Rating Curve= 0
Exp/Cntr=.3,.1

Type RM Length L Ch R = 1 ,550.00  ,50,50,50
BEGIN DESCRIPTION:
11
END DESCRIPTION:
#Sta/Elev= 10
      -6  122.32      -3  122.32       0  121.32       3  120.12     4.5  118.92
       6  118.92       8  121.92      11  123.72      14  124.72      17  125.72
#Mann= 3 , 0 , 0
      -6    .035       0       0    .035       0       8    .035       0
#XS Ineff= 2 , 0
               0     130       8             130
Permanent Ineff=
       F       F
#Block Obstruct= 2 , 0
                               8
Bank Sta=0,8
XS Rating Curve= 0
Exp/Cntr=.3,.1

Type RM Length L Ch R = 1 ,500.00  ,50,50,50
BEGIN DESCRIPTION:
10
END DESCRIPTION:
#Sta/Elev= 11
    -8.2  120.79    -5.2  120.79      -3  119.29       0  119.29     1.2  118.49
     6.2  117.49     7.4  117.49     8.4  118.59    11.4  119.09    14.4  120.29
    17.4  121.49
#Mann= 3 , 0 , 0
    -8.2    .035       0       0    .035       0    11.4    .035       0
#XS Ineff= 2 , 0
               0     125    11.4             125
Permanent Ineff=
       F       F
#Block Obstruct= 2 , 0
                            11.4
Bank Sta=0,11.4
XS Rating Curve= 0
Exp/Cntr=.3,.1

Type RM Length L Ch R = 1 ,450.00  ,50,50,50
BEGIN DESCRIPTION:
9
END DESCRIPTION:
#Sta/Elev= 12
    -8.2  118.63    -5.2  118.63      -3  117.13       0  117.13     1.2  116.53
     6.2  115.53     7.4  115.53     7.4  116.43     8.4  116.43    11.4  116.93
    14.4  118.13    17.4  119.33
#Mann= 3 , 0 , 0
    -8.2    .035       0       0    .035       0    11.4    .035       0
#XS Ineff= 2 , 0
               0     120    11.4             120
Permanent Ineff=
       F       F
#Block Obstruct= 2 , 0
                            11.4
Bank Sta=0,11.4
XS Rating Curve= 0
Exp/Cntr=.3,.1

Type RM Length L Ch R = 1 ,400.00  ,50,50,50
BEGIN DESCRIPTION:
8
END DESCRIPTION:
#Sta/Elev= 11
     -10  114.98       0  114.98      .4  113.78     1.9  113.98     3.4  113.98
     5.4  114.58     5.7  115.38     8.7  115.38    10.2  115.96    13.2  116.96
    16.2  117.96
#Mann= 3 , 0 , 0
     -10    .035       0       0    .035       0     5.7    .035       0
#XS Ineff= 2 , 0
               0     120     5.7             120
Permanent Ineff=
       F       F
#Block Obstruct= 2 , 0
                             5.7
Bank Sta=0,5.7
XS Rating Curve= 0
Exp/Cntr=.3,.1

Type RM Length L Ch R = 1 ,350.00  ,14,14,14
BEGIN DESCRIPTION:
7
END DESCRIPTION:
#Sta/Elev= 11
     -10  114.74       0  114.74      .4  113.54     1.9  112.84     3.4  112.84
     5.4  113.44     5.7  114.24     8.7  114.74    10.2  114.82    13.2  115.82
    16.2  116.82
#Mann= 3 , 0 , 0
     -10    .035       0       0    .035       0     8.7    .035       0
#XS Ineff= 2 , 0
               0     120     8.7             120
Permanent Ineff=
       F       F
#Block Obstruct= 2 , 0
                             8.7
Bank Sta=0,8.7
XS Rating Curve= 0
Exp/Cntr=.3,.1

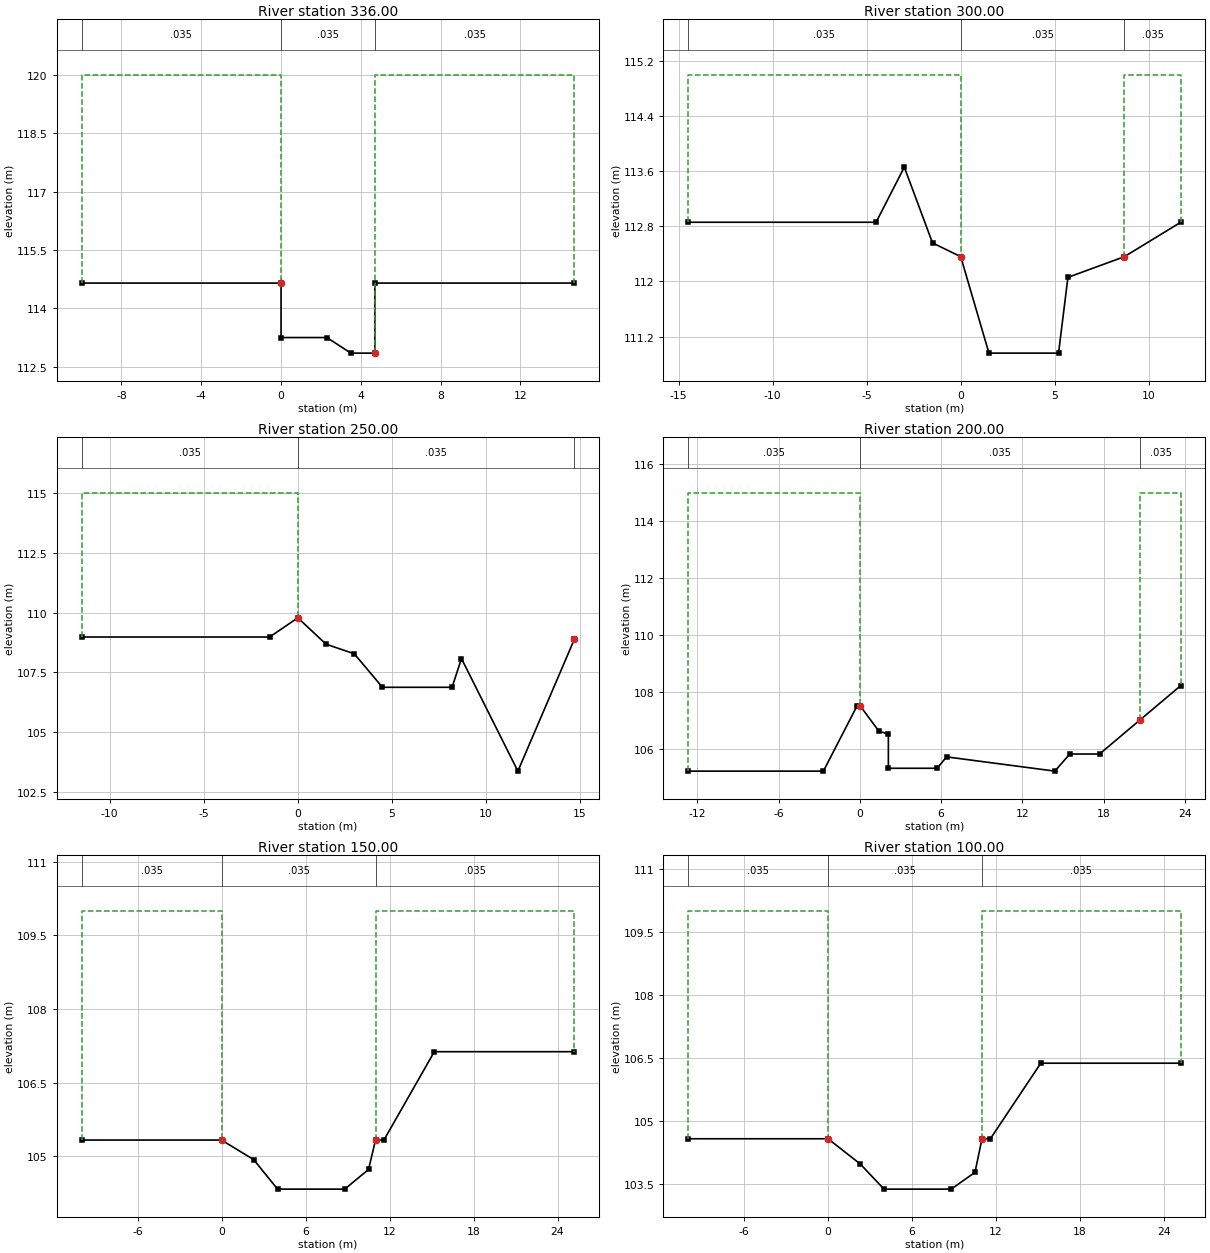
Type RM Length L Ch R = 1 ,336.00  ,36,36,36
BEGIN DESCRIPTION:
6.036
END DESCRIPTION:
#Sta/Elev= 8
     -10  114.65       0  114.65       0  113.25     2.3  113.25     3.5  112.85
     4.7  112.85     4.7  114.65    14.7  114.65
#Mann= 3 , 0 , 0
     -10    .035       0       0    .035       0     4.7    .035       0
#XS Ineff= 2 , 0
               0     120     4.7             120
Permanent Ineff=
       F       F
#Block Obstruct= 2 , 0
                             4.7
Bank Sta=0,4.7
XS Rating Curve= 0
Exp/Cntr=.3,.1

Type RM Length L Ch R = 1 ,300.00  ,50,50,50
BEGIN DESCRIPTION:
6
END DESCRIPTION:
#Sta/Elev= 10
   -14.5  112.86    -4.5  112.86      -3  113.66    -1.5  112.56       0  112.36
     1.5  110.96     5.2  110.96     5.7  112.06     8.7  112.36    11.7  112.86
#Mann= 3 , 0 , 0
   -14.5    .035       0       0    .035       0     8.7    .035       0
#XS Ineff= 2 , 0
               0     115     8.7             115
Permanent Ineff=
       F       F
#Block Obstruct= 2 , 0
                             8.7
Bank Sta=0,8.7
XS Rating Curve= 0
Exp/Cntr=.3,.1

Type RM Length L Ch R = 1 ,250.00  ,50,50,50
BEGIN DESCRIPTION:
5
END DESCRIPTION:
#Sta/Elev= 10
   -11.5  108.98    -1.5  108.98       0  109.78     1.5  108.68       3  108.28
     4.5  106.88     8.2  106.88     8.7  108.08    11.7  103.38    14.7  108.88
#Mann= 3 , 0 , 0
   -11.5    .035       0       0    .035       0    14.7    .035       0
#XS Ineff= 2 , 0
               0     115    14.7             115
Permanent Ineff=
       F       F
#Block Obstruct= 2 , 0
                            14.7
Bank Sta=0,14.7
XS Rating Curve= 0
Exp/Cntr=.3,.1

Type RM Length L Ch R = 1 ,200.00  ,50,50,50
BEGIN DESCRIPTION:
4
END DESCRIPTION:
#Sta/Elev= 14
   -12.7  105.24    -2.7  105.24     -.2  107.54       0  107.54     1.4  106.64
     2.1  106.54     2.1  105.34     5.7  105.34     6.4  105.74    14.4  105.24
    15.5  105.84    17.7  105.84    20.7  107.04    23.7  108.24
#Mann= 3 , 0 , 0
   -12.7    .035       0       0    .035       0    20.7    .035       0
#XS Ineff= 2 , 0
               0     115    20.7             115
Permanent Ineff=
       F       F
#Block Obstruct= 2 , 0
                            20.7
Bank Sta=0,20.7
XS Rating Curve= 0
Exp/Cntr=.3,.1

Type RM Length L Ch R = 1 ,150.00  ,50,50,50
BEGIN DESCRIPTION:
3
END DESCRIPTION:
#Sta/Elev= 10
     -10  105.33       0  105.33     2.3  104.93       4  104.33     8.8  104.33
    10.5  104.73      11  105.33    11.6  105.33    15.2  107.13    25.2  107.13
#Mann= 3 , 0 , 0
     -10    .035       0       0    .035       0      11    .035       0
#XS Ineff= 2 , 0
               0     110      11             110
Permanent Ineff=
       F       F
#Block Obstruct= 2 , 0
                              11
Bank Sta=0,11
XS Rating Curve= 0
Exp/Cntr=.3,.1

Type RM Length L Ch R = 1 ,100.00  ,12,12,12
BEGIN DESCRIPTION:
2
END DESCRIPTION:
#Sta/Elev= 10
     -10  104.57       0  104.57     2.3  103.97       4  103.37     8.8  103.37
    10.5  103.77      11  104.57    11.6  104.57    15.2  106.37    25.2  106.37
#Mann= 3 , 0 , 0
     -10    .035       0       0    .035       0      11    .035       0
#XS Ineff= 2 , 0
               0     110      11             110
Permanent Ineff=
       F       F
#Block Obstruct= 2 , 0
                              11
Bank Sta=0,11
XS Rating Curve= 0
Exp/Cntr=.3,.1

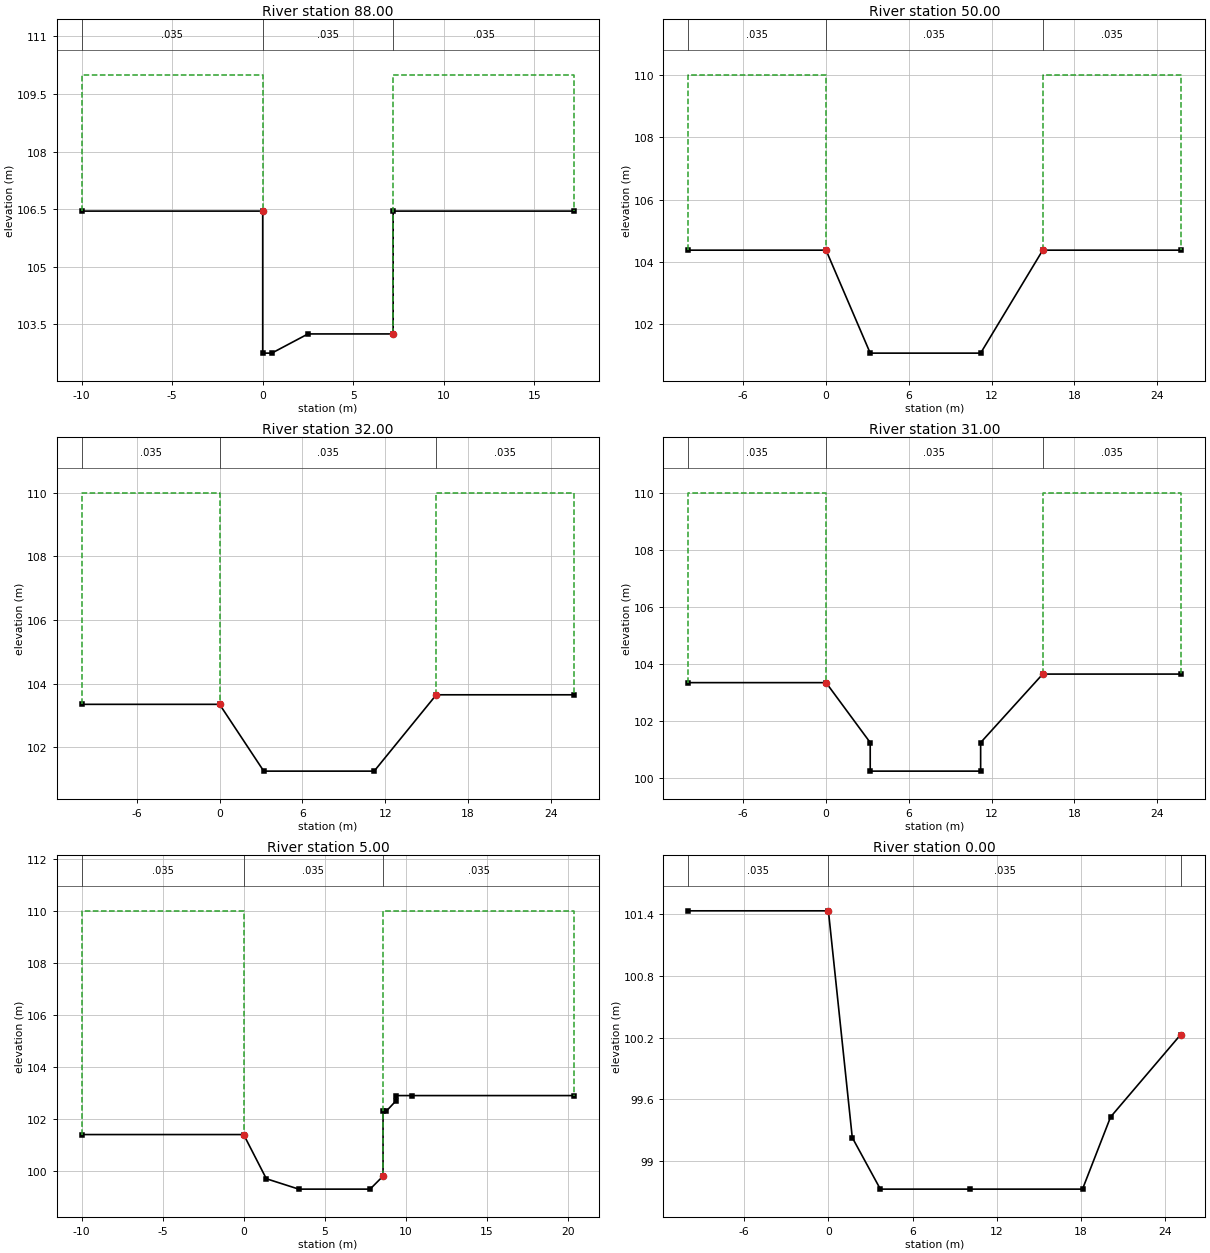
Type RM Length L Ch R = 1 ,88.00   ,38,38,38
BEGIN DESCRIPTION:
1.038
END DESCRIPTION:
#Sta/Elev= 8
     -10  106.45       0  106.45       0  102.75      .5  102.75     2.5  103.25
     7.2  103.25     7.2  106.45    17.2  106.45
#Mann= 3 , 0 , 0
     -10    .035       0       0    .035       0     7.2    .035       0
#XS Ineff= 2 , 0
               0     110     7.2             110
Permanent Ineff=
       F       F
#Block Obstruct= 2 , 0
                             7.2
Bank Sta=0,7.2
XS Rating Curve= 0
Exp/Cntr=.3,.1

Type RM Length L Ch R = 1 ,50.00   ,18,18,18
BEGIN DESCRIPTION:
1
END DESCRIPTION:
#Sta/Elev= 6
     -10  104.38       0  104.38     3.2  101.08    11.2  101.08    15.7  104.38
    25.7  104.38
#Mann= 3 , 0 , 0
     -10    .035       0       0    .035       0    15.7    .035       0
#XS Ineff= 2 , 0
               0     110    15.7             110
Permanent Ineff=
       F       F
#Block Obstruct= 2 , 0
                            15.7
Bank Sta=0,15.7
XS Rating Curve= 0
Exp/Cntr=.3,.1

Type RM Length L Ch R = 1 ,32.00   ,1,1,1
BEGIN DESCRIPTION:
0.032
END DESCRIPTION:
#Sta/Elev= 6
     -10  103.35       0  103.35     3.2  101.25    11.2  101.25    15.7  103.65
    25.7  103.65
#Mann= 3 , 0 , 0
     -10    .035       0       0    .035       0    15.7    .035       0
#XS Ineff= 2 , 0
               0     110    15.7             110
Permanent Ineff=
       F       F
#Block Obstruct= 2 , 0
                            15.7
Bank Sta=0,15.7
XS Rating Curve= 0
Exp/Cntr=.3,.1

Type RM Length L Ch R = 1 ,31.00   ,26,26,26
BEGIN DESCRIPTION:
0.031
END DESCRIPTION:
#Sta/Elev= 8
     -10  103.35       0  103.35     3.2  101.25     3.2  100.25    11.2  100.25
    11.2  101.25    15.7  103.65    25.7  103.65
#Mann= 3 , 0 , 0
     -10    .035       0       0    .035       0    15.7    .035       0
#XS Ineff= 2 , 0
               0     110    15.7             110
Permanent Ineff=
       F       F
#Block Obstruct= 2 , 0
                            15.7
Bank Sta=0,15.7
XS Rating Curve= 0
Exp/Cntr=.3,.1

Type RM Length L Ch R = 1 ,5.00    ,5,5,5
BEGIN DESCRIPTION:
0.005
END DESCRIPTION:
#Sta/Elev= 12
     -10  101.39       0  101.39     1.4   99.69     3.4   99.29     7.8   99.29
     8.6   99.79     8.6  102.29     8.8  102.29     9.4  102.69     9.4  102.89
    10.4  102.89    20.4  102.89
#Mann= 3 , 0 , 0
     -10    .035       0       0    .035       0     8.6    .035       0
#XS Ineff= 2 , 0
               0     110     8.6             110
Permanent Ineff=
       F       F
#Block Obstruct= 2 , 0
                             8.6
Bank Sta=0,8.6
XS Rating Curve= 0
Exp/Cntr=.3,.1

Type RM Length L Ch R = 1 ,0.00    ,0,0,0
BEGIN DESCRIPTION:
0
END DESCRIPTION:
#Sta/Elev= 8
     -10  101.43       0  101.43     1.7   99.23     3.7   98.73    10.1   98.73
    18.1   98.73    20.1   99.43    25.1  100.23
#Mann= 3 , 0 , 0
     -10    .035       0       0    .035       0    25.1    .035       0
#XS Ineff= 2 , 0
               0     110    25.1             110
Permanent Ineff=
       F       F
#Block Obstruct= 2 , 0
                            25.1
Bank Sta=0,25.1
XS Rating Curve= 0
Exp/Cntr=.3,.1

Chan Stop Cuts=-1