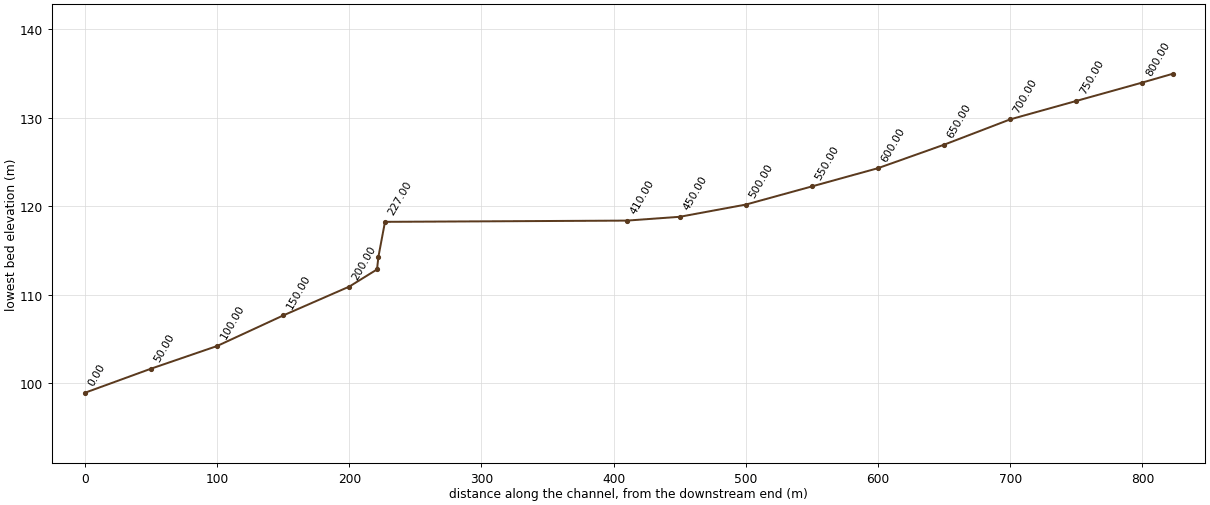
--- ASU.prj (project) ---

Proj Title=ASU
Current Plan=p01
Default Exp/Contr=.3,.1
SI Units
Geom File=g01
Flow File=f01
Plan File=p01
Y Axis Title=Elevation
X Axis Title(PF)=Main Channel Distance
X Axis Title(XS)=Station
BEGIN DESCRIPTION:
           BACK WATER COMPUTATION
      APPLICATION OF HEC-2 BY Samju Construction Engineering
      asuge-ch: 10,20,30,50,80 yr
END DESCRIPTION:
DSS Export Rating Curves= 0
DSS Export Rating Curve Sorted= 0
DSS Export Volume Flow Curves= 0
DXF OffsetX= 0
DXF OffsetY= 0
DXF ScaleX= 1
DXF ScaleY= 10

--- ASU.p01 (plan) ---

Plan Title=Imported Plan 01
Version=Version 3.0.1  Mar 2001
Short Identifier=Imported Pla
Geom File=g01
Flow File=f01
Subcritical Flow
K Sum by GR= 0
Std Step Tol= 0.003
Critical Tol= 0.003
Num of Std Step Trials= 20
Max Error Tol= 0.1
Flow Tol Ratio= 0.001
Split Flow NTrial= 30
Split Flow Tol= 0.02
Split Flow Ratio= 0.02
Log Output Level= 0
Friction Slope Method= 1
Unsteady Friction Slope Method= 2
Parabolic Critical Depth
Global Vel Dist= 0 , 0 , 0
Global Log Level= 0
CheckData=True
Encroach Param=-1 ,0,0, 0
Computation Interval=1HOUR
Output Interval=1HOUR
Run HTab= 0
Run UNet= 0
Run PostProcess= 0
UNET Theta= 1
UNET ZTol= 0.02
UNET ZSATol= 0.1
UNET MxIter= 20
UNET MaxInSteps= 20
UNET DtIC= 0
UNET DtMin= 0
UNET MaxCRTS= 20
UNET WFStab= 2
UNET SFStab= 1
UNET WFX= 1
UNET SFX= 1
UNET Convert EG Bridges=-1
UNET Use Existing IB Tables=-1
Instantaneous Interval=1HOUR
Write IC File= 0
Write Velocity= 0
Write Detailed= 0

--- ASU.f01 (steady flow) ---

Flow Title=Imported Flow 01
Version=Version 3.0.1  Mar 2001
Number of Profiles= 5
Profile Names=10YR,20YR,30YR,50YR,80YR
River Rch & RM=RIVER-1,Reach-1         ,823.00
   16.89   18.61   19.61   20.87   22.04
Boundary for River Rch & Prof#=RIVER-1,Reach-1         , 1
Up Type= 0
Dn Type= 3
Dn Slope=.064
Boundary for River Rch & Prof#=RIVER-1,Reach-1         , 2
Up Type= 0
Dn Type= 3
Dn Slope=.064
Boundary for River Rch & Prof#=RIVER-1,Reach-1         , 3
Up Type= 0
Dn Type= 3
Dn Slope=.064
Boundary for River Rch & Prof#=RIVER-1,Reach-1         , 4
Up Type= 0
Dn Type= 3
Dn Slope=.064
Boundary for River Rch & Prof#=RIVER-1,Reach-1         , 5
Up Type= 0
Dn Type= 3
Dn Slope=.064
DSS Import GetInterval= 0
DSS Import GetPeak= 0
DSS Import FillOption= 0

--- ASU.g01 (geometry) ---

Geom Title=Imported Geom 01
Version=Version 3.0.1  Mar 2001

River Reach=RIVER-1         ,Reach-1
Reach XY= 2
              .5             .95              .5             .05

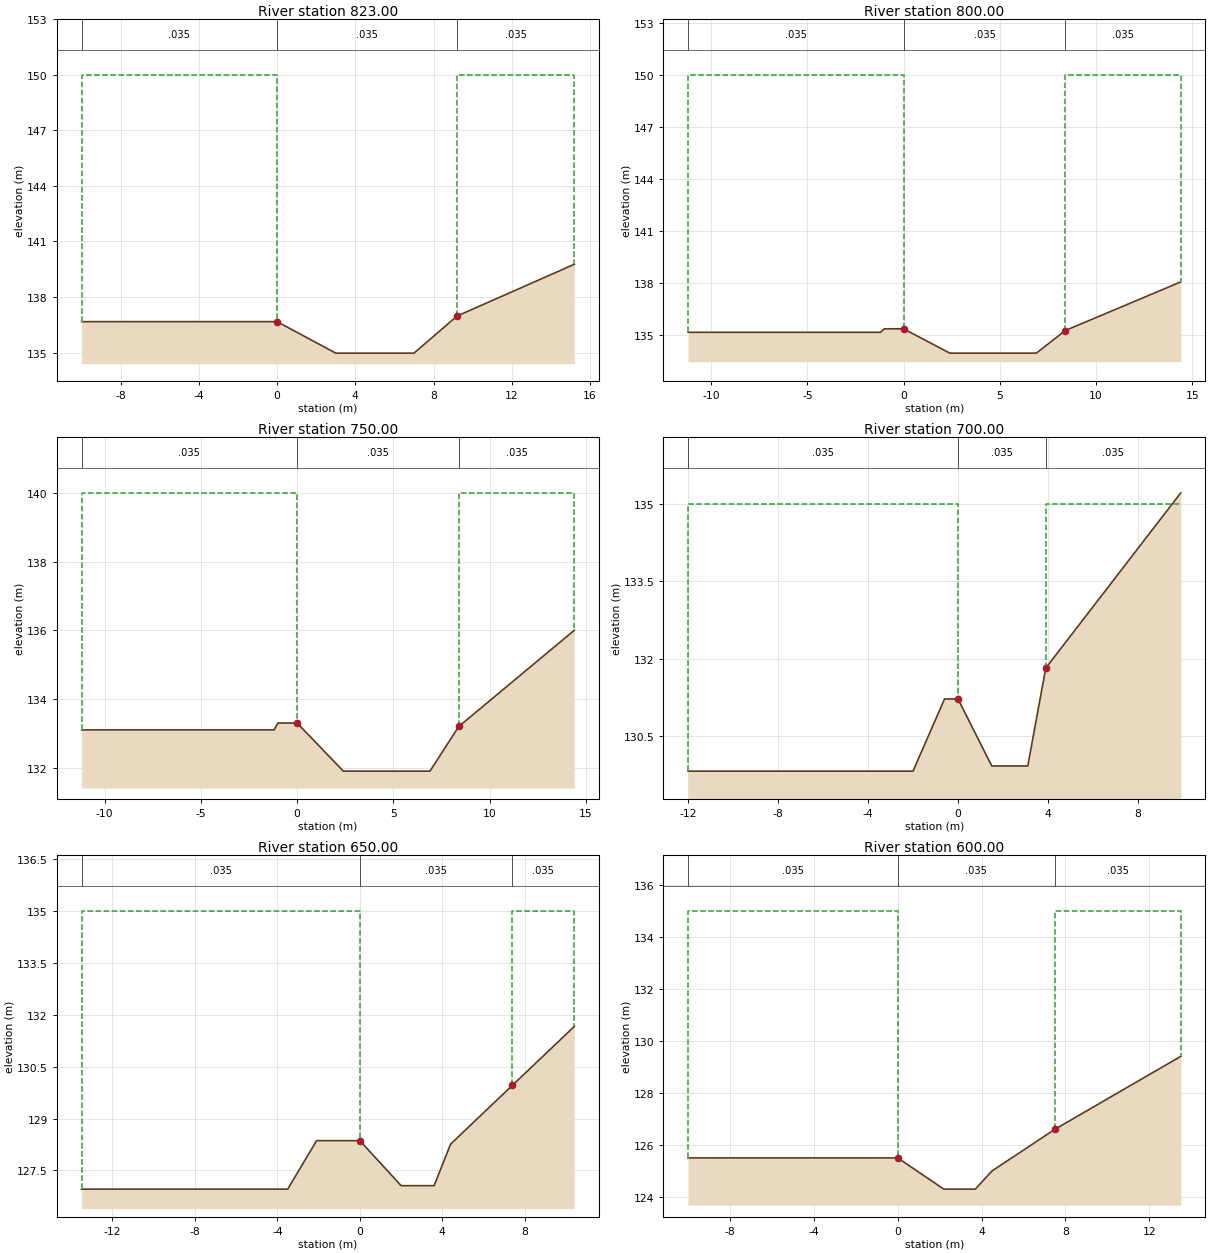
Type RM Length L Ch R = 1 ,823.00  ,23,23,23
BEGIN DESCRIPTION:
16.023
END DESCRIPTION:
#Sta/Elev= 7
     -10  136.67       0  136.67       3  134.97       7  134.97     9.2  136.97
    12.2  138.37    15.2  139.77
#Mann= 3 , 0 , 0
     -10    .035       0       0    .035       0     9.2    .035       0
#XS Ineff= 2 , 0
               0     150     9.2             150
Permanent Ineff=
       F       F
#Block Obstruct= 2 , 0
                             9.2
Bank Sta=0,9.2
XS Rating Curve= 0
Exp/Cntr=.3,.1

Type RM Length L Ch R = 1 ,800.00  ,50,50,50
BEGIN DESCRIPTION:
16
END DESCRIPTION:
#Sta/Elev= 9
   -11.2  135.18    -1.2  135.18      -1  135.38       0  135.38     2.4  133.98
     6.9  133.98     8.4  135.28    11.4  136.68    14.4  138.08
#Mann= 3 , 0 , 0
   -11.2    .035       0       0    .035       0     8.4    .035       0
#XS Ineff= 2 , 0
               0     150     8.4             150
Permanent Ineff=
       F       F
#Block Obstruct= 2 , 0
                             8.4
Bank Sta=0,8.4
XS Rating Curve= 0
Exp/Cntr=.3,.1

Type RM Length L Ch R = 1 ,750.00  ,50,50,50
BEGIN DESCRIPTION:
15
END DESCRIPTION:
#Sta/Elev= 9
   -11.2   133.1    -1.2   133.1      -1   133.3       0   133.3     2.4   131.9
     6.9   131.9     8.4   133.2    11.4   134.6    14.4     136
#Mann= 3 , 0 , 0
   -11.2    .035       0       0    .035       0     8.4    .035       0
#XS Ineff= 2 , 0
               0     140     8.4             140
Permanent Ineff=
       F       F
#Block Obstruct= 2 , 0
                             8.4
Bank Sta=0,8.4
XS Rating Curve= 0
Exp/Cntr=.3,.1

Type RM Length L Ch R = 1 ,700.00  ,50,50,50
BEGIN DESCRIPTION:
14
END DESCRIPTION:
#Sta/Elev= 9
     -12  129.82      -2  129.82     -.6  131.22       0  131.22     1.5  129.92
     3.1  129.92     3.9  131.82     6.9  133.52     9.9  135.22
#Mann= 3 , 0 , 0
     -12    .035       0       0    .035       0     3.9    .035       0
#XS Ineff= 2 , 0
               0     135     3.9             135
Permanent Ineff=
       F       F
#Block Obstruct= 2 , 0
                             3.9
Bank Sta=0,3.9
XS Rating Curve= 0
Exp/Cntr=.3,.1

Type RM Length L Ch R = 1 ,650.00  ,50,50,50
BEGIN DESCRIPTION:
13
END DESCRIPTION:
#Sta/Elev= 10
   -13.5  126.96    -3.5  126.96    -2.1  128.36    -1.5  128.36       0  128.36
       2  127.06     3.6  127.06     4.4  128.26     7.4  129.96    10.4  131.66
#Mann= 3 , 0 , 0
   -13.5    .035       0       0    .035       0     7.4    .035       0
#XS Ineff= 2 , 0
               0     135     7.4             135
Permanent Ineff=
       F       F
#Block Obstruct= 2 , 0
                             7.4
Bank Sta=0,7.4
XS Rating Curve= 0
Exp/Cntr=.3,.1

Type RM Length L Ch R = 1 ,600.00  ,50,50,50
BEGIN DESCRIPTION:
12
END DESCRIPTION:
#Sta/Elev= 8
     -10  125.51       0  125.51     2.2  124.31     3.7  124.31     4.5  125.01
     7.5  126.61    10.5  128.01    13.5  129.41
#Mann= 3 , 0 , 0
     -10    .035       0       0    .035       0     7.5    .035       0
#XS Ineff= 2 , 0
               0     135     7.5             135
Permanent Ineff=
       F       F
#Block Obstruct= 2 , 0
                             7.5
Bank Sta=0,7.5
XS Rating Curve= 0
Exp/Cntr=.3,.1

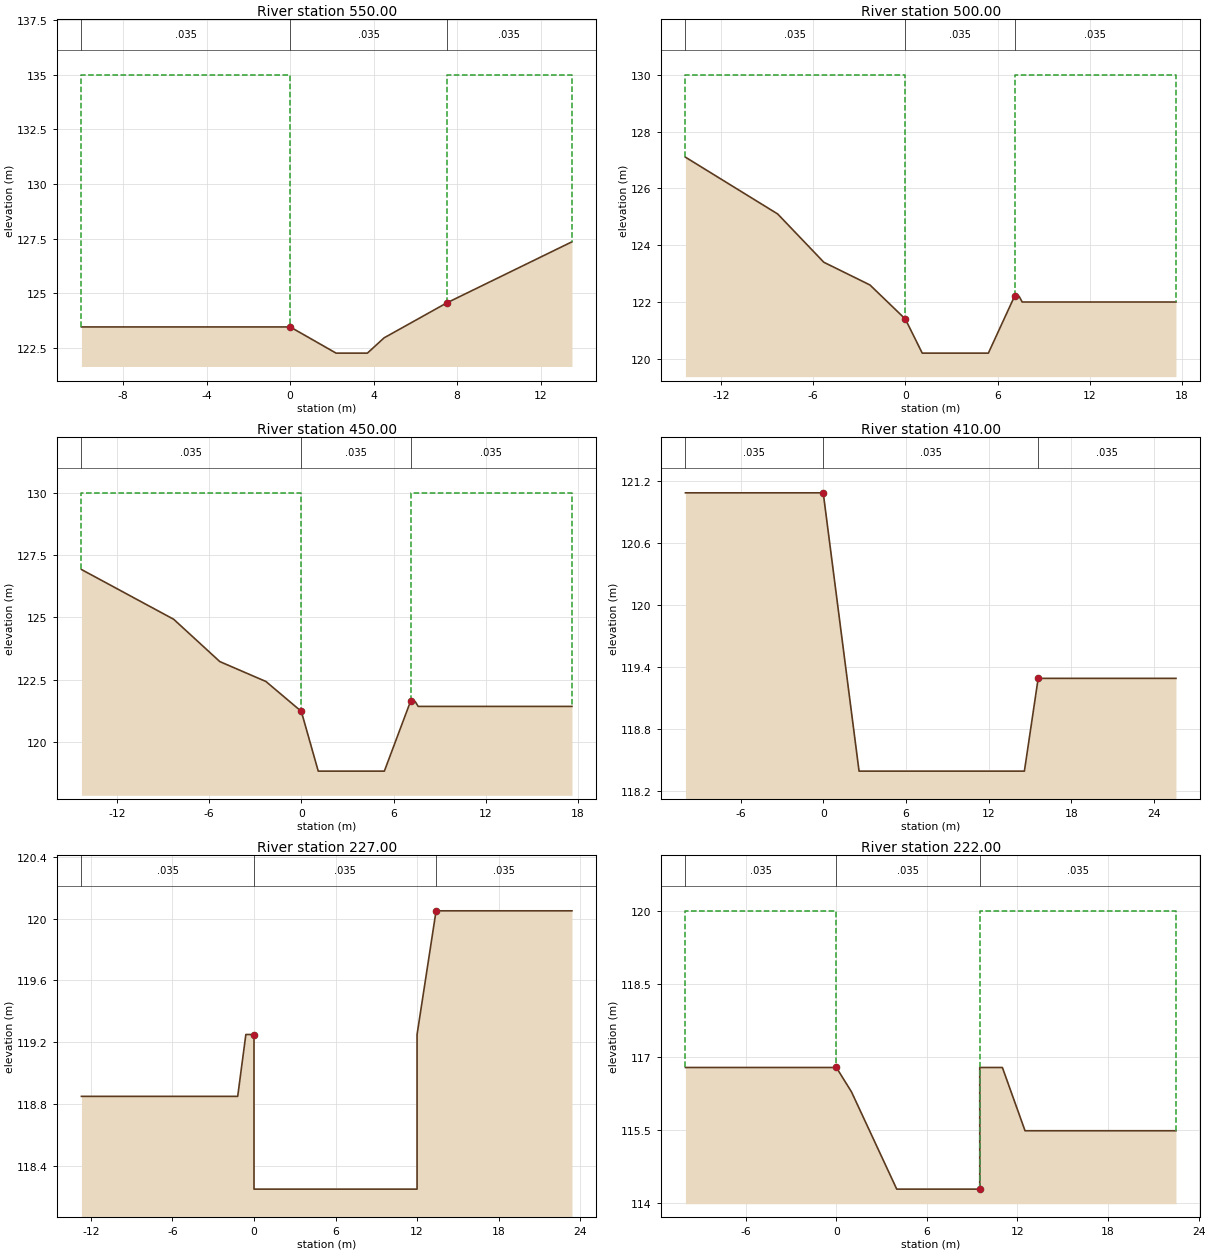
Type RM Length L Ch R = 1 ,550.00  ,50,50,50
BEGIN DESCRIPTION:
11
END DESCRIPTION:
#Sta/Elev= 8
     -10  123.45       0  123.45     2.2  122.25     3.7  122.25     4.5  122.95
     7.5  124.55    10.5  125.95    13.5  127.35
#Mann= 3 , 0 , 0
     -10    .035       0       0    .035       0     7.5    .035       0
#XS Ineff= 2 , 0
               0     135     7.5             135
Permanent Ineff=
       F       F
#Block Obstruct= 2 , 0
                             7.5
Bank Sta=0,7.5
XS Rating Curve= 0
Exp/Cntr=.3,.1

Type RM Length L Ch R = 1 ,500.00  ,50,50,50
BEGIN DESCRIPTION:
10
END DESCRIPTION:
#Sta/Elev= 12
   -14.3   127.1   -11.3   126.1    -8.3   125.1    -5.3   123.4    -2.3   122.6
       0   121.4     1.1   120.2     5.4   120.2     7.1   122.2     7.4   122.2
     7.6     122    17.6     122
#Mann= 3 , 0 , 0
   -14.3    .035       0       0    .035       0     7.1    .035       0
#XS Ineff= 2 , 0
               0     130     7.1             130
Permanent Ineff=
       F       F
#Block Obstruct= 2 , 0
                             7.1
Bank Sta=0,7.1
XS Rating Curve= 0
Exp/Cntr=.3,.1

Type RM Length L Ch R = 1 ,450.00  ,40,40,40
BEGIN DESCRIPTION:
9
END DESCRIPTION:
#Sta/Elev= 12
   -14.3  126.92   -11.3  125.92    -8.3  124.92    -5.3  123.22    -2.3  122.42
       0  121.22     1.1  118.82     5.4  118.82     7.1  121.62     7.4  121.62
     7.6  121.42    17.6  121.42
#Mann= 3 , 0 , 0
   -14.3    .035       0       0    .035       0     7.1    .035       0
#XS Ineff= 2 , 0
               0     130     7.1             130
Permanent Ineff=
       F       F
#Block Obstruct= 2 , 0
                             7.1
Bank Sta=0,7.1
XS Rating Curve= 0
Exp/Cntr=.3,.1

Type RM Length L Ch R = 1 ,410.00  ,183,183,183
BEGIN DESCRIPTION:
8.01
END DESCRIPTION:
#Sta/Elev= 6
     -10  121.09       0  121.09     2.6  118.39    14.6  118.39    15.6  119.29
    25.6  119.29
#Mann= 3 , 0 , 0
     -10    .035       0       0    .035       0    15.6    .035       0
#XS Ineff= 2 , 0
               0     130    15.6             130
Permanent Ineff=
       F       F
#Block Obstruct= 2 , 0
                            15.6
Bank Sta=0,15.6
XS Rating Curve= 0
Exp/Cntr=.3,.1

Type RM Length L Ch R = 1 ,227.00  ,5,5,5
BEGIN DESCRIPTION:
4.027
END DESCRIPTION:
#Sta/Elev= 10
   -12.7  118.85    -2.7  118.85    -1.2  118.85     -.6  119.25       0  119.25
       0  118.25      12  118.25      12  119.25    13.4  120.05    23.4  120.05
#Mann= 3 , 0 , 0
   -12.7    .035       0       0    .035       0    13.4    .035       0
#XS Ineff= 2 , 0
               0     130    13.4             130
Permanent Ineff=
       F       F
#Block Obstruct= 2 , 0
                            13.4
Bank Sta=0,13.4
XS Rating Curve= 0
Exp/Cntr=.3,.1

Type RM Length L Ch R = 1 ,222.00  ,1,1,1
BEGIN DESCRIPTION:
4.022
END DESCRIPTION:
#Sta/Elev= 10
     -10  116.78       0  116.78       1  116.28       4  114.28     5.5  114.28
     9.5  114.28     9.5  116.78      11  116.78    12.5  115.48    22.5  115.48
#Mann= 3 , 0 , 0
     -10    .035       0       0    .035       0     9.5    .035       0
#XS Ineff= 2 , 0
               0     120     9.5             120
Permanent Ineff=
       F       F
#Block Obstruct= 2 , 0
                             9.5
Bank Sta=0,9.5
XS Rating Curve= 0
Exp/Cntr=.3,.1

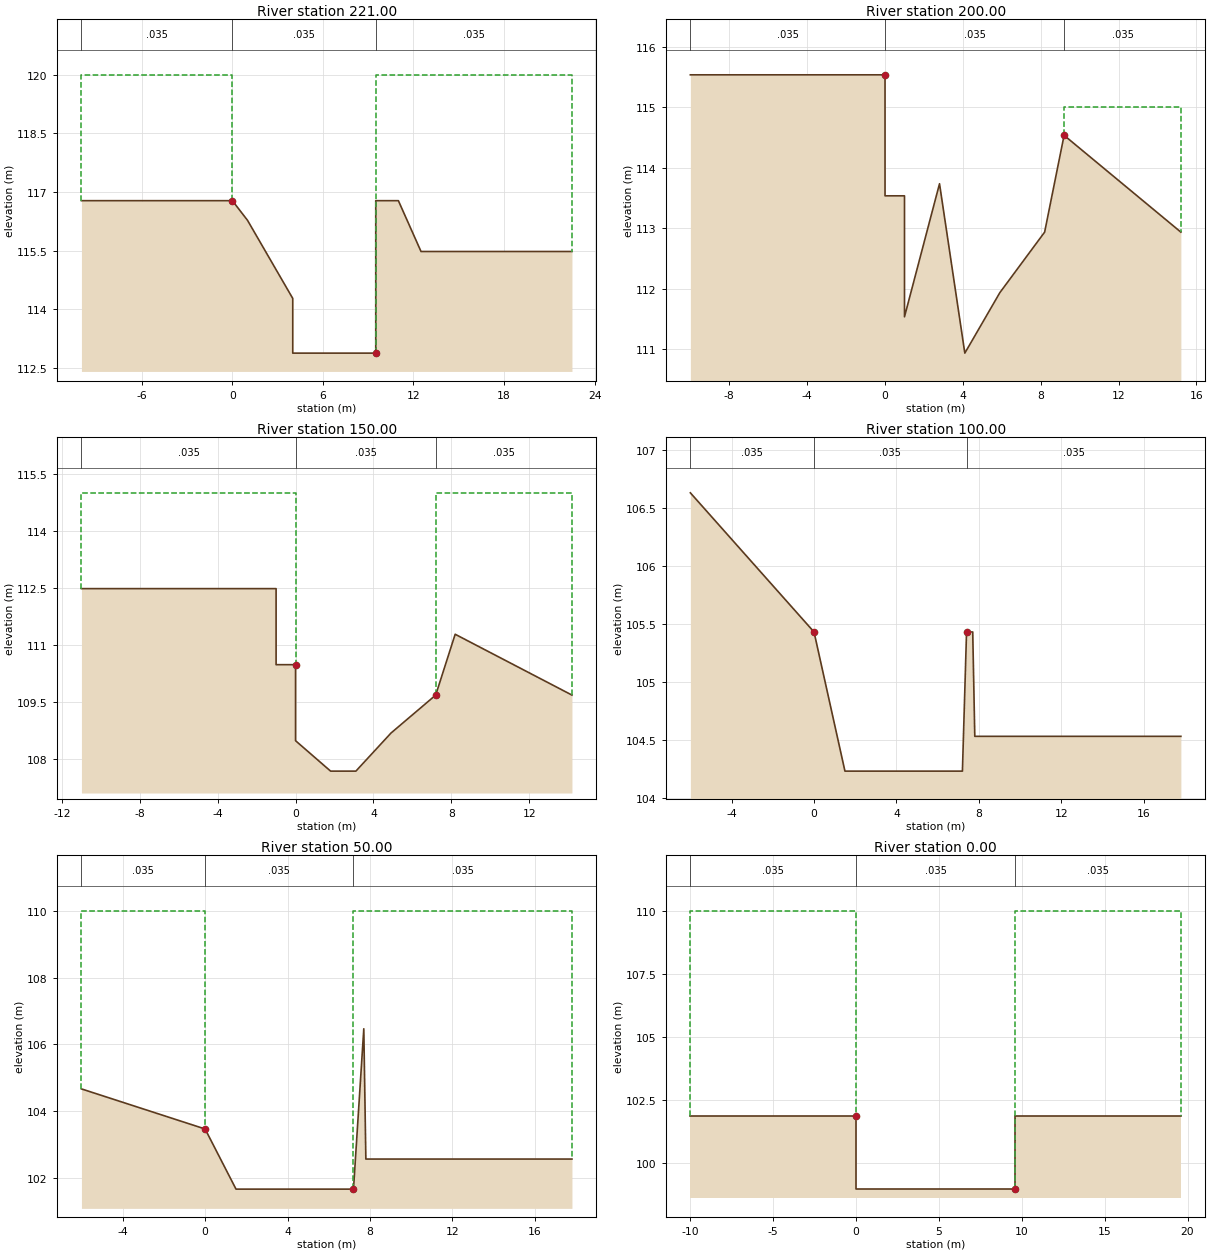
Type RM Length L Ch R = 1 ,221.00  ,21,21,21
BEGIN DESCRIPTION:
4.021
END DESCRIPTION:
#Sta/Elev= 12
     -10  116.78       0  116.78       1  116.28       4  114.28       4  112.88
     5.5  112.88     9.5  112.88     9.5  114.28     9.5  116.78      11  116.78
    12.5  115.48    22.5  115.48
#Mann= 3 , 0 , 0
     -10    .035       0       0    .035       0     9.5    .035       0
#XS Ineff= 2 , 0
               0     120     9.5             120
Permanent Ineff=
       F       F
#Block Obstruct= 2 , 0
                             9.5
Bank Sta=0,9.5
XS Rating Curve= 0
Exp/Cntr=.3,.1

Type RM Length L Ch R = 1 ,200.00  ,50,50,50
BEGIN DESCRIPTION:
4
END DESCRIPTION:
#Sta/Elev= 12
     -10  115.54       0  115.54       0  113.54       1  113.54       1  111.54
     2.8  113.74     4.1  110.94     5.9  111.94     8.2  112.94     9.2  114.54
    12.2  113.74    15.2  112.94
#Mann= 3 , 0 , 0
     -10    .035       0       0    .035       0     9.2    .035       0
#XS Ineff= 2 , 0
               0     115     9.2             115
Permanent Ineff=
       F       F
#Block Obstruct= 2 , 0
                             9.2
Bank Sta=0,9.2
XS Rating Curve= 0
Exp/Cntr=.3,.1

Type RM Length L Ch R = 1 ,150.00  ,50,50,50
BEGIN DESCRIPTION:
3
END DESCRIPTION:
#Sta/Elev= 12
     -11  112.48      -1  112.48      -1  110.48       0  110.48       0  108.48
     1.8  107.68     3.1  107.68     4.9  108.68     7.2  109.68     8.2  111.28
    11.2  110.48    14.2  109.68
#Mann= 3 , 0 , 0
     -11    .035       0       0    .035       0     7.2    .035       0
#XS Ineff= 2 , 0
               0     115     7.2             115
Permanent Ineff=
       F       F
#Block Obstruct= 2 , 0
                             7.2
Bank Sta=0,7.2
XS Rating Curve= 0
Exp/Cntr=.3,.1

Type RM Length L Ch R = 1 ,100.00  ,50,50,50
BEGIN DESCRIPTION:
2
END DESCRIPTION:
#Sta/Elev= 9
      -6  106.63      -3  106.03       0  105.43     1.5  104.23     7.2  104.23
     7.4  105.43     7.7  105.43     7.8  104.53    17.8  104.53
#Mann= 3 , 0 , 0
      -6    .035       0       0    .035       0     7.4    .035       0
#XS Ineff= 2 , 0
               0     115     7.4             115
Permanent Ineff=
       F       F
#Block Obstruct= 2 , 0
                             7.4
Bank Sta=0,7.4
XS Rating Curve= 0
Exp/Cntr=.3,.1

Type RM Length L Ch R = 1 ,50.00   ,50,50,50
BEGIN DESCRIPTION:
1
END DESCRIPTION:
#Sta/Elev= 8
      -6  104.67      -3  104.07       0  103.47     1.5  101.67     7.2  101.67
     7.7  106.47     7.8  102.57    17.8  102.57
#Mann= 3 , 0 , 0
      -6    .035       0       0    .035       0     7.2    .035       0
#XS Ineff= 2 , 0
               0     110     7.2             110
Permanent Ineff=
       F       F
#Block Obstruct= 2 , 0
                             7.4
Bank Sta=0,7.2
XS Rating Curve= 0
Exp/Cntr=.3,.1

Type RM Length L Ch R = 1 ,0.00    ,0,0,0
BEGIN DESCRIPTION:
0
END DESCRIPTION:
#Sta/Elev= 6
     -10  101.85       0  101.85       0   98.95     9.6   98.95     9.6  101.85
    19.6  101.85
#Mann= 3 , 0 , 0
     -10    .035       0       0    .035       0     9.6    .035       0
#XS Ineff= 2 , 0
               0     110     9.6             110
Permanent Ineff=
       F       F
#Block Obstruct= 2 , 0
                             9.6
Bank Sta=0,9.6
XS Rating Curve= 0
Exp/Cntr=.3,.1

Chan Stop Cuts=-1