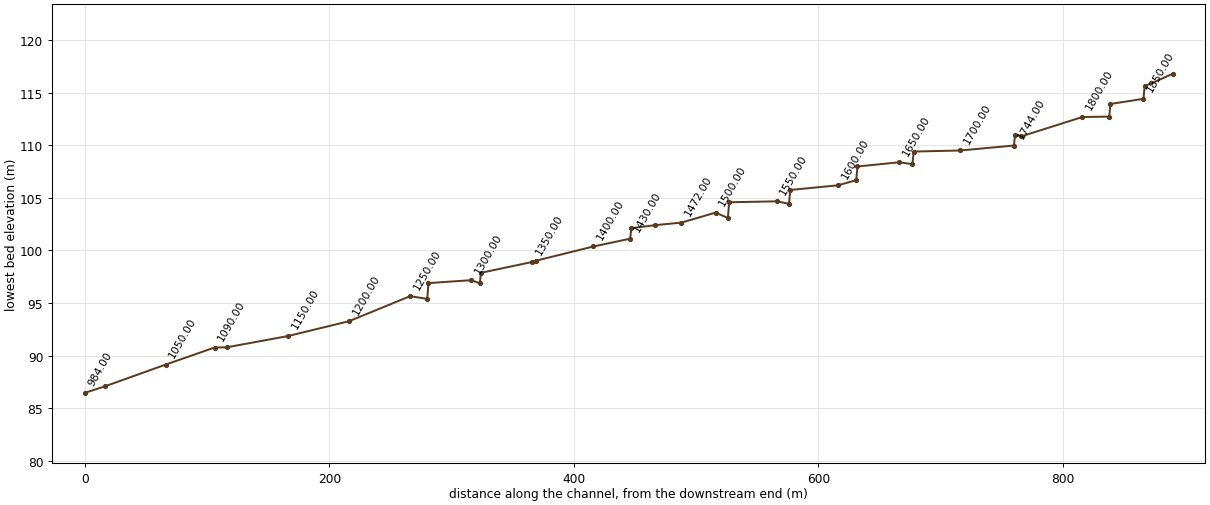
--- MDC.prj (project) ---

Proj Title=MYUNGDAE
Current Plan=p01
Default Exp/Contr=.3,.1
SI Units
Geom File=g01
Flow File=f01
Plan File=p01
Y Axis Title=Elevation
X Axis Title(PF)=Main Channel Distance
X Axis Title(XS)=Station
BEGIN DESCRIPTION:
           BACK WATER COMPUTATION
      APPLICATION OF HEC-2 BY Samju Construction Engineering
      meongdae-ch: 10,20,30,50,80 yr
END DESCRIPTION:
DSS Export Rating Curves= 0
DSS Export Rating Curve Sorted= 0
DSS Export Volume Flow Curves= 0
DXF OffsetX= 0
DXF OffsetY= 0
DXF ScaleX= 1
DXF ScaleY= 10

--- MDC.p01 (plan) ---

Plan Title=Imported Plan 01
Version=Version 3.0.1  Mar 2001
Short Identifier=Imported Pla
Geom File=g01
Flow File=f01
Subcritical Flow
K Sum by GR= 0
Std Step Tol= 0.003
Critical Tol= 0.003
Num of Std Step Trials= 20
Max Error Tol= 0.1
Flow Tol Ratio= 0.001
Split Flow NTrial= 30
Split Flow Tol= 0.02
Split Flow Ratio= 0.02
Log Output Level= 0
Friction Slope Method= 1
Unsteady Friction Slope Method= 2
Parabolic Critical Depth
Global Vel Dist= 0 , 0 , 0
Global Log Level= 0
CheckData=True
Encroach Param=-1 ,0,0, 0
Computation Interval=1HOUR
Output Interval=1HOUR
Run HTab= 0
Run UNet= 0
Run PostProcess= 0
UNET Theta= 1
UNET ZTol= 0.02
UNET ZSATol= 0.1
UNET MxIter= 20
UNET MaxInSteps= 20
UNET DtIC= 0
UNET DtMin= 0
UNET MaxCRTS= 20
UNET WFStab= 2
UNET SFStab= 1
UNET WFX= 1
UNET SFX= 1
UNET Convert EG Bridges=-1
UNET Use Existing IB Tables=-1
Instantaneous Interval=1HOUR
Write IC File= 0
Write Velocity= 0
Write Detailed= 0

--- MDC.f01 (steady flow) ---

Flow Title=Imported Flow 01
Version=Version 3.0.1  Mar 2001
Number of Profiles= 5
Profile Names=10YR,20YR,30YR,50YR,80YR
River Rch & RM=RIVER-1,Reach-1         ,1874.00
   20.41   22.48    23.7   25.23   26.64
River Rch & RM=RIVER-1,Reach-1         ,850.00
   25.78   28.41   29.96    31.9   33.69
Boundary for River Rch & Prof#=RIVER-1,Reach-1         , 1
Up Type= 0
Dn Type= 3
Dn Slope=.032
Boundary for River Rch & Prof#=RIVER-1,Reach-1         , 2
Up Type= 0
Dn Type= 3
Dn Slope=.032
Boundary for River Rch & Prof#=RIVER-1,Reach-1         , 3
Up Type= 0
Dn Type= 3
Dn Slope=.032
Boundary for River Rch & Prof#=RIVER-1,Reach-1         , 4
Up Type= 0
Dn Type= 3
Dn Slope=.032
Boundary for River Rch & Prof#=RIVER-1,Reach-1         , 5
Up Type= 0
Dn Type= 3
Dn Slope=.032
DSS Import GetInterval= 0
DSS Import GetPeak= 0
DSS Import FillOption= 0

--- MDC.g01 (geometry) ---

Geom Title=Imported Geom 01
Version=Version 3.0.1  Mar 2001

River Reach=RIVER-1         ,Reach-1
Reach XY= 2
              .5             .95              .5             .05

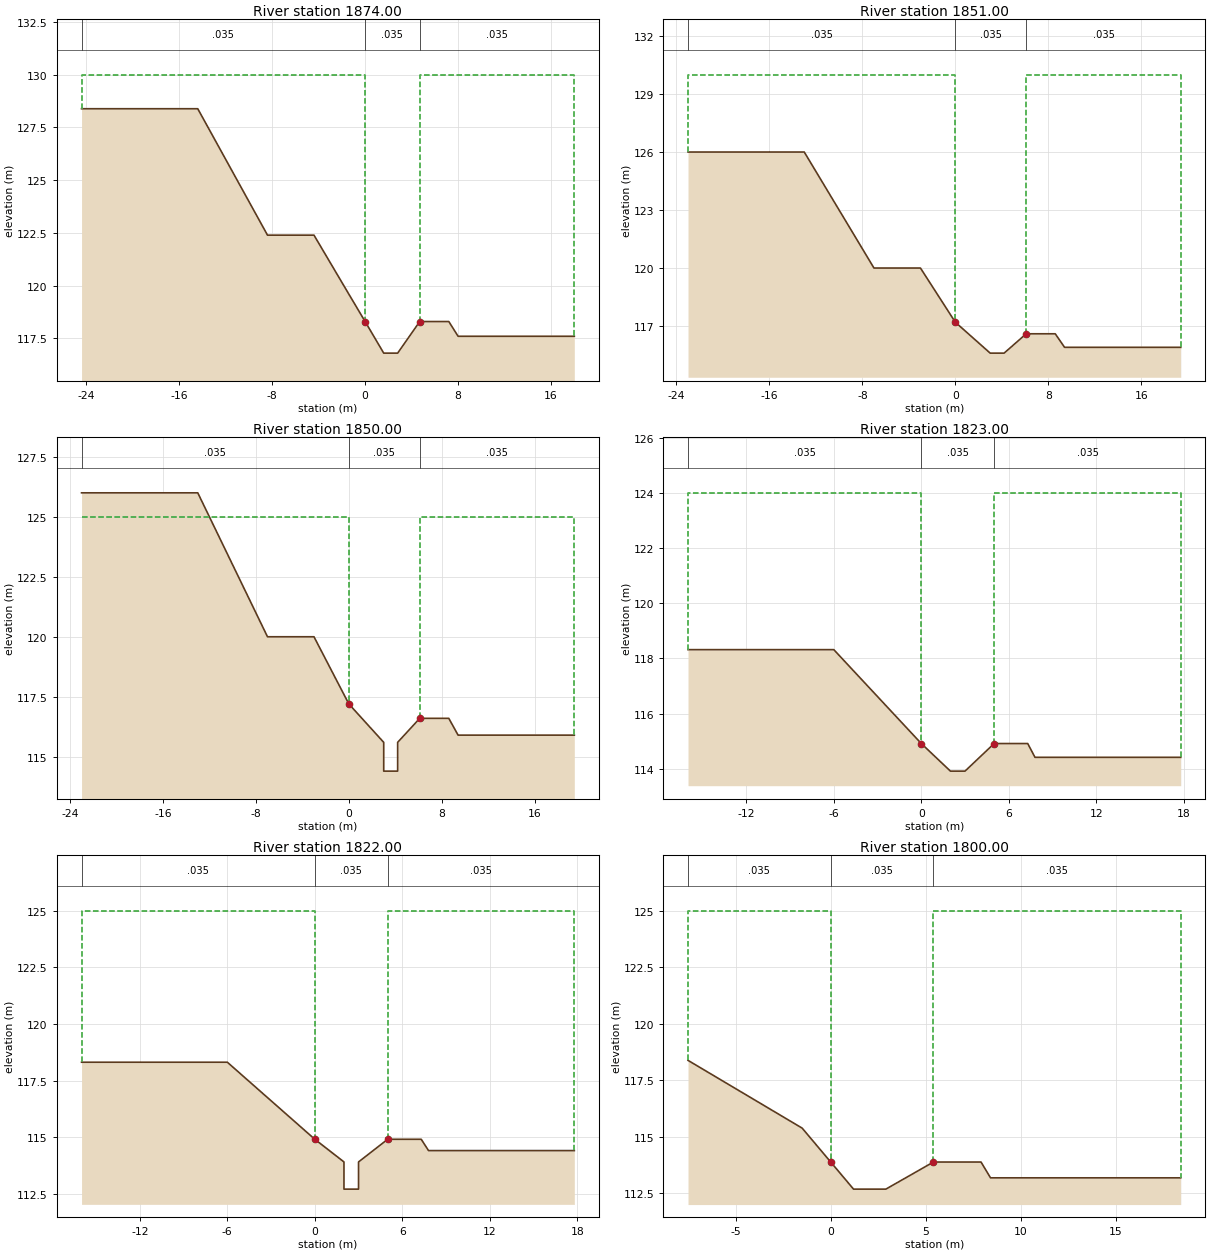
Type RM Length L Ch R = 1 ,1874.00 ,23,23,23
BEGIN DESCRIPTION:
37.024
END DESCRIPTION:
#Sta/Elev= 13
   -24.4  128.39   -14.4  128.39   -11.4  125.39    -8.4  122.39    -4.4  122.39
    -1.4  119.59       0  118.29     1.6  116.79     2.8  116.79     4.7  118.29
     7.2  118.29       8  117.59      18  117.59
#Mann= 3 , 0 , 0
   -24.4    .035       0       0    .035       0     4.7    .035       0
#XS Ineff= 2 , 0
               0     130     4.7             130
Permanent Ineff=
       F       F
#Block Obstruct= 2 , 0
                             4.7
Bank Sta=0,4.7
XS Rating Curve= 0
Exp/Cntr=.3,.1

Type RM Length L Ch R = 1 ,1851.00 ,1,1,1
BEGIN DESCRIPTION:
37.001
END DESCRIPTION:
#Sta/Elev= 12
     -23  126.01     -13  126.01     -10  123.01      -7  120.01      -3  120.01
       0  117.21       3  115.61     4.2  115.61     6.1  116.61     8.6  116.61
     9.4  115.91    19.4  115.91
#Mann= 3 , 0 , 0
     -23    .035       0       0    .035       0     6.1    .035       0
#XS Ineff= 2 , 0
               0     130     6.1             130
Permanent Ineff=
       F       F
#Block Obstruct= 2 , 0
                             6.1
Bank Sta=0,6.1
XS Rating Curve= 0
Exp/Cntr=.3,.1

Type RM Length L Ch R = 1 ,1850.00 ,27,27,27
BEGIN DESCRIPTION:
37
END DESCRIPTION:
#Sta/Elev= 14
     -23  126.01     -13  126.01     -10  123.01      -7  120.01      -3  120.01
       0  117.21       3  115.61       3  114.41     4.2  114.41     4.2  115.61
     6.1  116.61     8.6  116.61     9.4  115.91    19.4  115.91
#Mann= 3 , 0 , 0
     -23    .035       0       0    .035       0     6.1    .035       0
#XS Ineff= 2 , 0
               0     125     6.1             125
Permanent Ineff=
       F       F
#Block Obstruct= 2 , 0
                             6.2
Bank Sta=0,6.1
XS Rating Curve= 0
Exp/Cntr=.3,.1

Type RM Length L Ch R = 1 ,1823.00 ,1,1,1
BEGIN DESCRIPTION:
36.023
END DESCRIPTION:
#Sta/Elev= 10
     -16  118.32      -6  118.32      -3  116.62       0  114.92       2  113.92
       3  113.92       5  114.92     7.3  114.92     7.8  114.42    17.8  114.42
#Mann= 3 , 0 , 0
     -16    .035       0       0    .035       0       5    .035       0
#XS Ineff= 2 , 0
               0     124       5             124
Permanent Ineff=
       F       F
#Block Obstruct= 2 , 0
                               5
Bank Sta=0,5
XS Rating Curve= 0
Exp/Cntr=.3,.1

Type RM Length L Ch R = 1 ,1822.00 ,22,22,22
BEGIN DESCRIPTION:
36.022
END DESCRIPTION:
#Sta/Elev= 12
     -16  118.32      -6  118.32      -3  116.62       0  114.92       2  113.92
       2  112.72       3  112.72       3  113.92       5  114.92     7.3  114.92
     7.8  114.42    17.8  114.42
#Mann= 3 , 0 , 0
     -16    .035       0       0    .035       0       5    .035       0
#XS Ineff= 2 , 0
               0     125       5             125
Permanent Ineff=
       F       F
#Block Obstruct= 2 , 0
                               5
Bank Sta=0,5
XS Rating Curve= 0
Exp/Cntr=.3,.1

Type RM Length L Ch R = 1 ,1800.00 ,50,50,50
BEGIN DESCRIPTION:
36
END DESCRIPTION:
#Sta/Elev= 10
    -7.5  118.38    -4.5  116.88    -1.5  115.38       0  113.88     1.2  112.68
     2.9  112.68     5.4  113.88     7.9  113.88     8.4  113.18    18.4  113.18
#Mann= 3 , 0 , 0
    -7.5    .035       0       0    .035       0     5.4    .035       0
#XS Ineff= 2 , 0
               0     125     5.4             125
Permanent Ineff=
       F       F
#Block Obstruct= 2 , 0
                             5.4
Bank Sta=0,5.4
XS Rating Curve= 0
Exp/Cntr=.3,.1

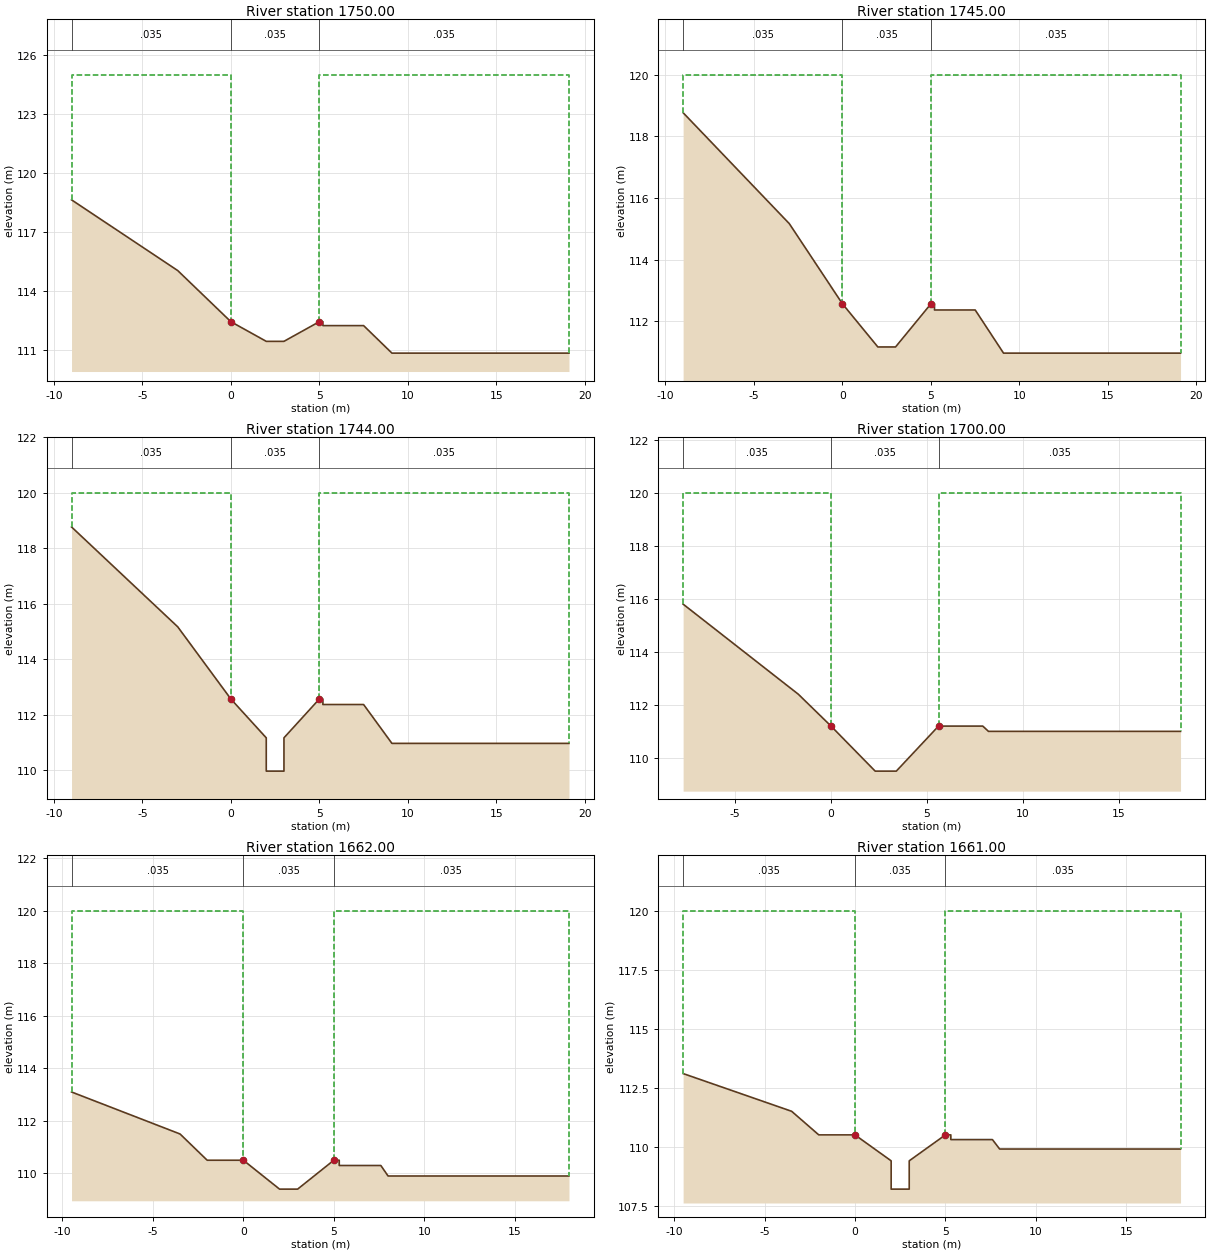
Type RM Length L Ch R = 1 ,1750.00 ,5,5,5
BEGIN DESCRIPTION:
35
END DESCRIPTION:
#Sta/Elev= 12
      -9  118.64      -6  116.84      -3  115.04       0  112.44       2  111.44
       3  111.44       5  112.44     5.2  112.44     5.2  112.24     7.5  112.24
     9.1  110.84    19.1  110.84
#Mann= 3 , 0 , 0
      -9    .035       0       0    .035       0       5    .035       0
#XS Ineff= 2 , 0
               0     125       5             125
Permanent Ineff=
       F       F
#Block Obstruct= 2 , 0
                               5
Bank Sta=0,5
XS Rating Curve= 0
Exp/Cntr=.3,.1

Type RM Length L Ch R = 1 ,1745.00 ,1,1,1
BEGIN DESCRIPTION:
34.045
END DESCRIPTION:
#Sta/Elev= 12
      -9  118.77      -6  116.97      -3  115.17       0  112.57       2  111.17
       3  111.17       5  112.57     5.2  112.57     5.2  112.37     7.5  112.37
     9.1  110.97    19.1  110.97
#Mann= 3 , 0 , 0
      -9    .035       0       0    .035       0       5    .035       0
#XS Ineff= 2 , 0
               0     120       5             120
Permanent Ineff=
       F       F
#Block Obstruct= 2 , 0
                               5
Bank Sta=0,5
XS Rating Curve= 0
Exp/Cntr=.3,.1

Type RM Length L Ch R = 1 ,1744.00 ,44,44,44
BEGIN DESCRIPTION:
34.044
END DESCRIPTION:
#Sta/Elev= 14
      -9  118.77      -6  116.97      -3  115.17       0  112.57       2  111.17
       2  109.97       3  109.97       3  111.17       5  112.57     5.2  112.57
     5.2  112.37     7.5  112.37     9.1  110.97    19.1  110.97
#Mann= 3 , 0 , 0
      -9    .035       0       0    .035       0       5    .035       0
#XS Ineff= 2 , 0
               0     120       5             120
Permanent Ineff=
       F       F
#Block Obstruct= 2 , 0
                               5
Bank Sta=0,5
XS Rating Curve= 0
Exp/Cntr=.3,.1

Type RM Length L Ch R = 1 ,1700.00 ,38,38,38
BEGIN DESCRIPTION:
34
END DESCRIPTION:
#Sta/Elev= 10
    -7.7   115.8    -4.7   114.1    -1.7   112.4       0   111.2     2.3   109.5
     3.4   109.5     5.6   111.2     7.9   111.2     8.2     111    18.2     111
#Mann= 3 , 0 , 0
    -7.7    .035       0       0    .035       0     5.6    .035       0
#XS Ineff= 2 , 0
               0     120     5.6             120
Permanent Ineff=
       F       F
#Block Obstruct= 2 , 0
                             5.6
Bank Sta=0,5.6
XS Rating Curve= 0
Exp/Cntr=.3,.1

Type RM Length L Ch R = 1 ,1662.00 ,1,1,1
BEGIN DESCRIPTION:
33.012
END DESCRIPTION:
#Sta/Elev= 13
    -9.5   113.1    -6.5   112.3    -3.5   111.5      -2   110.5       0   110.5
       2   109.4       3   109.4       5   110.5     5.3   110.5     5.3   110.3
     7.6   110.3       8   109.9      18   109.9
#Mann= 3 , 0 , 0
    -9.5    .035       0       0    .035       0       5    .035       0
#XS Ineff= 2 , 0
               0     120       5             120
Permanent Ineff=
       F       F
#Block Obstruct= 2 , 0
                               5
Bank Sta=0,5
XS Rating Curve= 0
Exp/Cntr=.3,.1

Type RM Length L Ch R = 1 ,1661.00 ,11,11,11
BEGIN DESCRIPTION:
33.011
END DESCRIPTION:
#Sta/Elev= 15
    -9.5   113.1    -6.5   112.3    -3.5   111.5      -2   110.5       0   110.5
       2   109.4       2   108.2       3   108.2       3   109.4       5   110.5
     5.3   110.5     5.3   110.3     7.6   110.3       8   109.9      18   109.9
#Mann= 3 , 0 , 0
    -9.5    .035       0       0    .035       0       5    .035       0
#XS Ineff= 2 , 0
               0     120       5             120
Permanent Ineff=
       F       F
#Block Obstruct= 2 , 0
                               5
Bank Sta=0,5
XS Rating Curve= 0
Exp/Cntr=.3,.1

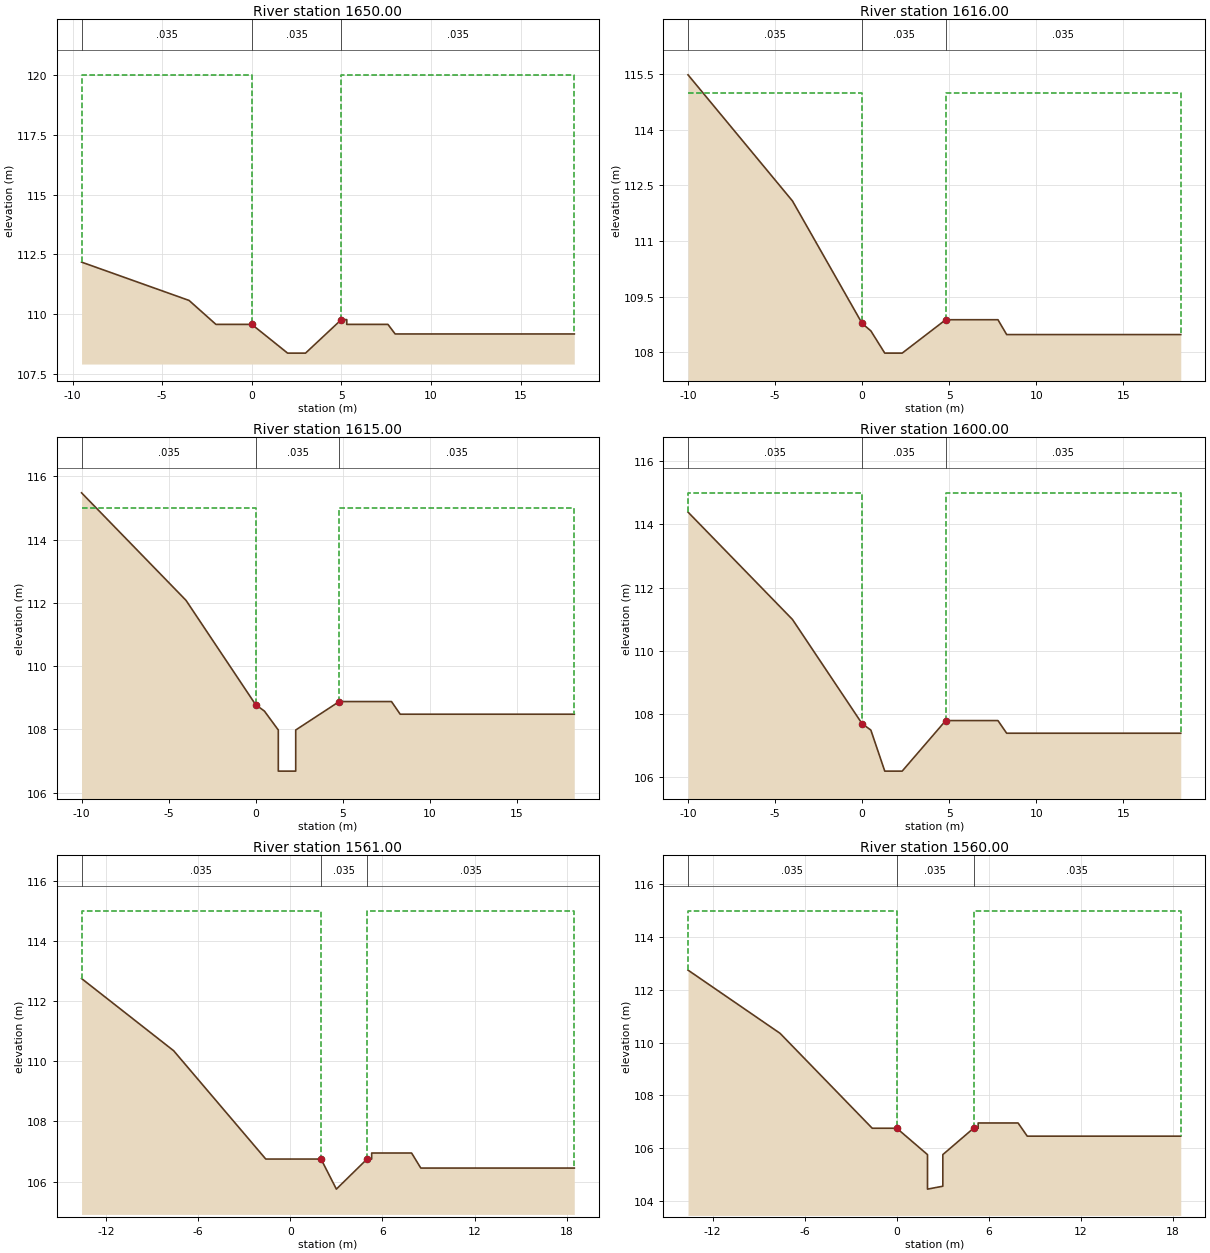
Type RM Length L Ch R = 1 ,1650.00 ,34,34,34
BEGIN DESCRIPTION:
33
END DESCRIPTION:
#Sta/Elev= 13
    -9.5  112.18    -6.5  111.38    -3.5  110.58      -2  109.58       0  109.58
       2  108.38       3  108.38       5  109.78     5.3  109.78     5.3  109.58
     7.6  109.58       8  109.18      18  109.18
#Mann= 3 , 0 , 0
    -9.5    .035       0       0    .035       0       5    .035       0
#XS Ineff= 2 , 0
               0     120       5             120
Permanent Ineff=
       F       F
#Block Obstruct= 2 , 0
                               5
Bank Sta=0,5
XS Rating Curve= 0
Exp/Cntr=.3,.1

Type RM Length L Ch R = 1 ,1616.00 ,1,1,1
BEGIN DESCRIPTION:
32.016
END DESCRIPTION:
#Sta/Elev= 11
     -10  115.48      -7  113.78      -4  112.08       0  108.78      .5  108.58
     1.3  107.98     2.3  107.98     4.8  108.88     7.8  108.88     8.3  108.48
    18.3  108.48
#Mann= 3 , 0 , 0
     -10    .035       0       0    .035       0     4.8    .035       0
#XS Ineff= 2 , 0
               0     115     4.8             115
Permanent Ineff=
       F       F
#Block Obstruct= 2 , 0
                             4.8
Bank Sta=0,4.8
XS Rating Curve= 0
Exp/Cntr=.3,.1

Type RM Length L Ch R = 1 ,1615.00 ,15,15,15
BEGIN DESCRIPTION:
32.015
END DESCRIPTION:
#Sta/Elev= 13
     -10  115.48      -7  113.78      -4  112.08       0  108.78      .5  108.58
     1.3  107.98     1.3  106.68     2.3  106.68     2.3  107.98     4.8  108.88
     7.8  108.88     8.3  108.48    18.3  108.48
#Mann= 3 , 0 , 0
     -10    .035       0       0    .035       0     4.8    .035       0
#XS Ineff= 2 , 0
               0     115     4.8             115
Permanent Ineff=
       F       F
#Block Obstruct= 2 , 0
                             4.8
Bank Sta=0,4.8
XS Rating Curve= 0
Exp/Cntr=.3,.1

Type RM Length L Ch R = 1 ,1600.00 ,39,39,39
BEGIN DESCRIPTION:
32
END DESCRIPTION:
#Sta/Elev= 11
     -10  114.39      -7  112.69      -4  110.99       0  107.69      .5  107.49
     1.3  106.19     2.3  106.19     4.8  107.79     7.8  107.79     8.3  107.39
    18.3  107.39
#Mann= 3 , 0 , 0
     -10    .035       0       0    .035       0     4.8    .035       0
#XS Ineff= 2 , 0
               0     115     4.8             115
Permanent Ineff=
       F       F
#Block Obstruct= 2 , 0
                             4.8
Bank Sta=0,4.8
XS Rating Curve= 0
Exp/Cntr=.3,.1

Type RM Length L Ch R = 1 ,1561.00 ,1,1,1
BEGIN DESCRIPTION:
31.011
END DESCRIPTION:
#Sta/Elev= 13
   -13.6  112.75   -10.6  111.55    -7.6  110.35    -4.6  108.55    -1.6  106.75
       2  106.75       3  105.75       5  106.75     5.3  106.75     5.3  106.95
     7.9  106.95     8.5  106.45    18.5  106.45
#Mann= 3 , 0 , 0
   -13.6    .035       0       2    .035       0       5    .035       0
#XS Ineff= 2 , 0
               2     115       5             115
Permanent Ineff=
       F       F
#Block Obstruct= 2 , 0
                               5
Bank Sta=2,5
XS Rating Curve= 0
Exp/Cntr=.3,.1

Type RM Length L Ch R = 1 ,1560.00 ,10,10,10
BEGIN DESCRIPTION:
31.01
END DESCRIPTION:
#Sta/Elev= 16
   -13.6  112.75   -10.6  111.55    -7.6  110.35    -4.6  108.55    -1.6  106.75
       0  106.75       2  105.75       2  104.44       3  104.55       3  105.75
       5  106.75     5.3  106.75     5.3  106.95     7.9  106.95     8.5  106.45
    18.5  106.45
#Mann= 3 , 0 , 0
   -13.6    .035       0       0    .035       0       5    .035       0
#XS Ineff= 2 , 0
               0     115       5             115
Permanent Ineff=
       F       F
#Block Obstruct= 2 , 0
                               5
Bank Sta=0,5
XS Rating Curve= 0
Exp/Cntr=.3,.1

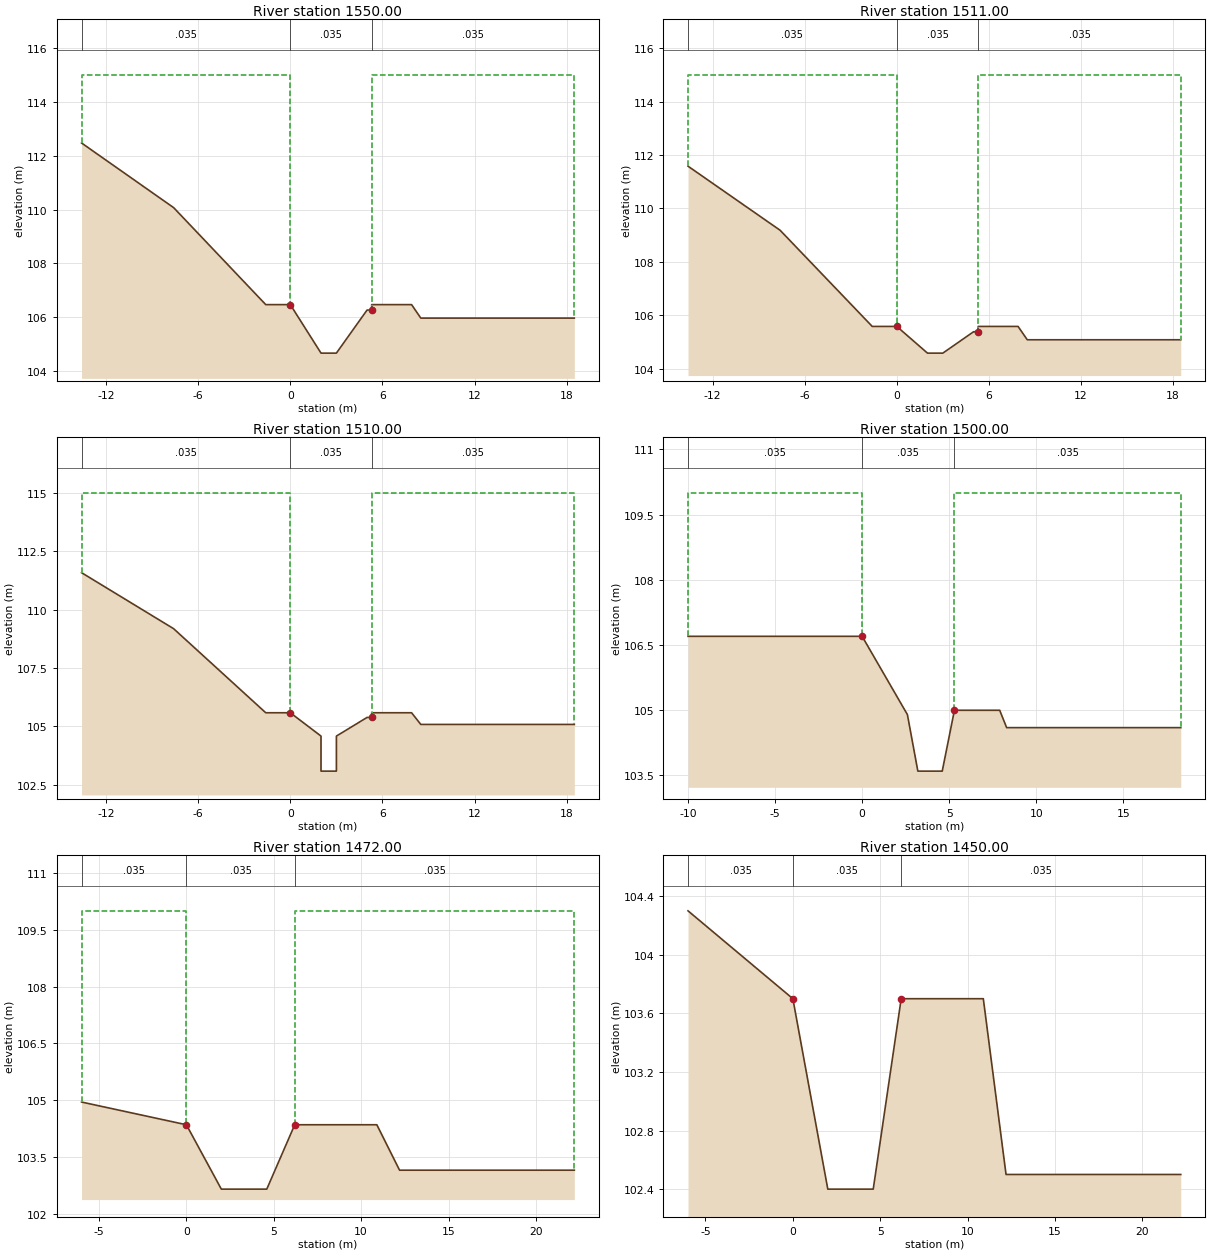
Type RM Length L Ch R = 1 ,1550.00 ,39,39,39
BEGIN DESCRIPTION:
31
END DESCRIPTION:
#Sta/Elev= 14
   -13.6  112.47   -10.6  111.27    -7.6  110.07    -4.6  108.27    -1.6  106.47
       0  106.47       2  104.67       3  104.67       5  106.27     5.3  106.27
     5.3  106.47     7.9  106.47     8.5  105.97    18.5  105.97
#Mann= 3 , 0 , 0
   -13.6    .035       0       0    .035       0     5.3    .035       0
#XS Ineff= 2 , 0
               0     115     5.3             115
Permanent Ineff=
       F       F
#Block Obstruct= 2 , 0
                             5.3
Bank Sta=0,5.3
XS Rating Curve= 0
Exp/Cntr=.3,.1

Type RM Length L Ch R = 1 ,1511.00 ,1,1,1
BEGIN DESCRIPTION:
30.011
END DESCRIPTION:
#Sta/Elev= 14
   -13.6  111.58   -10.6  110.38    -7.6  109.18    -4.6  107.38    -1.6  105.58
       0  105.58       2  104.58       3  104.58       5  105.38     5.3  105.38
     5.3  105.58     7.9  105.58     8.5  105.08    18.5  105.08
#Mann= 3 , 0 , 0
   -13.6    .035       0       0    .035       0     5.3    .035       0
#XS Ineff= 2 , 0
               0     115     5.3             115
Permanent Ineff=
       F       F
#Block Obstruct= 2 , 0
                             5.3
Bank Sta=0,5.3
XS Rating Curve= 0
Exp/Cntr=.3,.1

Type RM Length L Ch R = 1 ,1510.00 ,10,10,10
BEGIN DESCRIPTION:
30.01
END DESCRIPTION:
#Sta/Elev= 16
   -13.6  111.58   -10.6  110.38    -7.6  109.18    -4.6  107.38    -1.6  105.58
       0  105.58       2  104.58       2  103.08       3  103.08       3  104.58
       5  105.38     5.3  105.38     5.3  105.58     7.9  105.58     8.5  105.08
    18.5  105.08
#Mann= 3 , 0 , 0
   -13.6    .035       0       0    .035       0     5.3    .035       0
#XS Ineff= 2 , 0
               0     115     5.3             115
Permanent Ineff=
       F       F
#Block Obstruct= 2 , 0
                             5.3
Bank Sta=0,5.3
XS Rating Curve= 0
Exp/Cntr=.3,.1

Type RM Length L Ch R = 1 ,1500.00 ,28,28,28
BEGIN DESCRIPTION:
30
END DESCRIPTION:
#Sta/Elev= 9
     -10   106.7       0   106.7     2.6   104.9     3.2   103.6     4.6   103.6
     5.3     105     7.9     105     8.3   104.6    18.3   104.6
#Mann= 3 , 0 , 0
     -10    .035       0       0    .035       0     5.3    .035       0
#XS Ineff= 2 , 0
               0     110     5.3             110
Permanent Ineff=
       F       F
#Block Obstruct= 2 , 0
                             5.3
Bank Sta=0,5.3
XS Rating Curve= 0
Exp/Cntr=.3,.1

Type RM Length L Ch R = 1 ,1472.00 ,22,22,22
BEGIN DESCRIPTION:
29.022
END DESCRIPTION:
#Sta/Elev= 9
      -6  104.95      -3  104.65       0  104.35       2  102.65     4.6  102.65
     6.2  104.35    10.9  104.35    12.2  103.15    22.2  103.15
#Mann= 3 , 0 , 0
      -6    .035       0       0    .035       0     6.2    .035       0
#XS Ineff= 2 , 0
               0     110     6.2             110
Permanent Ineff=
       F       F
#Block Obstruct= 2 , 0
                             6.2
Bank Sta=0,6.2
XS Rating Curve= 0
Exp/Cntr=.3,.1

Type RM Length L Ch R = 1 ,1450.00 ,19,19,19
BEGIN DESCRIPTION:
29
END DESCRIPTION:
#Sta/Elev= 9
      -6   104.3      -3     104       0   103.7       2   102.4     4.6   102.4
     6.2   103.7    10.9   103.7    12.2   102.5    22.2   102.5
#Mann= 3 , 0 , 0
      -6    .035       0       0    .035       0     6.2    .035       0
#XS Ineff= 2 , 0
               0     110     6.2             110
Permanent Ineff=
       F       F
#Block Obstruct= 2 , 0
                             6.2
Bank Sta=0,6.2
XS Rating Curve= 0
Exp/Cntr=.3,.1

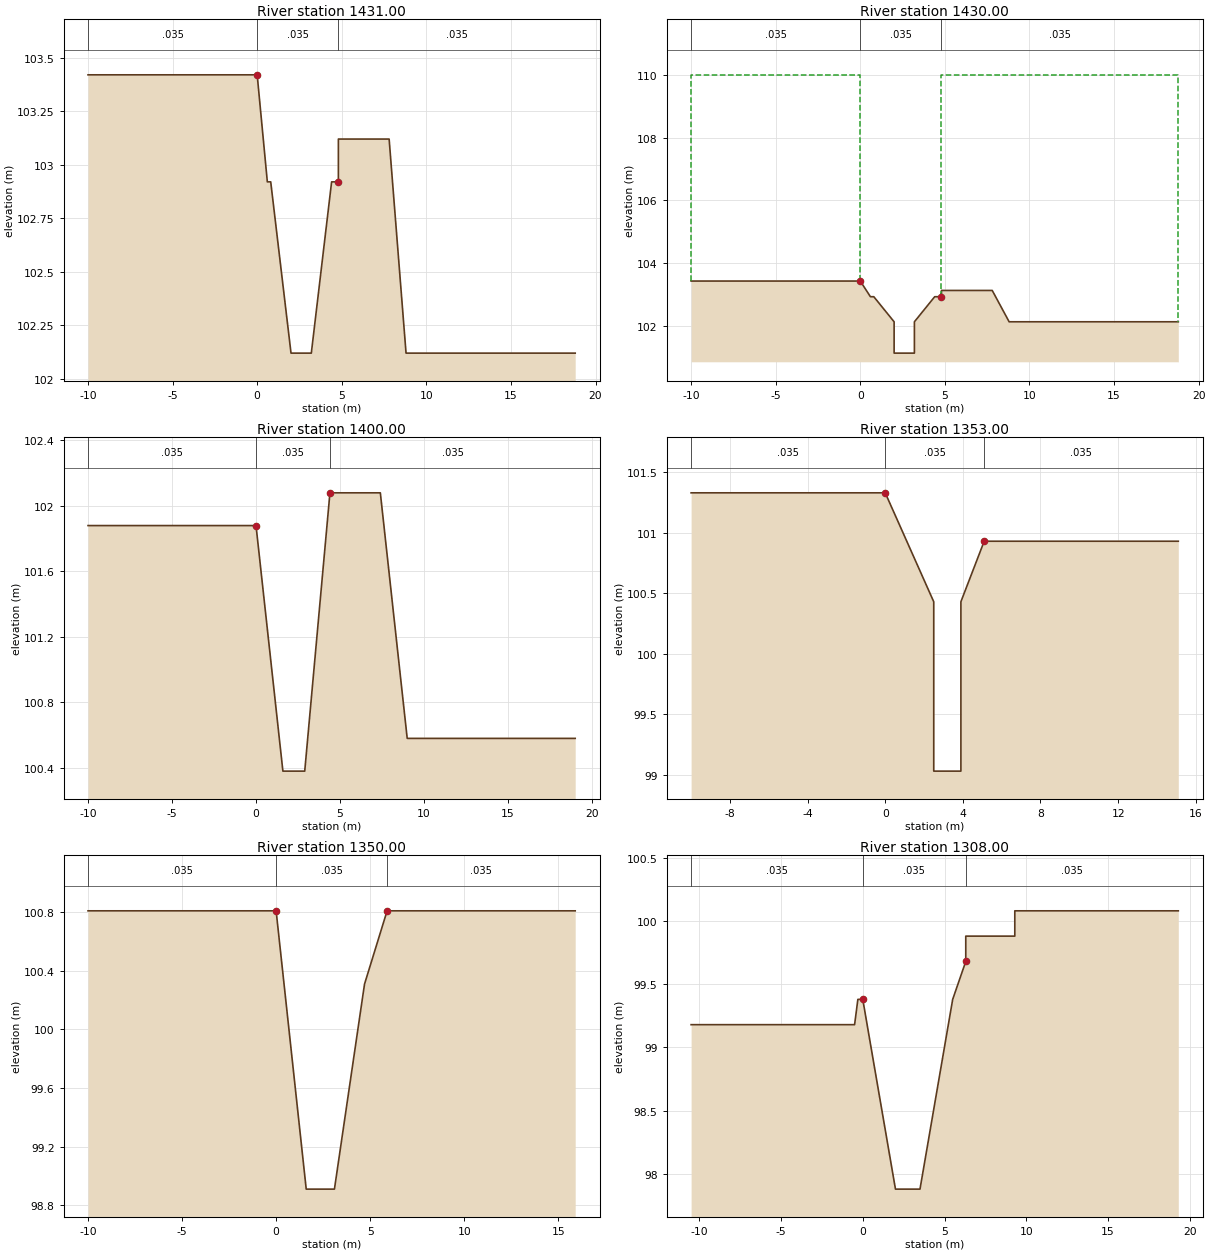
Type RM Length L Ch R = 1 ,1431.00 ,1,1,1
BEGIN DESCRIPTION:
28.031
END DESCRIPTION:
#Sta/Elev= 12
     -10  103.42       0  103.42      .6  102.92      .8  102.92       2  102.12
     3.2  102.12     4.4  102.92     4.8  102.92     4.8  103.12     7.8  103.12
     8.8  102.12    18.8  102.12
#Mann= 3 , 0 , 0
     -10    .035       0       0    .035       0     4.8    .035       0
#XS Ineff= 2 , 0
               0     110     4.8             110
Permanent Ineff=
       F       F
#Block Obstruct= 2 , 0
                             4.8
Bank Sta=0,4.8
XS Rating Curve= 0
Exp/Cntr=.3,.1

Type RM Length L Ch R = 1 ,1430.00 ,30,30,30
BEGIN DESCRIPTION:
28.03
END DESCRIPTION:
#Sta/Elev= 14
     -10  103.42       0  103.42      .6  102.92      .8  102.92       2  102.12
       2  101.12     3.2  101.12     3.2  102.12     4.4  102.92     4.8  102.92
     4.8  103.12     7.8  103.12     8.8  102.12    18.8  102.12
#Mann= 3 , 0 , 0
     -10    .035       0       0    .035       0     4.8    .035       0
#XS Ineff= 2 , 0
               0     110     4.8             110
Permanent Ineff=
       F       F
#Block Obstruct= 2 , 0
                             4.8
Bank Sta=0,4.8
XS Rating Curve= 0
Exp/Cntr=.3,.1

Type RM Length L Ch R = 1 ,1400.00 ,47,47,47
BEGIN DESCRIPTION:
28
END DESCRIPTION:
#Sta/Elev= 8
     -10  101.88       0  101.88     1.6  100.38     2.9  100.38     4.4  102.08
     7.4  102.08       9  100.58      19  100.58
#Mann= 3 , 0 , 0
     -10    .035       0       0    .035       0     4.4    .035       0
#XS Ineff= 2 , 0
               0     110     4.4             110
Permanent Ineff=
       F       F
#Block Obstruct= 2 , 0
                             4.4
Bank Sta=0,4.4
XS Rating Curve= 0
Exp/Cntr=.3,.1

Type RM Length L Ch R = 1 ,1353.00 ,3,3,3
BEGIN DESCRIPTION:
27.003
END DESCRIPTION:
#Sta/Elev= 8
     -10  101.33       0  101.33     2.5  100.43     2.5   99.03     3.9   99.03
     3.9  100.43     5.1  100.93    15.1  100.93
#Mann= 3 , 0 , 0
     -10    .035       0       0    .035       0     5.1    .035       0
#XS Ineff= 2 , 0
               0     110     5.1             110
Permanent Ineff=
       F       F
#Block Obstruct= 2 , 0
                             5.1
Bank Sta=0,5.1
XS Rating Curve= 0
Exp/Cntr=.3,.1

Type RM Length L Ch R = 1 ,1350.00 ,42,42,42
BEGIN DESCRIPTION:
27
END DESCRIPTION:
#Sta/Elev= 7
     -10  100.81       0  100.81     1.6   98.91     3.1   98.91     4.7  100.31
     5.9  100.81    15.9  100.81
#Mann= 3 , 0 , 0
     -10    .035       0       0    .035       0     5.9    .035       0
#XS Ineff= 2 , 0
               0     110     5.9             110
Permanent Ineff=
       F       F
#Block Obstruct= 2 , 0
                             5.9
Bank Sta=0,5.9
XS Rating Curve= 0
Exp/Cntr=.3,.1

Type RM Length L Ch R = 1 ,1308.00 ,1,1,1
BEGIN DESCRIPTION:
26.008
END DESCRIPTION:
#Sta/Elev= 12
   -10.5   99.18     -.5   99.18     -.3   99.38       0   99.38       2   97.88
     3.5   97.88     5.5   99.38     6.3   99.68     6.3   99.88     9.3   99.88
     9.3  100.08    19.3  100.08
#Mann= 3 , 0 , 0
   -10.5    .035       0       0    .035       0     6.3    .035       0
#XS Ineff= 2 , 0
               0     110     6.3             110
Permanent Ineff=
       F       F
#Block Obstruct= 2 , 0
                             6.3
Bank Sta=0,6.3
XS Rating Curve= 0
Exp/Cntr=.3,.1

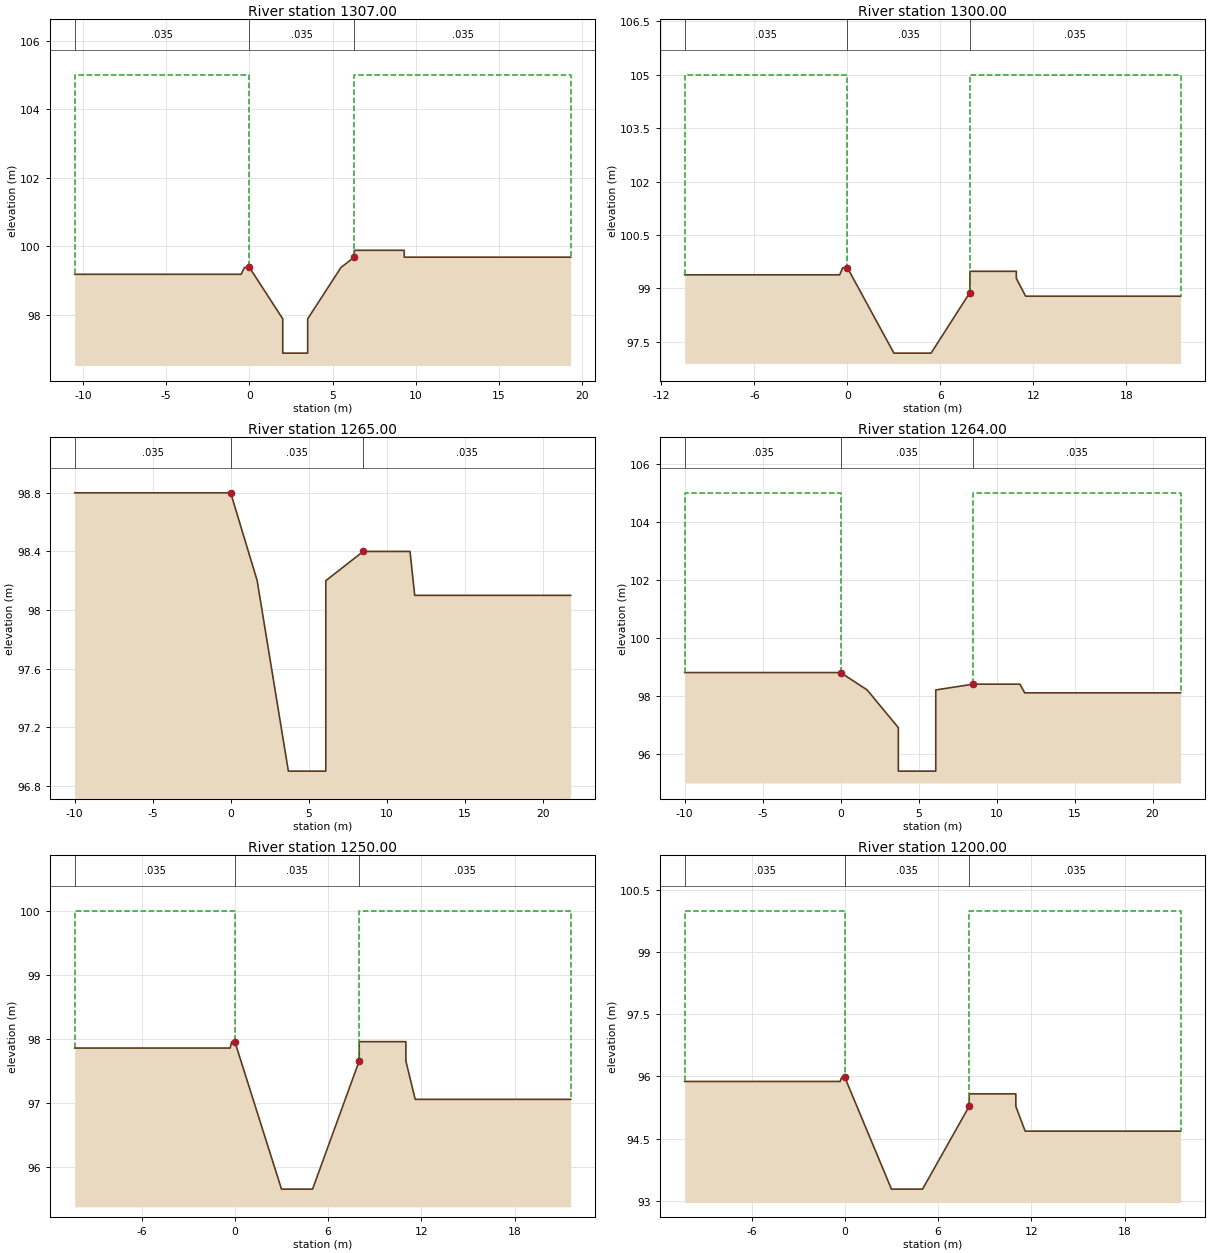
Type RM Length L Ch R = 1 ,1307.00 ,7,7,7
BEGIN DESCRIPTION:
26.007
END DESCRIPTION:
#Sta/Elev= 14
   -10.5   99.18     -.5   99.18     -.3   99.38       0   99.38       2   97.88
       2   96.88     3.5   96.88     3.5   97.88     5.5   99.38     6.3   99.68
     6.3   99.88     9.3   99.88     9.3   99.68    19.3   99.68
#Mann= 3 , 0 , 0
   -10.5    .035       0       0    .035       0     6.3    .035       0
#XS Ineff= 2 , 0
               0     105     6.3             105
Permanent Ineff=
       F       F
#Block Obstruct= 2 , 0
                             6.3
Bank Sta=0,6.3
XS Rating Curve= 0
Exp/Cntr=.3,.1

Type RM Length L Ch R = 1 ,1300.00 ,35,35,35
BEGIN DESCRIPTION:
26
END DESCRIPTION:
#Sta/Elev= 12
   -10.5   99.38     -.5   99.38     -.3   99.58       0   99.58       3   97.18
     5.4   97.18     7.9   98.88     7.9   99.48    10.9   99.48    10.9   99.28
    11.5   98.78    21.5   98.78
#Mann= 3 , 0 , 0
   -10.5    .035       0       0    .035       0     7.9    .035       0
#XS Ineff= 2 , 0
               0     105     7.9             105
Permanent Ineff=
       F       F
#Block Obstruct= 2 , 0
                             7.9
Bank Sta=0,7.9
XS Rating Curve= 0
Exp/Cntr=.3,.1

Type RM Length L Ch R = 1 ,1265.00 ,1,1,1
BEGIN DESCRIPTION:
25.015
END DESCRIPTION:
#Sta/Elev= 10
     -10    98.8       0    98.8     1.7    98.2     3.7    96.9     6.1    96.9
     6.1    98.2     8.5    98.4    11.5    98.4    11.8    98.1    21.8    98.1
#Mann= 3 , 0 , 0
     -10    .035       0       0    .035       0     8.5    .035       0
#XS Ineff= 2 , 0
               0     105     8.5             105
Permanent Ineff=
       F       F
#Block Obstruct= 2 , 0
                             8.5
Bank Sta=0,8.5
XS Rating Curve= 0
Exp/Cntr=.3,.1

Type RM Length L Ch R = 1 ,1264.00 ,14,14,14
BEGIN DESCRIPTION:
25.014
END DESCRIPTION:
#Sta/Elev= 12
     -10    98.8       0    98.8     1.7    98.2     3.7    96.9     3.7    95.4
     6.1    95.4     6.1    96.9     6.1    98.2     8.5    98.4    11.5    98.4
    11.8    98.1    21.8    98.1
#Mann= 3 , 0 , 0
     -10    .035       0       0    .035       0     8.5    .035       0
#XS Ineff= 2 , 0
               0     105     8.5             105
Permanent Ineff=
       F       F
#Block Obstruct= 2 , 0
                             8.5
Bank Sta=0,8.5
XS Rating Curve= 0
Exp/Cntr=.3,.1

Type RM Length L Ch R = 1 ,1250.00 ,50,50,50
BEGIN DESCRIPTION:
25
END DESCRIPTION:
#Sta/Elev= 12
   -10.3   97.86     -.3   97.86     -.2   97.96       0   97.96       3   95.66
       5   95.66       8   97.66       8   97.96      11   97.96      11   97.66
    11.6   97.06    21.6   97.06
#Mann= 3 , 0 , 0
   -10.3    .035       0       0    .035       0       8    .035       0
#XS Ineff= 2 , 0
               0     100       8             100
Permanent Ineff=
       F       F
#Block Obstruct= 2 , 0
                               8
Bank Sta=0,8
XS Rating Curve= 0
Exp/Cntr=.3,.1

Type RM Length L Ch R = 1 ,1200.00 ,50,50,50
BEGIN DESCRIPTION:
24
END DESCRIPTION:
#Sta/Elev= 12
   -10.3   95.88     -.3   95.88     -.2   95.98       0   95.98       3   93.28
       5   93.28       8   95.28       8   95.58      11   95.58      11   95.28
    11.6   94.68    21.6   94.68
#Mann= 3 , 0 , 0
   -10.3    .035       0       0    .035       0       8    .035       0
#XS Ineff= 2 , 0
               0     100       8             100
Permanent Ineff=
       F       F
#Block Obstruct= 2 , 0
                               8
Bank Sta=0,8
XS Rating Curve= 0
Exp/Cntr=.3,.1

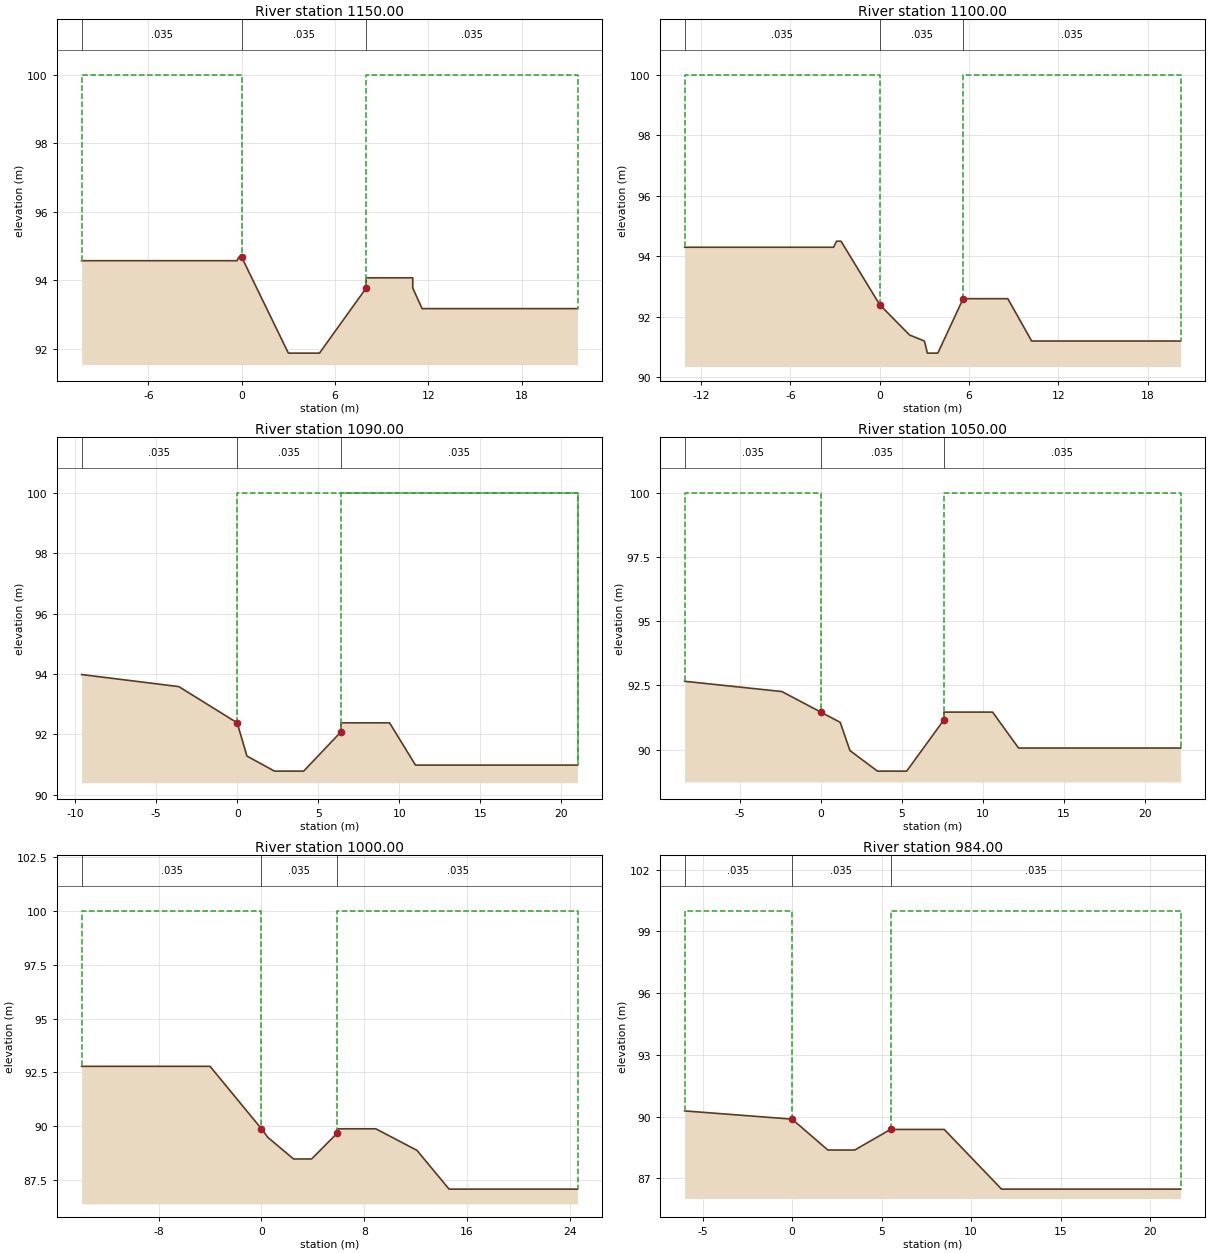
Type RM Length L Ch R = 1 ,1150.00 ,50,50,50
BEGIN DESCRIPTION:
23
END DESCRIPTION:
#Sta/Elev= 12
   -10.3   94.57     -.3   94.57     -.2   94.67       0   94.67       3   91.87
       5   91.87       8   93.77       8   94.07      11   94.07      11   93.77
    11.6   93.17    21.6   93.17
#Mann= 3 , 0 , 0
   -10.3    .035       0       0    .035       0       8    .035       0
#XS Ineff= 2 , 0
               0     100       8             100
Permanent Ineff=
       F       F
#Block Obstruct= 2 , 0
                               8
Bank Sta=0,8
XS Rating Curve= 0
Exp/Cntr=.3,.1

Type RM Length L Ch R = 1 ,1100.00 ,10,10,10
BEGIN DESCRIPTION:
22
END DESCRIPTION:
#Sta/Elev= 13
   -13.1    94.3    -3.1    94.3    -2.9    94.5    -2.6    94.5       0    92.4
       2    91.4       3    91.2     3.2    90.8     3.9    90.8     5.6    92.6
     8.6    92.6    10.2    91.2    20.2    91.2
#Mann= 3 , 0 , 0
   -13.1    .035       0       0    .035       0     5.6    .035       0
#XS Ineff= 2 , 0
               0     100     5.6             100
Permanent Ineff=
       F       F
#Block Obstruct= 2 , 0
                             5.6
Bank Sta=0,5.6
XS Rating Curve= 0
Exp/Cntr=.3,.1

Type RM Length L Ch R = 1 ,1090.00 ,40,40,40
BEGIN DESCRIPTION:
21.04
END DESCRIPTION:
#Sta/Elev= 12
    -9.6   93.98    -6.6   93.78    -3.6   93.58       0   92.38      .6   91.28
     2.3   90.78     4.1   90.78     6.4   92.08     6.4   92.38     9.4   92.38
      11   90.98      21   90.98
#Mann= 3 , 0 , 0
    -9.6    .035       0       0    .035       0     6.4    .035       0
#XS Ineff= 2 , 0
       0       0     100     6.4       0     100
Permanent Ineff=
       F       F
#Block Obstruct= 2 , 0
                             6.4
Bank Sta=0,6.4
XS Rating Curve= 0
Exp/Cntr=.3,.1

Type RM Length L Ch R = 1 ,1050.00 ,50,50,50
BEGIN DESCRIPTION:
21
END DESCRIPTION:
#Sta/Elev= 13
    -8.4   92.66    -5.4   92.46    -2.4   92.26       0   91.46     1.2   91.06
     1.8   89.96     3.5   89.16     5.3   89.16     7.6   91.16     7.6   91.46
    10.6   91.46    12.2   90.06    22.2   90.06
#Mann= 3 , 0 , 0
    -8.4    .035       0       0    .035       0     7.6    .035       0
#XS Ineff= 2 , 0
               0     100     7.6             100
Permanent Ineff=
       F       F
#Block Obstruct= 2 , 0
                             7.6
Bank Sta=0,7.6
XS Rating Curve= 0
Exp/Cntr=.3,.1

Type RM Length L Ch R = 1 ,1000.00 ,16,16,16
BEGIN DESCRIPTION:
20
END DESCRIPTION:
#Sta/Elev= 12
     -14   92.78      -4   92.78       0   89.88      .5   89.48     2.5   88.48
     3.9   88.48     5.9   89.68     5.9   89.88     8.9   89.88    12.1   88.88
    14.6   87.08    24.6   87.08
#Mann= 3 , 0 , 0
     -14    .035       0       0    .035       0     5.9    .035       0
#XS Ineff= 2 , 0
               0     100     5.9             100
Permanent Ineff=
       F       F
#Block Obstruct= 2 , 0
                             5.9
Bank Sta=0,5.9
XS Rating Curve= 0
Exp/Cntr=.3,.1

Type RM Length L Ch R = 1 ,984.00  ,1,1,1
BEGIN DESCRIPTION:
19.034
END DESCRIPTION:
#Sta/Elev= 9
      -6   90.28      -3   90.08       0   89.88       2   88.38     3.5   88.38
     5.5   89.38     8.5   89.38    11.7   86.48    21.7   86.48
#Mann= 3 , 0 , 0
      -6    .035       0       0    .035       0     5.5    .035       0
#XS Ineff= 2 , 0
               0     100     5.5             100
Permanent Ineff=
       F       F
#Block Obstruct= 2 , 0
                             5.5
Bank Sta=0,5.5
XS Rating Curve= 0
Exp/Cntr=.3,.1