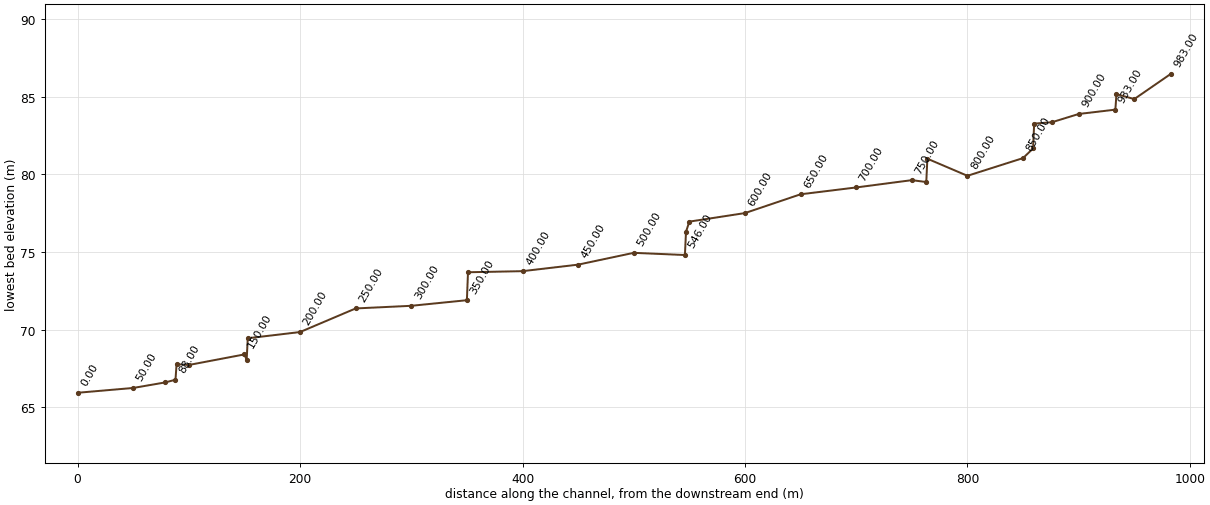
HEC-RAS study MDC.prj: MYUNGDAE

--- MDC.g01 (geometry) --- (continued)

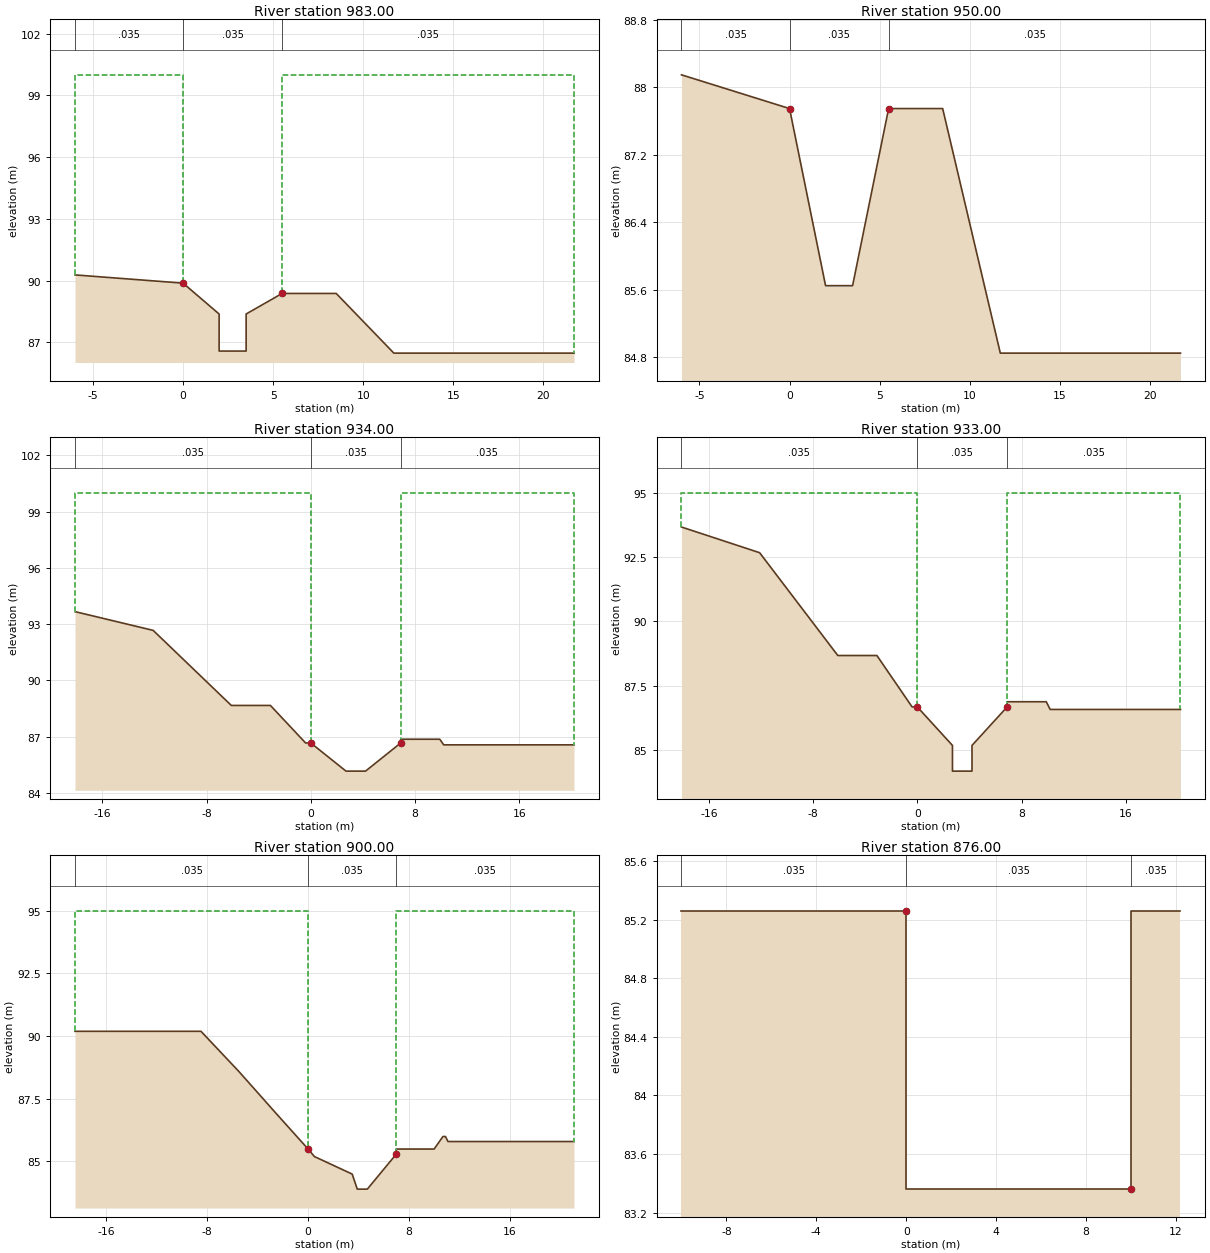
Type RM Length L Ch R = 1 ,983.00  ,33,33,33
BEGIN DESCRIPTION:
19.033
END DESCRIPTION:
#Sta/Elev= 11
      -6   90.28      -3   90.08       0   89.88       2   88.38       2   86.58
     3.5   86.58     3.5   88.38     5.5   89.38     8.5   89.38    11.7   86.48
    21.7   86.48
#Mann= 3 , 0 , 0
      -6    .035       0       0    .035       0     5.5    .035       0
#XS Ineff= 2 , 0
               0     100     5.5             100
Permanent Ineff=
       F       F
#Block Obstruct= 2 , 0
                             5.5
Bank Sta=0,5.5
XS Rating Curve= 0
Exp/Cntr=.3,.1

Type RM Length L Ch R = 1 ,950.00  ,16,16,16
BEGIN DESCRIPTION:
19
END DESCRIPTION:
#Sta/Elev= 9
      -6   88.15      -3   87.95       0   87.75       2   85.65     3.5   85.65
     5.5   87.75     8.5   87.75    11.7   84.85    21.7   84.85
#Mann= 3 , 0 , 0
      -6    .035       0       0    .035       0     5.5    .035       0
#XS Ineff= 2 , 0
               0     100     5.5             100
Permanent Ineff=
       F       F
#Block Obstruct= 2 , 0
                             5.5
Bank Sta=0,5.5
XS Rating Curve= 0
Exp/Cntr=.3,.1

Type RM Length L Ch R = 1 ,934.00  ,1,1,1
BEGIN DESCRIPTION:
18.034
END DESCRIPTION:
#Sta/Elev= 15
   -18.1   93.67   -15.1   93.17   -12.1   92.67    -9.1   90.67    -6.1   88.67
    -3.1   88.67     -.4   86.67       0   86.67     2.7   85.17     4.2   85.17
     6.9   86.67     6.9   86.87     9.9   86.87    10.2   86.57    20.2   86.57
#Mann= 3 , 0 , 0
   -18.1    .035       0       0    .035       0     6.9    .035       0
#XS Ineff= 2 , 0
               0     100     6.9             100
Permanent Ineff=
       F       F
#Block Obstruct= 2 , 0
                             6.9
Bank Sta=0,6.9
XS Rating Curve= 0
Exp/Cntr=.3,.1

Type RM Length L Ch R = 1 ,933.00  ,33,33,33
BEGIN DESCRIPTION:
18.033
END DESCRIPTION:
#Sta/Elev= 17
   -18.1   93.67   -15.1   93.17   -12.1   92.67    -9.1   90.67    -6.1   88.67
    -3.1   88.67     -.4   86.67       0   86.67     2.7   85.17     2.7   84.17
     4.2   84.17     4.2   85.17     6.9   86.67     6.9   86.87     9.9   86.87
    10.2   86.57    20.2   86.57
#Mann= 3 , 0 , 0
   -18.1    .035       0       0    .035       0     6.9    .035       0
#XS Ineff= 2 , 0
               0      95     6.9              95
Permanent Ineff=
       F       F
#Block Obstruct= 2 , 0
                             6.9
Bank Sta=0,6.9
XS Rating Curve= 0
Exp/Cntr=.3,.1

Type RM Length L Ch R = 1 ,900.00  ,24,24,24
BEGIN DESCRIPTION:
18
END DESCRIPTION:
#Sta/Elev= 16
   -18.5   90.19    -8.5   90.19    -5.5   88.59    -2.5   86.89       0   85.49
      .5   85.19     3.5   84.49     3.9   83.89     4.7   83.89       7   85.29
       7   85.49      10   85.49    10.7   85.99    10.9   85.99    11.1   85.79
    21.1   85.79
#Mann= 3 , 0 , 0
   -18.5    .035       0       0    .035       0       7    .035       0
#XS Ineff= 2 , 0
               0      95       7              95
Permanent Ineff=
       F       F
#Block Obstruct= 2 , 0
                               7
Bank Sta=0,7
XS Rating Curve= 0
Exp/Cntr=.3,.1

Type RM Length L Ch R = 1 ,876.00  ,16,16,16
BEGIN DESCRIPTION:
17.026
END DESCRIPTION:
#Sta/Elev= 6
     -10   85.26       0   85.26       0   83.36      10   83.36      10   85.26
    12.2   85.26
#Mann= 3 , 0 , 0
     -10    .035       0       0    .035       0      10    .035       0
#XS Ineff= 2 , 0
       0       0      95      10       0      95
Permanent Ineff=
       F       F
#Block Obstruct= 2 , 0
       0                      10       0
Bank Sta=0,10
XS Rating Curve= 0
Exp/Cntr=.3,.1

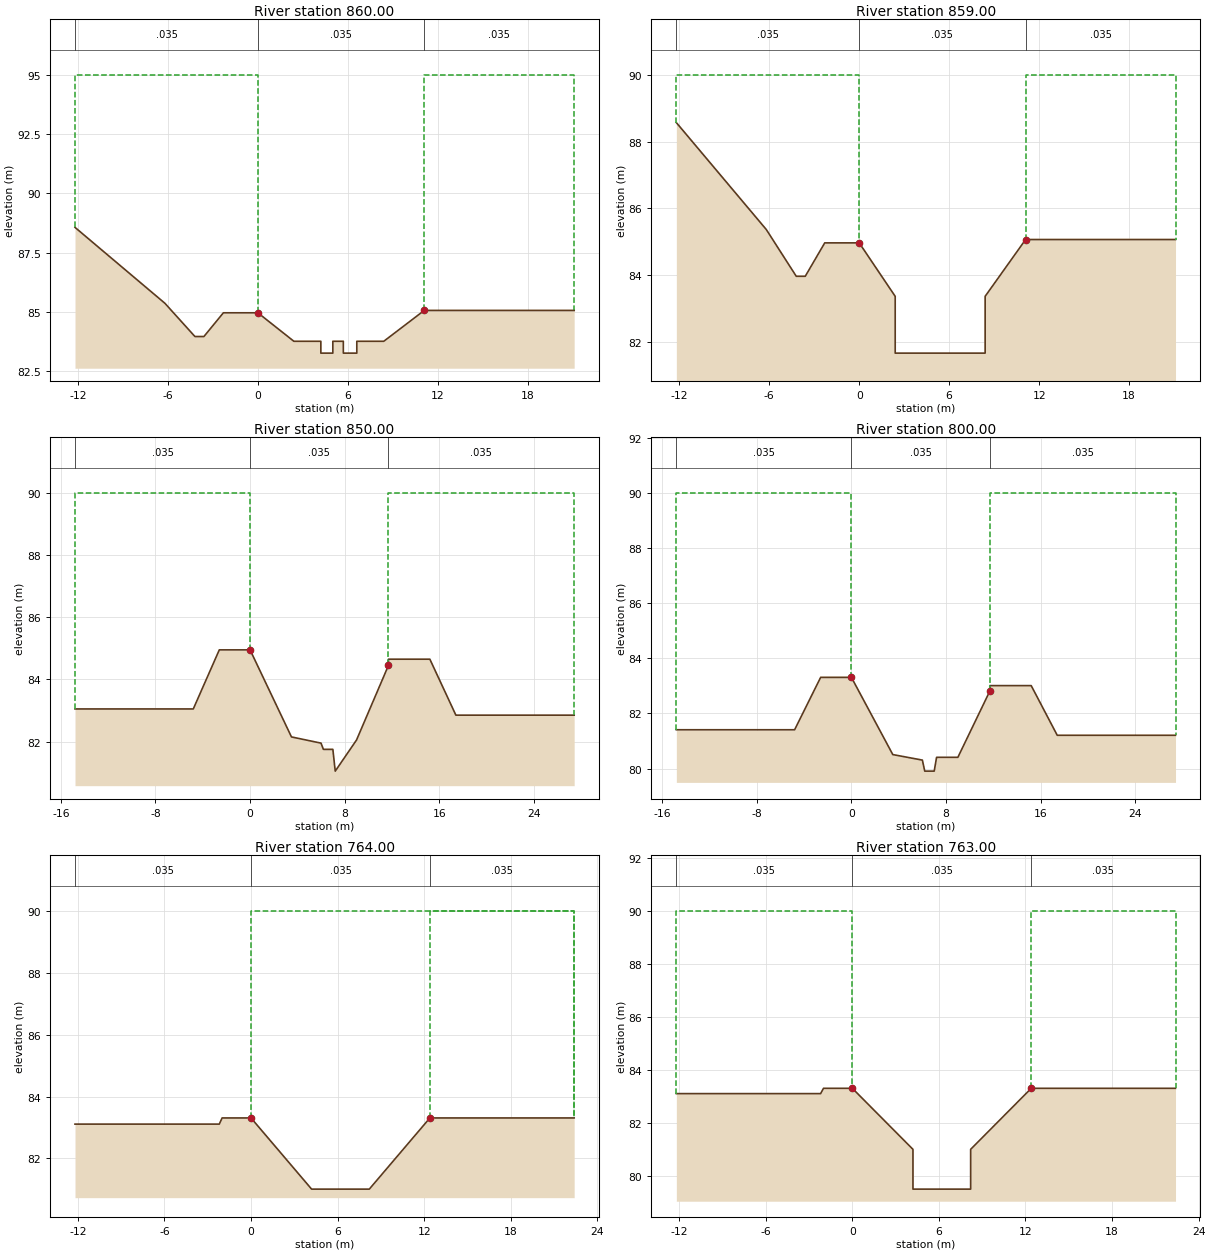
Type RM Length L Ch R = 1 ,860.00  ,1,1,1
BEGIN DESCRIPTION:
17.01
END DESCRIPTION:
#Sta/Elev= 19
   -12.2   88.57    -9.2   86.97    -6.2   85.37    -4.2   83.97    -3.6   83.97
    -2.3   84.97       0   84.97     2.4   83.77     4.2   83.77     4.2   83.27
       5   83.27       5   83.77     5.7   83.77     5.7   83.27     6.6   83.27
     6.6   83.77     8.4   83.77    11.1   85.07    21.1   85.07
#Mann= 3 , 0 , 0
   -12.2    .035       0       0    .035       0    11.1    .035       0
#XS Ineff= 2 , 0
               0      95    11.1              95
Permanent Ineff=
       F       F
#Block Obstruct= 2 , 0
                            11.1
Bank Sta=0,11.1
XS Rating Curve= 0
Exp/Cntr=.3,.1

Type RM Length L Ch R = 1 ,859.00  ,9,9,9
BEGIN DESCRIPTION:
17.009
END DESCRIPTION:
#Sta/Elev= 13
   -12.2   88.57    -9.2   86.97    -6.2   85.37    -4.2   83.97    -3.6   83.97
    -2.3   84.97       0   84.97     2.4   83.37     2.4   81.67     8.4   81.67
     8.4   83.37    11.1   85.07    21.1   85.07
#Mann= 3 , 0 , 0
   -12.2    .035       0       0    .035       0    11.1    .035       0
#XS Ineff= 2 , 0
               0      90    11.1              90
Permanent Ineff=
       F       F
#Block Obstruct= 2 , 0
                            11.1
Bank Sta=0,11.1
XS Rating Curve= 0
Exp/Cntr=.3,.1

Type RM Length L Ch R = 1 ,850.00  ,50,50,50
BEGIN DESCRIPTION:
17
END DESCRIPTION:
#Sta/Elev= 15
   -14.8   83.05    -4.8   83.05    -2.6   84.95       0   84.95     3.5   82.15
       6   81.95     6.2   81.75       7   81.75     7.2   81.05       9   82.05
    11.7   84.45    11.7   84.65    15.2   84.65    17.4   82.85    27.4   82.85
#Mann= 3 , 0 , 0
   -14.8    .035       0       0    .035       0    11.7    .035       0
#XS Ineff= 2 , 0
               0      90    11.7              90
Permanent Ineff=
       F       F
#Block Obstruct= 2 , 0
                            11.7
Bank Sta=0,11.7
XS Rating Curve= 0
Exp/Cntr=.3,.1

Type RM Length L Ch R = 1 ,800.00  ,36,36,36
BEGIN DESCRIPTION:
16
END DESCRIPTION:
#Sta/Elev= 15
   -14.8   81.41    -4.8   81.41    -2.6   83.31       0   83.31     3.5   80.51
       6   80.31     6.2   79.91       7   79.91     7.2   80.41       9   80.41
    11.7   82.81    11.7   83.01    15.2   83.01    17.4   81.21    27.4   81.21
#Mann= 3 , 0 , 0
   -14.8    .035       0       0    .035       0    11.7    .035       0
#XS Ineff= 2 , 0
               0      90    11.7              90
Permanent Ineff=
       F       F
#Block Obstruct= 2 , 0
                            11.7
Bank Sta=0,11.7
XS Rating Curve= 0
Exp/Cntr=.3,.1

Type RM Length L Ch R = 1 ,764.00  ,1,1,1
BEGIN DESCRIPTION:
15.014
END DESCRIPTION:
#Sta/Elev= 8
   -12.2   83.11    -2.2   83.11      -2   83.31       0   83.31     4.2   81.01
     8.2   81.01    12.4   83.31    22.4   83.31
#Mann= 3 , 0 , 0
   -12.2    .035       0       0    .035       0    12.4    .035       0
#XS Ineff= 2 , 0
       0       0      90    12.4       0      90
Permanent Ineff=
       F       F
#Block Obstruct= 2 , 0
                            12.4
Bank Sta=0,12.4
XS Rating Curve= 0
Exp/Cntr=.3,.1

Type RM Length L Ch R = 1 ,763.00  ,13,13,13
BEGIN DESCRIPTION:
15.013
END DESCRIPTION:
#Sta/Elev= 10
   -12.2   83.11    -2.2   83.11      -2   83.31       0   83.31     4.2   81.01
     4.2   79.51     8.2   79.51     8.2   81.01    12.4   83.31    22.4   83.31
#Mann= 3 , 0 , 0
   -12.2    .035       0       0    .035       0    12.4    .035       0
#XS Ineff= 2 , 0
               0      90    12.4              90
Permanent Ineff=
       F       F
#Block Obstruct= 2 , 0
                            12.4
Bank Sta=0,12.4
XS Rating Curve= 0
Exp/Cntr=.3,.1

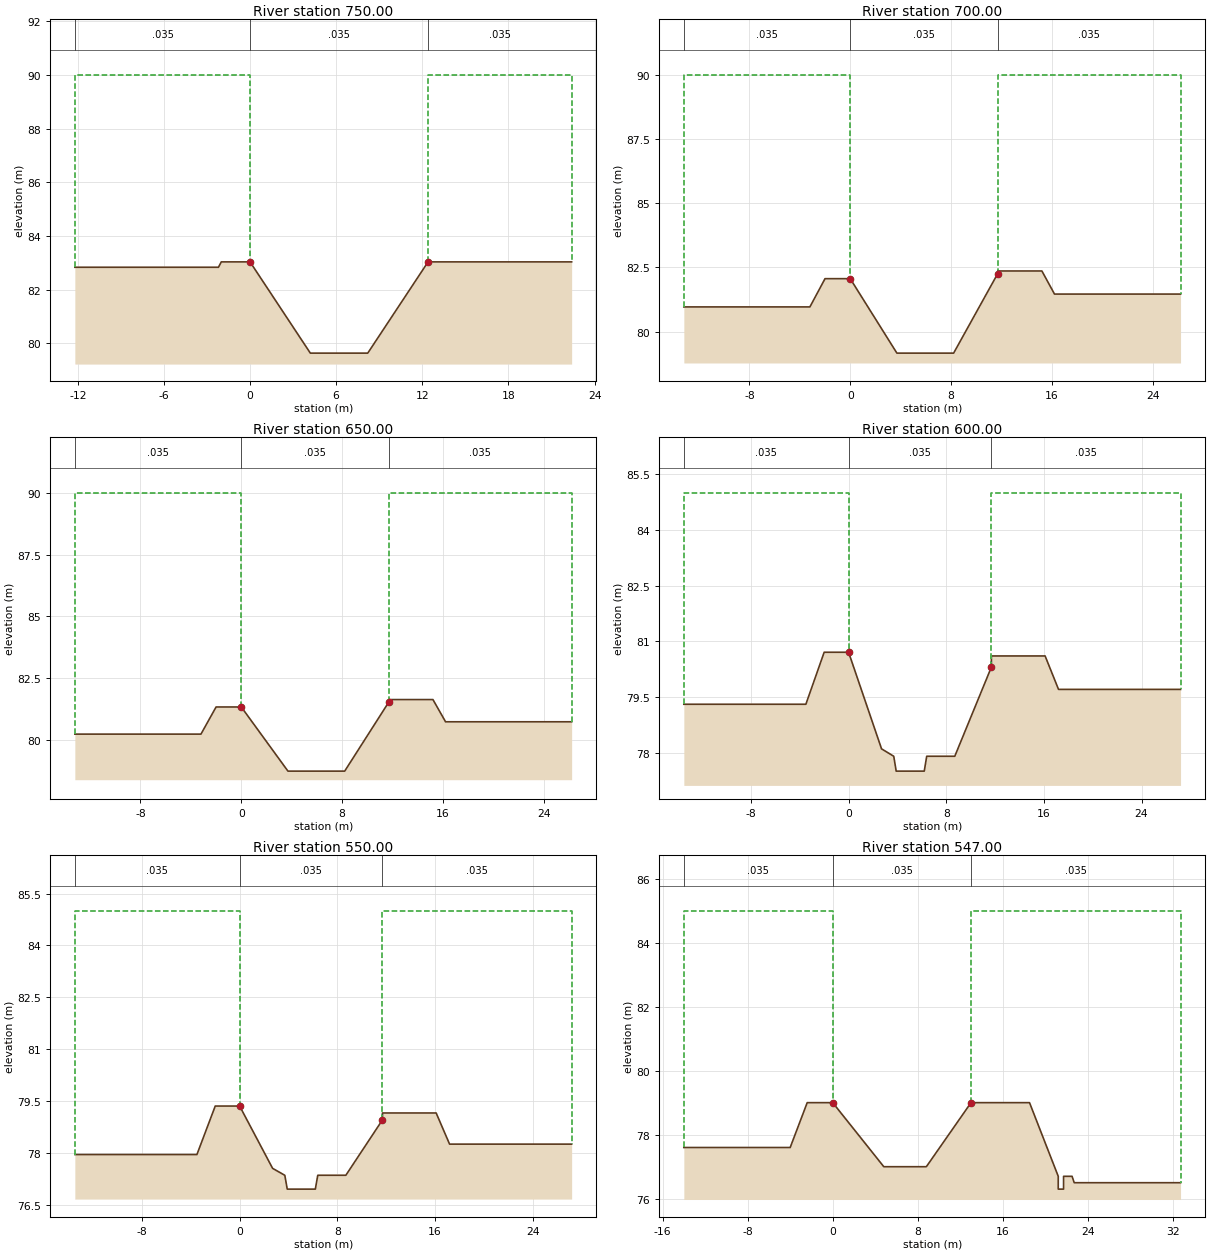
Type RM Length L Ch R = 1 ,750.00  ,50,50,50
BEGIN DESCRIPTION:
15
END DESCRIPTION:
#Sta/Elev= 8
   -12.2   82.83    -2.2   82.83      -2   83.03       0   83.03     4.2   79.63
     8.2   79.63    12.4   83.03    22.4   83.03
#Mann= 3 , 0 , 0
   -12.2    .035       0       0    .035       0    12.4    .035       0
#XS Ineff= 2 , 0
               0      90    12.4              90
Permanent Ineff=
       F       F
#Block Obstruct= 2 , 0
                            12.4
Bank Sta=0,12.4
XS Rating Curve= 0
Exp/Cntr=.3,.1

Type RM Length L Ch R = 1 ,700.00  ,50,50,50
BEGIN DESCRIPTION:
14
END DESCRIPTION:
#Sta/Elev= 11
   -13.2   80.96    -3.2   80.96      -2   82.06       0   82.06     3.7   79.16
     8.2   79.16    11.7   82.26    11.7   82.36    15.2   82.36    16.2   81.46
    26.2   81.46
#Mann= 3 , 0 , 0
   -13.2    .035       0       0    .035       0    11.7    .035       0
#XS Ineff= 2 , 0
               0      90    11.7              90
Permanent Ineff=
       F       F
#Block Obstruct= 2 , 0
                            11.7
Bank Sta=0,11.7
XS Rating Curve= 0
Exp/Cntr=.3,.1

Type RM Length L Ch R = 1 ,650.00  ,50,50,50
BEGIN DESCRIPTION:
13
END DESCRIPTION:
#Sta/Elev= 11
   -13.2   80.22    -3.2   80.22      -2   81.32       0   81.32     3.7   78.72
     8.2   78.72    11.7   81.52    11.7   81.62    15.2   81.62    16.2   80.72
    26.2   80.72
#Mann= 3 , 0 , 0
   -13.2    .035       0       0    .035       0    11.7    .035       0
#XS Ineff= 2 , 0
               0      90    11.7              90
Permanent Ineff=
       F       F
#Block Obstruct= 2 , 0
                            11.7
Bank Sta=0,11.7
XS Rating Curve= 0
Exp/Cntr=.3,.1

Type RM Length L Ch R = 1 ,600.00  ,50,50,50
BEGIN DESCRIPTION:
12
END DESCRIPTION:
#Sta/Elev= 16
   -13.5   79.31    -3.5   79.31      -2   80.71       0   80.71     2.7   78.11
     3.7   77.91     3.9   77.51     6.2   77.51     6.4   77.91     8.7   77.91
    11.7   80.31    11.7   80.61    15.2   80.61    16.1   80.61    17.2   79.71
    27.2   79.71
#Mann= 3 , 0 , 0
   -13.5    .035       0       0    .035       0    11.7    .035       0
#XS Ineff= 2 , 0
               0      85    11.7              85
Permanent Ineff=
       F       F
#Block Obstruct= 2 , 0
                            11.7
Bank Sta=0,11.7
XS Rating Curve= 0
Exp/Cntr=.3,.1

Type RM Length L Ch R = 1 ,550.00  ,3,3,3
BEGIN DESCRIPTION:
11
END DESCRIPTION:
#Sta/Elev= 16
   -13.5   77.96    -3.5   77.96      -2   79.36       0   79.36     2.7   77.56
     3.7   77.36     3.9   76.96     6.2   76.96     6.4   77.36     8.7   77.36
    11.7   78.96    11.7   79.16    15.2   79.16    16.1   79.16    17.2   78.26
    27.2   78.26
#Mann= 3 , 0 , 0
   -13.5    .035       0       0    .035       0    11.7    .035       0
#XS Ineff= 2 , 0
               0      85    11.7              85
Permanent Ineff=
       F       F
#Block Obstruct= 2 , 0
                            11.7
Bank Sta=0,11.7
XS Rating Curve= 0
Exp/Cntr=.3,.1

Type RM Length L Ch R = 1 ,547.00  ,1,1,1
BEGIN DESCRIPTION:
10.047
END DESCRIPTION:
#Sta/Elev= 16
     -14   77.61      -4   77.61    -2.4   79.01       0   79.01     4.8   77.01
     8.8   77.01      13   79.01    17.5   79.01    18.5   79.01    21.2   76.71
    21.2   76.31    21.7   76.31    21.7   76.71    22.5   76.71    22.7   76.51
    32.7   76.51
#Mann= 3 , 0 , 0
     -14    .035       0       0    .035       0      13    .035       0
#XS Ineff= 2 , 0
               0      85      13              85
Permanent Ineff=
       F       F
#Block Obstruct= 2 , 0
                              13
Bank Sta=0,13
XS Rating Curve= 0
Exp/Cntr=.3,.1

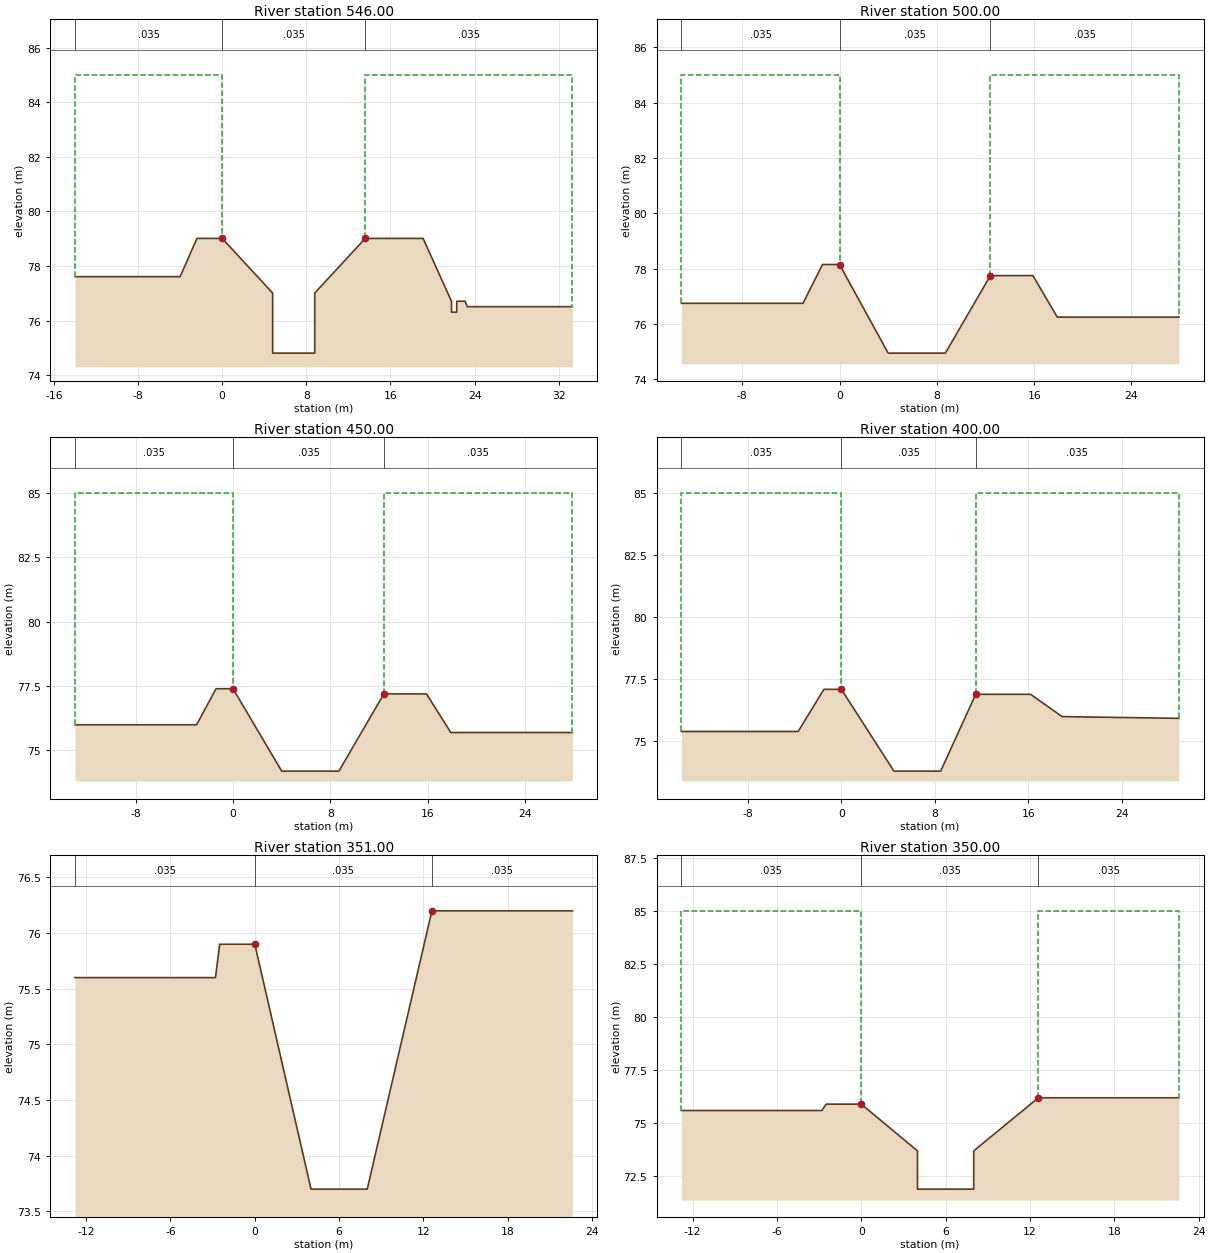
Type RM Length L Ch R = 1 ,546.00  ,46,46,46
BEGIN DESCRIPTION:
10.046
END DESCRIPTION:
#Sta/Elev= 18
     -14   77.61      -4   77.61    -2.4   79.01       0   79.01     4.8   77.01
     4.8   74.81     8.8   74.81     8.8   77.01    13.6   79.01    18.1   79.01
    19.1   79.01    21.8   76.71    21.8   76.31    22.3   76.31    22.3   76.71
    23.1   76.71    23.3   76.51    33.3   76.51
#Mann= 3 , 0 , 0
     -14    .035       0       0    .035       0    13.6    .035       0
#XS Ineff= 2 , 0
               0      85    13.6              85
Permanent Ineff=
       F       F
#Block Obstruct= 2 , 0
                            13.6
Bank Sta=0,13.6
XS Rating Curve= 0
Exp/Cntr=.3,.1

Type RM Length L Ch R = 1 ,500.00  ,50,50,50
BEGIN DESCRIPTION:
10
END DESCRIPTION:
#Sta/Elev= 10
     -13   76.75      -3   76.75    -1.4   78.15       0   78.15       4   74.95
     8.7   74.95    12.4   77.75    15.9   77.75    17.9   76.25    27.9   76.25
#Mann= 3 , 0 , 0
     -13    .035       0       0    .035       0    12.4    .035       0
#XS Ineff= 2 , 0
               0      85    12.4              85
Permanent Ineff=
       F       F
#Block Obstruct= 2 , 0
                            12.4
Bank Sta=0,12.4
XS Rating Curve= 0
Exp/Cntr=.3,.1

Type RM Length L Ch R = 1 ,450.00  ,50,50,50
BEGIN DESCRIPTION:
9
END DESCRIPTION:
#Sta/Elev= 10
     -13   75.99      -3   75.99    -1.4   77.39       0   77.39       4   74.19
     8.7   74.19    12.4   77.19    15.9   77.19    17.9   75.69    27.9   75.69
#Mann= 3 , 0 , 0
     -13    .035       0       0    .035       0    12.4    .035       0
#XS Ineff= 2 , 0
               0      85    12.4              85
Permanent Ineff=
       F       F
#Block Obstruct= 2 , 0
                            12.4
Bank Sta=0,12.4
XS Rating Curve= 0
Exp/Cntr=.3,.1

Type RM Length L Ch R = 1 ,400.00  ,49,49,49
BEGIN DESCRIPTION:
8
END DESCRIPTION:
#Sta/Elev= 12
   -13.7   75.37    -3.7   75.37    -1.5   77.07       0   77.07     4.5   73.77
     8.5   73.77    11.5   76.87      12   76.87      15   76.87    16.2   76.87
    18.9   75.97    28.9    75.9
#Mann= 3 , 0 , 0
   -13.7    .035       0       0    .035       0    11.5    .035       0
#XS Ineff= 2 , 0
               0      85    11.5              85
Permanent Ineff=
       F       F
#Block Obstruct= 2 , 0
                            11.5
Bank Sta=0,11.5
XS Rating Curve= 0
Exp/Cntr=.3,.1

Type RM Length L Ch R = 1 ,351.00  ,1,1,1
BEGIN DESCRIPTION:
7.001
END DESCRIPTION:
#Sta/Elev= 8
   -12.8    75.6    -2.8    75.6    -2.5    75.9       0    75.9       4    73.7
       8    73.7    12.6    76.2    22.6    76.2
#Mann= 3 , 0 , 0
   -12.8    .035       0       0    .035       0    12.6    .035       0
#XS Ineff= 2 , 0
               0      85    12.6              85
Permanent Ineff=
       F       F
#Block Obstruct= 2 , 0
                            12.6
Bank Sta=0,12.6
XS Rating Curve= 0
Exp/Cntr=.3,.1

Type RM Length L Ch R = 1 ,350.00  ,50,50,50
BEGIN DESCRIPTION:
7
END DESCRIPTION:
#Sta/Elev= 10
   -12.8    75.6    -2.8    75.6    -2.5    75.9       0    75.9       4    73.7
       4    71.9       8    71.9       8    73.7    12.6    76.2    22.6    76.2
#Mann= 3 , 0 , 0
   -12.8    .035       0       0    .035       0    12.6    .035       0
#XS Ineff= 2 , 0
               0      85    12.6              85
Permanent Ineff=
       F       F
#Block Obstruct= 2 , 0
                            12.6
Bank Sta=0,12.6
XS Rating Curve= 0
Exp/Cntr=.3,.1

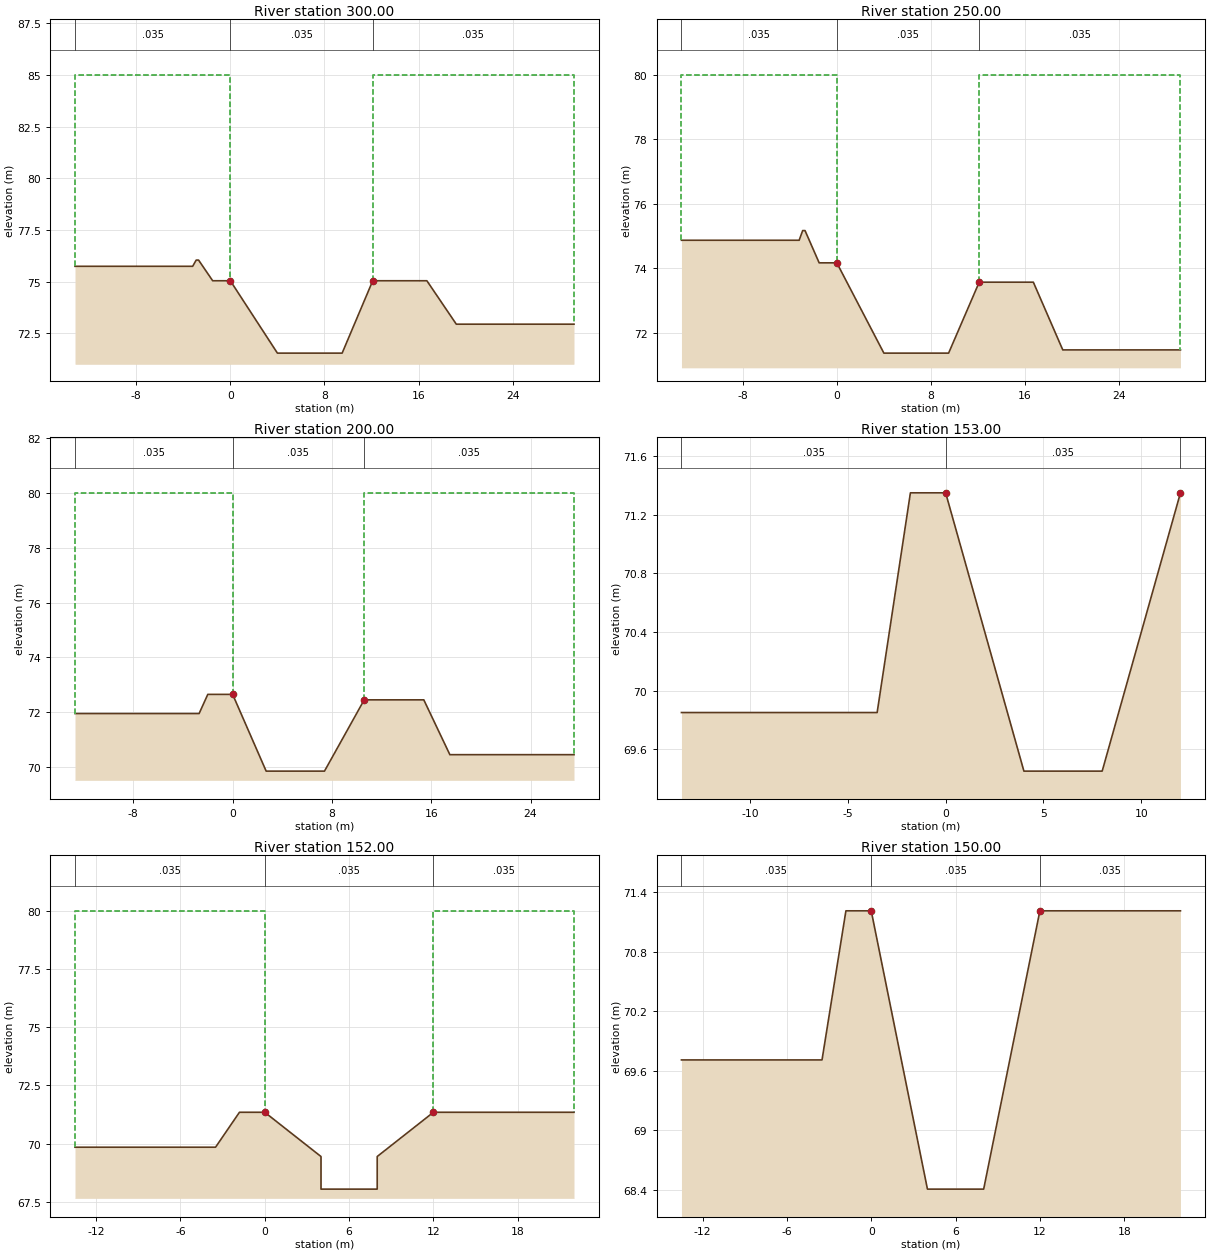
Type RM Length L Ch R = 1 ,300.00  ,50,50,50
BEGIN DESCRIPTION:
6
END DESCRIPTION:
#Sta/Elev= 14
   -13.2   75.74    -3.2   75.74    -2.9   76.04    -2.7   76.04    -1.5   75.04
       0   75.04       4   71.54     9.5   71.54    12.1   75.04    12.9   75.04
    15.9   75.04    16.7   75.04    19.2   72.94    29.2   72.94
#Mann= 3 , 0 , 0
   -13.2    .035       0       0    .035       0    12.1    .035       0
#XS Ineff= 2 , 0
               0      85    12.1              85
Permanent Ineff=
       F       F
#Block Obstruct= 2 , 0
                            12.1
Bank Sta=0,12.1
XS Rating Curve= 0
Exp/Cntr=.3,.1

Type RM Length L Ch R = 1 ,250.00  ,50,50,50
BEGIN DESCRIPTION:
5
END DESCRIPTION:
#Sta/Elev= 14
   -13.2   74.87    -3.2   74.87    -2.9   75.17    -2.7   75.17    -1.5   74.17
       0   74.17       4   71.37     9.5   71.37    12.1   73.57    12.9   73.57
    15.9   73.57    16.7   73.57    19.2   71.47    29.2   71.47
#Mann= 3 , 0 , 0
   -13.2    .035       0       0    .035       0    12.1    .035       0
#XS Ineff= 2 , 0
               0      80    12.1              80
Permanent Ineff=
       F       F
#Block Obstruct= 2 , 0
                            12.1
Bank Sta=0,12.1
XS Rating Curve= 0
Exp/Cntr=.3,.1

Type RM Length L Ch R = 1 ,200.00  ,47,47,47
BEGIN DESCRIPTION:
4
END DESCRIPTION:
#Sta/Elev= 12
   -12.7   71.95    -2.7   71.95      -2   72.65       0   72.65     2.7   69.85
     7.4   69.85    10.6   72.45    11.6   72.45    14.6   72.45    15.4   72.45
    17.5   70.45    27.5   70.45
#Mann= 3 , 0 , 0
   -12.7    .035       0       0    .035       0    10.6    .035       0
#XS Ineff= 2 , 0
               0      80    10.6              80
Permanent Ineff=
       F       F
#Block Obstruct= 2 , 0
                            10.6
Bank Sta=0,10.6
XS Rating Curve= 0
Exp/Cntr=.3,.1

Type RM Length L Ch R = 1 ,153.00  ,1,1,1
BEGIN DESCRIPTION:
3.003
END DESCRIPTION:
#Sta/Elev= 7
   -13.5   69.85    -3.5   69.85    -1.8   71.35       0   71.35       4   69.45
       8   69.45      12   71.35
#Mann= 3 , 0 , 0
   -13.5    .035       0       0    .035       0      12    .035       0
#XS Ineff= 2 , 0
       0       0      80      12       0      80
Permanent Ineff=
       F       F
#Block Obstruct= 2 , 0
                              12
Bank Sta=0,12
XS Rating Curve= 0
Exp/Cntr=.3,.1

Type RM Length L Ch R = 1 ,152.00  ,2,2,2
BEGIN DESCRIPTION:
3.002
END DESCRIPTION:
#Sta/Elev= 10
   -13.5   69.85    -3.5   69.85    -1.8   71.35       0   71.35       4   69.45
       4   68.05       8   68.05       8   69.45      12   71.35      22   71.35
#Mann= 3 , 0 , 0
   -13.5    .035       0       0    .035       0      12    .035       0
#XS Ineff= 2 , 0
               0      80      12              80
Permanent Ineff=
       F       F
#Block Obstruct= 2 , 0
                              12
Bank Sta=0,12
XS Rating Curve= 0
Exp/Cntr=.3,.1

Type RM Length L Ch R = 1 ,150.00  ,50,50,50
BEGIN DESCRIPTION:
3
END DESCRIPTION:
#Sta/Elev= 8
   -13.5   69.71    -3.5   69.71    -1.8   71.21       0   71.21       4   68.41
       8   68.41      12   71.21      22   71.21
#Mann= 3 , 0 , 0
   -13.5    .035       0       0    .035       0      12    .035       0
#XS Ineff= 2 , 0
               0      80      12              80
Permanent Ineff=
       F       F
#Block Obstruct= 2 , 0
                              12
Bank Sta=0,12
XS Rating Curve= 0
Exp/Cntr=.3,.1

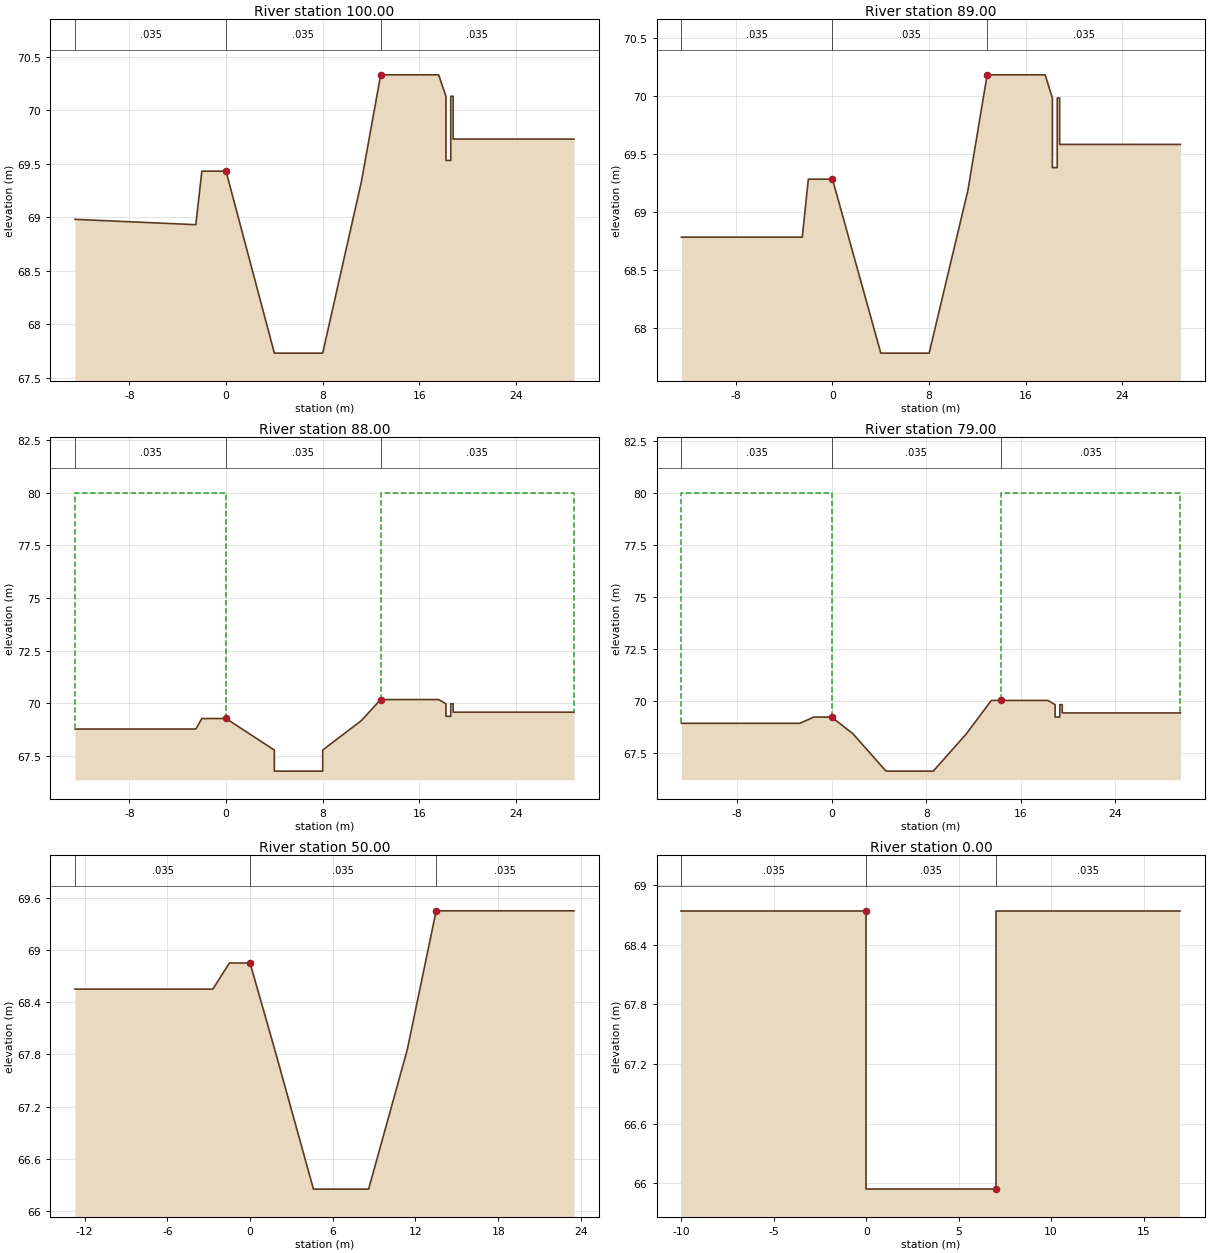
Type RM Length L Ch R = 1 ,100.00  ,11,11,11
BEGIN DESCRIPTION:
2
END DESCRIPTION:
#Sta/Elev= 18
   -12.5   68.98    -2.5   68.93      -2   69.43       0   69.43       4   67.73
       8   67.73    11.2   69.33    12.8   70.33    13.6   70.33    16.6   70.33
    17.6   70.33    18.2   70.13    18.2   69.53    18.6   69.53    18.6   70.13
    18.8   70.13    18.8   69.73    28.8   69.73
#Mann= 3 , 0 , 0
   -12.5    .035       0       0    .035       0    12.8    .035       0
#XS Ineff= 2 , 0
               0      80    12.8              80
Permanent Ineff=
       F       F
#Block Obstruct= 2 , 0
                            12.8
Bank Sta=0,12.8
XS Rating Curve= 0
Exp/Cntr=.3,.1

Type RM Length L Ch R = 1 ,89.00   ,1,1,1
BEGIN DESCRIPTION:
1.039
END DESCRIPTION:
#Sta/Elev= 18
   -12.5   68.78    -2.5   68.78      -2   69.28       0   69.28       4   67.78
       8   67.78    11.2   69.18    12.8   70.18    13.6   70.18    16.6   70.18
    17.6   70.18    18.2   69.98    18.2   69.38    18.6   69.38    18.6   69.98
    18.8   69.98    18.8   69.58    28.8   69.58
#Mann= 3 , 0 , 0
   -12.5    .035       0       0    .035       0    12.8    .035       0
#XS Ineff= 2 , 0
               0      80    12.8              80
Permanent Ineff=
       F       F
#Block Obstruct= 2 , 0
                            12.8
Bank Sta=0,12.8
XS Rating Curve= 0
Exp/Cntr=.3,.1

Type RM Length L Ch R = 1 ,88.00   ,9,9,9
BEGIN DESCRIPTION:
1.038
END DESCRIPTION:
#Sta/Elev= 20
   -12.5   68.78    -2.5   68.78      -2   69.28       0   69.28       4   67.78
       4   66.78       8   66.78       8   67.78    11.2   69.18    12.8   70.18
    13.6   70.18    16.6   70.18    17.6   70.18    18.2   69.98    18.2   69.38
    18.6   69.38    18.6   69.98    18.8   69.98    18.8   69.58    28.8   69.58
#Mann= 3 , 0 , 0
   -12.5    .035       0       0    .035       0    12.8    .035       0
#XS Ineff= 2 , 0
               0      80    12.8              80
Permanent Ineff=
       F       F
#Block Obstruct= 2 , 0
                            12.8
Bank Sta=0,12.8
XS Rating Curve= 0
Exp/Cntr=.3,.1

Type RM Length L Ch R = 1 ,79.00   ,29,29,29
BEGIN DESCRIPTION:
1.029
END DESCRIPTION:
#Sta/Elev= 19
   -12.7   68.91    -2.7   68.91    -1.5   69.21       0   69.21     1.8   68.41
     4.6   66.61     8.6   66.61    11.4   68.41    13.5   70.01    14.3   70.01
    17.3   70.01    18.3   70.01    18.9   69.81    18.9   69.21    19.3   69.21
    19.3   69.81    19.5   69.81    19.5   69.41    29.5   69.41
#Mann= 3 , 0 , 0
   -12.7    .035       0       0    .035       0    14.3    .035       0
#XS Ineff= 2 , 0
               0      80    14.3              80
Permanent Ineff=
       F       F
#Block Obstruct= 2 , 0
                            14.3
Bank Sta=0,14.3
XS Rating Curve= 0
Exp/Cntr=.3,.1

Type RM Length L Ch R = 1 ,50.00   ,50,50,50
BEGIN DESCRIPTION:
1
END DESCRIPTION:
#Sta/Elev= 10
   -12.7   68.55    -2.7   68.55    -1.5   68.85       0   68.85     1.8   67.85
     4.6   66.25     8.6   66.25    11.4   67.85    13.5   69.45    23.5   69.45
#Mann= 3 , 0 , 0
   -12.7    .035       0       0    .035       0    13.5    .035       0
#XS Ineff= 2 , 0
               0      80    13.5              80
Permanent Ineff=
       F       F
#Block Obstruct= 2 , 0
                            13.5
Bank Sta=0,13.5
XS Rating Curve= 0
Exp/Cntr=.3,.1

Type RM Length L Ch R = 1 ,0.00    ,0,0,0
BEGIN DESCRIPTION:
0
END DESCRIPTION:
#Sta/Elev= 6
     -10   68.74       0   68.74       0   65.94       7   65.94       7   68.74
      17   68.74
#Mann= 3 , 0 , 0
     -10    .035       0       0    .035       0       7    .035       0
#XS Ineff= 2 , 0
               0      80       7              80
Permanent Ineff=
       F       F
#Block Obstruct= 2 , 0
                               7
Bank Sta=0,7
XS Rating Curve= 0
Exp/Cntr=.3,.1

Chan Stop Cuts=-1