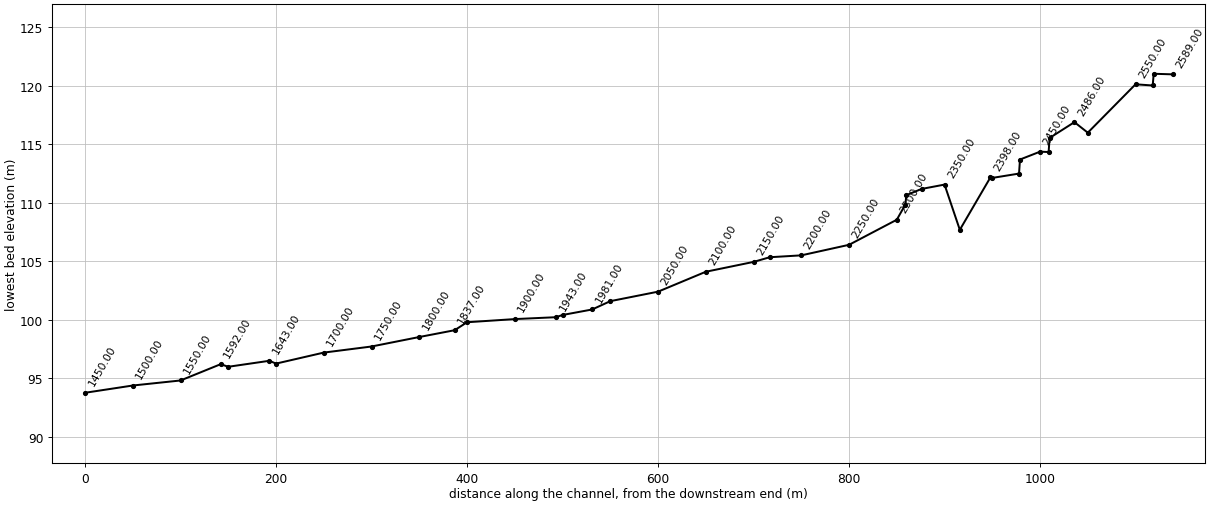
--- SIN.prj (project) ---

Proj Title=SIN
Current Plan=p01
Default Exp/Contr=.3,.1
SI Units
Geom File=g01
Flow File=f01
Plan File=p01
Y Axis Title=Elevation
X Axis Title(PF)=Main Channel Distance
X Axis Title(XS)=Station
BEGIN DESCRIPTION:
           BACK WATER COMPUTATION
      APPLICATION OF HEC-2 BY Samju Construction Engineering
      sinsan-ch: 10,20,30,50,80 yr
END DESCRIPTION:
DSS Export Rating Curves= 0
DSS Export Rating Curve Sorted= 0
DSS Export Volume Flow Curves= 0
DXF OffsetX= 0
DXF OffsetY= 0
DXF ScaleX= 1
DXF ScaleY= 10

--- SIN.p01 (plan) ---

Plan Title=Imported Plan 01
Version=Version 3.0.1  Mar 2001
Short Identifier=Imported Pla
Geom File=g01
Flow File=f01
Subcritical Flow
K Sum by GR= 0
Std Step Tol= 0.003
Critical Tol= 0.003
Num of Std Step Trials= 20
Max Error Tol= 0.1
Flow Tol Ratio= 0.001
Split Flow NTrial= 30
Split Flow Tol= 0.02
Split Flow Ratio= 0.02
Log Output Level= 0
Friction Slope Method= 1
Unsteady Friction Slope Method= 2
Parabolic Critical Depth
Global Vel Dist= 0 , 0 , 0
Global Log Level= 0
CheckData=True
Encroach Param=-1 ,0,0, 0
Computation Interval=1HOUR
Output Interval=1HOUR
Run HTab= 0
Run UNet= 0
Run PostProcess= 0
UNET Theta= 1
UNET ZTol= 0.02
UNET ZSATol= 0.1
UNET MxIter= 20
UNET MaxInSteps= 20
UNET DtIC= 0
UNET DtMin= 0
UNET MaxCRTS= 20
UNET WFStab= 2
UNET SFStab= 1
UNET WFX= 1
UNET SFX= 1
UNET Convert EG Bridges=-1
UNET Use Existing IB Tables=-1
Instantaneous Interval=1HOUR
Write IC File= 0
Write Velocity= 0
Write Detailed= 0

--- SIN.f01 (steady flow) ---

Flow Title=Imported Flow 01
Version=Version 3.0.1  Mar 2001
Number of Profiles= 5
Profile Names=10YR,20YR,30YR,50YR,80YR
River Rch & RM=RIVER-1,Reach-1         ,2589.00
     9.9    10.9   11.48   12.22    12.9
River Rch & RM=RIVER-1,Reach-1         ,2000.00
   21.98   24.22   25.52   27.17   28.69
River Rch & RM=RIVER-1,Reach-1         ,750.00
   28.19   31.07   32.75   34.88   36.83
Boundary for River Rch & Prof#=RIVER-1,Reach-1         , 1
Up Type= 0
Dn Type= 3
Dn Slope=.028
Boundary for River Rch & Prof#=RIVER-1,Reach-1         , 2
Up Type= 0
Dn Type= 3
Dn Slope=.028
Boundary for River Rch & Prof#=RIVER-1,Reach-1         , 3
Up Type= 0
Dn Type= 3
Dn Slope=.028
Boundary for River Rch & Prof#=RIVER-1,Reach-1         , 4
Up Type= 0
Dn Type= 3
Dn Slope=.028
Boundary for River Rch & Prof#=RIVER-1,Reach-1         , 5
Up Type= 0
Dn Type= 3
Dn Slope=.028
DSS Import GetInterval= 0
DSS Import GetPeak= 0
DSS Import FillOption= 0

--- SIN.g01 (geometry) ---

Geom Title=Imported Geom 01
Version=Version 3.0.1  Mar 2001

River Reach=RIVER-1         ,Reach-1
Reach XY= 2
              .5             .95              .5             .05

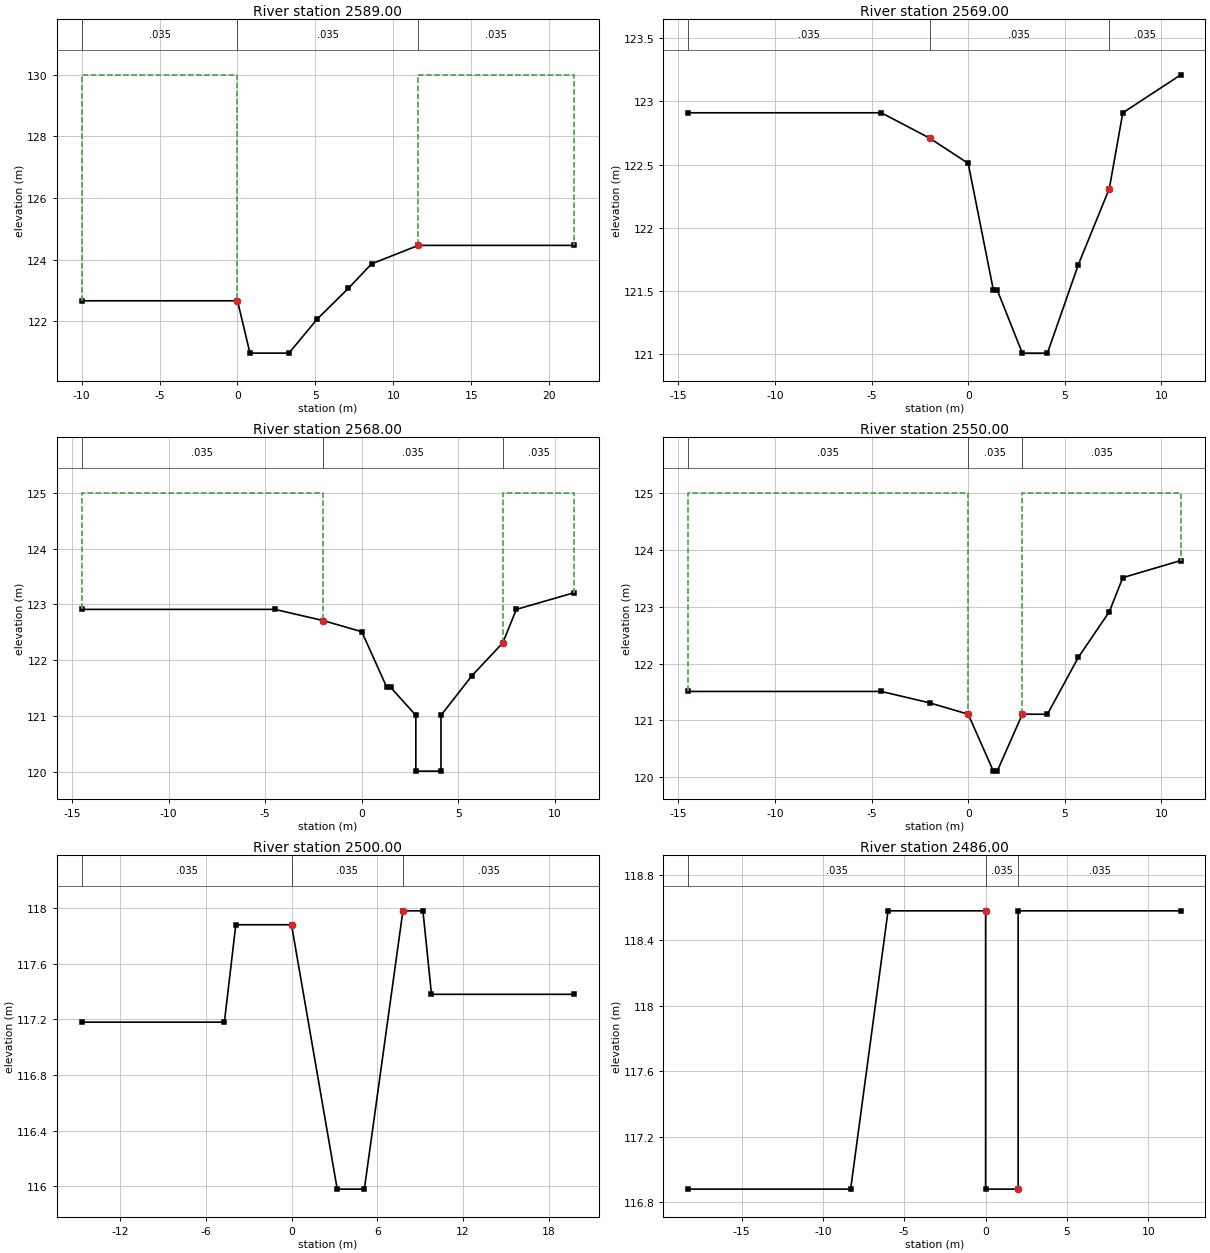
Type RM Length L Ch R = 1 ,2589.00 ,20,20,20
BEGIN DESCRIPTION:
51.02
END DESCRIPTION:
#Sta/Elev= 9
     -10  122.66       0  122.66      .8  120.96     3.3  120.96     5.1  122.06
     7.1  123.06     8.6  123.86    11.6  124.46    21.6  124.46
#Mann= 3 , 0 , 0
     -10    .035       0       0    .035       0    11.6    .035       0
#XS Ineff= 2 , 0
               0     130    11.6             130
Permanent Ineff=
       F       F
#Block Obstruct= 2 , 0
                            11.6
Bank Sta=0,11.6
XS Rating Curve= 0
Exp/Cntr=.3,.1

Type RM Length L Ch R = 1 ,2569.00 ,1,1,1
BEGIN DESCRIPTION:
51.019
END DESCRIPTION:
#Sta/Elev= 12
   -14.5  122.91    -4.5  122.91      -2  122.71       0  122.51     1.3  121.51
     1.5  121.51     2.8  121.01     4.1  121.01     5.7  121.71     7.3  122.31
       8  122.91      11  123.21
#Mann= 3 , 0 , 0
   -14.5    .035       0      -2    .035       0     7.3    .035       0
#XS Ineff= 2 , 0
              -2     130     7.3             130
Permanent Ineff=
       F       F
#Block Obstruct= 2 , 0
                             7.3
Bank Sta=-2,7.3
XS Rating Curve= 0
Exp/Cntr=.3,.1

Type RM Length L Ch R = 1 ,2568.00 ,18,18,18
BEGIN DESCRIPTION:
51.018
END DESCRIPTION:
#Sta/Elev= 14
   -14.5  122.91    -4.5  122.91      -2  122.71       0  122.51     1.3  121.51
     1.5  121.51     2.8  121.01     2.8  120.01     4.1  120.01     4.1  121.01
     5.7  121.72     7.3  122.31       8  122.91      11  123.21
#Mann= 3 , 0 , 0
   -14.5    .035       0      -2    .035       0     7.3    .035       0
#XS Ineff= 2 , 0
              -2     125     7.3             125
Permanent Ineff=
       F       F
#Block Obstruct= 2 , 0
                             7.3
Bank Sta=-2,7.3
XS Rating Curve= 0
Exp/Cntr=.3,.1

Type RM Length L Ch R = 1 ,2550.00 ,50,50,50
BEGIN DESCRIPTION:
51
END DESCRIPTION:
#Sta/Elev= 12
   -14.5  121.51    -4.5  121.51      -2  121.31       0  121.11     1.3  120.11
     1.5  120.11     2.8  121.11     4.1  121.11     5.7  122.11     7.3  122.91
       8  123.51      11  123.81
#Mann= 3 , 0 , 0
   -14.5    .035       0       0    .035       0     2.8    .035       0
#XS Ineff= 2 , 0
               0     125     2.8             125
Permanent Ineff=
       F       F
#Block Obstruct= 2 , 0
                             2.8
Bank Sta=0,2.8
XS Rating Curve= 0
Exp/Cntr=.3,.1

Type RM Length L Ch R = 1 ,2500.00 ,14,14,14
BEGIN DESCRIPTION:
50
END DESCRIPTION:
#Sta/Elev= 10
   -14.7  117.18    -4.7  117.18    -3.9  117.88       0  117.88     3.2  115.98
     5.1  115.98     7.8  117.98     9.2  117.98     9.8  117.38    19.8  117.38
#Mann= 3 , 0 , 0
   -14.7    .035       0       0    .035       0     7.8    .035       0
#XS Ineff= 2 , 0
               0     125     7.8             125
Permanent Ineff=
       F       F
#Block Obstruct= 2 , 0
                             7.8
Bank Sta=0,7.8
XS Rating Curve= 0
Exp/Cntr=.3,.1

Type RM Length L Ch R = 1 ,2486.00 ,26,26,26
BEGIN DESCRIPTION:
49.036
END DESCRIPTION:
#Sta/Elev= 8
   -18.3  116.88    -8.3  116.88      -6  118.58       0  118.58       0  116.88
       2  116.88       2  118.58      12  118.58
#Mann= 3 , 0 , 0
   -18.3    .035       0       0    .035       0       2    .035       0
#XS Ineff= 2 , 0
               0     125       2             125
Permanent Ineff=
       F       F
#Block Obstruct= 2 , 0
                               2
Bank Sta=0,2
XS Rating Curve= 0
Exp/Cntr=.3,.1

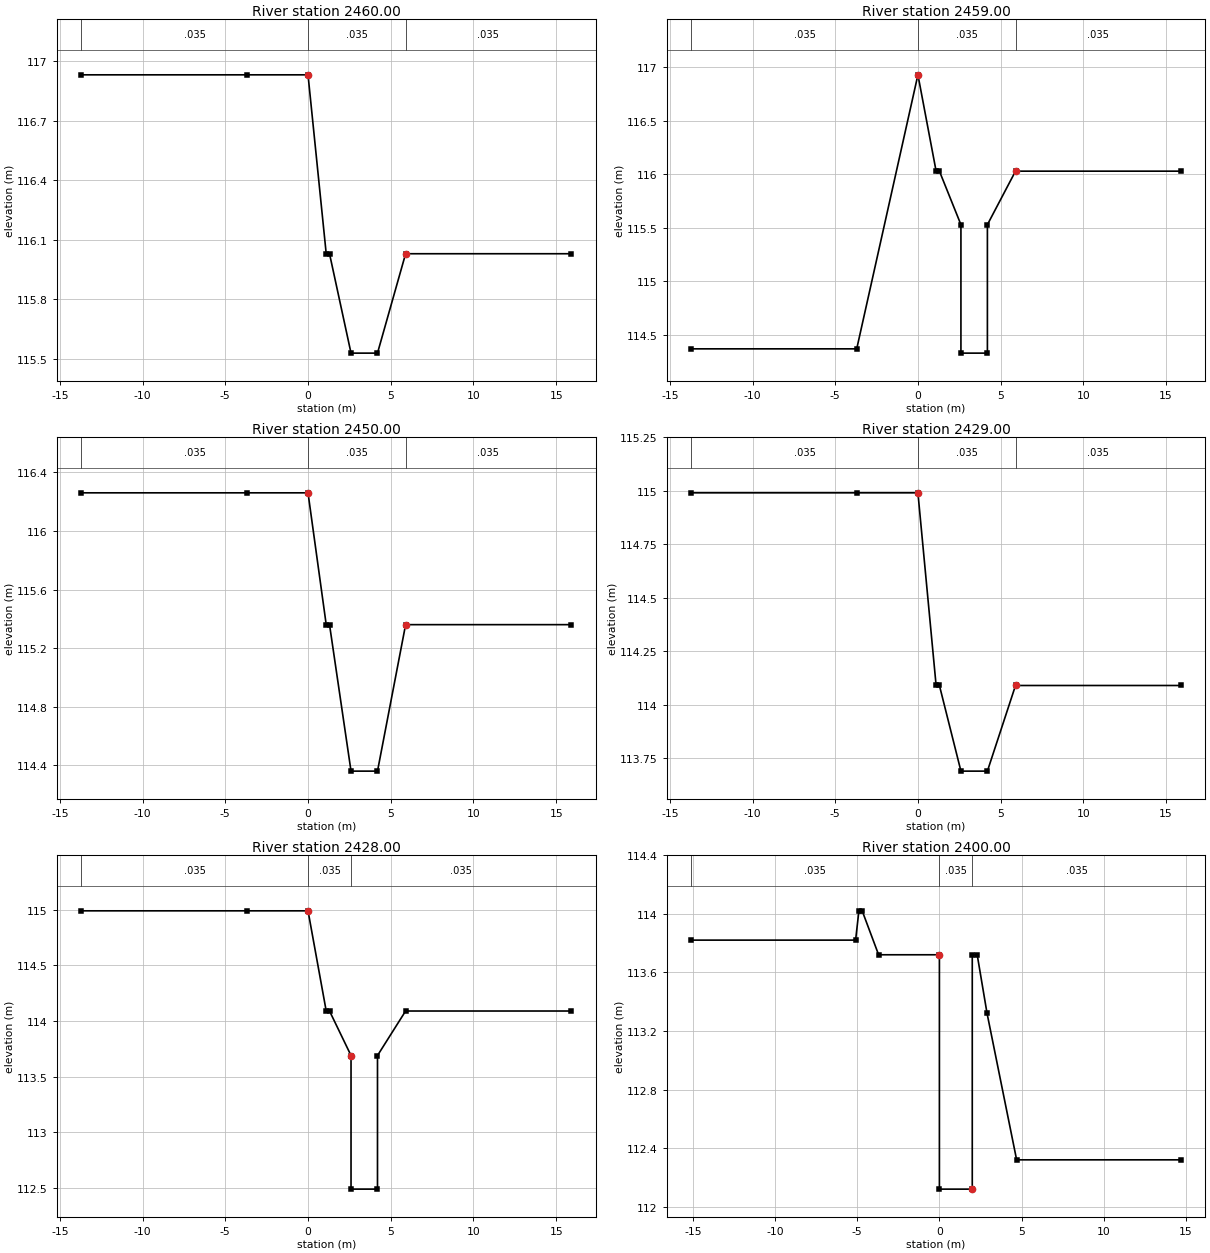
Type RM Length L Ch R = 1 ,2460.00 ,1,1,1
BEGIN DESCRIPTION:
49.01
END DESCRIPTION:
#Sta/Elev= 9
   -13.7  116.93    -3.7  116.93       0  116.93     1.1  116.03     1.3  116.03
     2.6  115.53     4.2  115.53     5.9  116.03    15.9  116.03
#Mann= 3 , 0 , 0
   -13.7    .035       0       0    .035       0     5.9    .035       0
#XS Ineff= 2 , 0
               0     125     5.9             125
Permanent Ineff=
       F       F
#Block Obstruct= 2 , 0
                             5.9
Bank Sta=0,5.9
XS Rating Curve= 0
Exp/Cntr=.3,.1

Type RM Length L Ch R = 1 ,2459.00 ,9,9,9
BEGIN DESCRIPTION:
49.009
END DESCRIPTION:
#Sta/Elev= 11
   -13.7  114.37    -3.7  114.37       0  116.93     1.1  116.03     1.3  116.03
     2.6  115.53     2.6  114.33     4.2  114.33     4.2  115.53     5.9  116.03
    15.9  116.03
#Mann= 3 , 0 , 0
   -13.7    .035       0       0    .035       0     5.9    .035       0
#XS Ineff= 2 , 0
               0     125     5.9             125
Permanent Ineff=
       F       F
#Block Obstruct= 2 , 0
                             5.9
Bank Sta=0,5.9
XS Rating Curve= 0
Exp/Cntr=.3,.1

Type RM Length L Ch R = 1 ,2450.00 ,21,21,21
BEGIN DESCRIPTION:
49
END DESCRIPTION:
#Sta/Elev= 9
   -13.7  116.26    -3.7  116.26       0  116.26     1.1  115.36     1.3  115.36
     2.6  114.36     4.2  114.36     5.9  115.36    15.9  115.36
#Mann= 3 , 0 , 0
   -13.7    .035       0       0    .035       0     5.9    .035       0
#XS Ineff= 2 , 0
               0     125     5.9             125
Permanent Ineff=
       F       F
#Block Obstruct= 2 , 0
                             5.9
Bank Sta=0,5.9
XS Rating Curve= 0
Exp/Cntr=.3,.1

Type RM Length L Ch R = 1 ,2429.00 ,1,1,1
BEGIN DESCRIPTION:
48.029
END DESCRIPTION:
#Sta/Elev= 9
   -13.7  114.99    -3.7  114.99       0  114.99     1.1  114.09     1.3  114.09
     2.6  113.69     4.2  113.69     5.9  114.09    15.9  114.09
#Mann= 3 , 0 , 0
   -13.7    .035       0       0    .035       0     5.9    .035       0
#XS Ineff= 2 , 0
               0     125     5.9             125
Permanent Ineff=
       F       F
#Block Obstruct= 2 , 0
                             5.9
Bank Sta=0,5.9
XS Rating Curve= 0
Exp/Cntr=.3,.1

Type RM Length L Ch R = 1 ,2428.00 ,28,28,28
BEGIN DESCRIPTION:
48.028
END DESCRIPTION:
#Sta/Elev= 11
   -13.7  114.99    -3.7  114.99       0  114.99     1.1  114.09     1.3  114.09
     2.6  113.69     2.6  112.49     4.2  112.49     4.2  113.69     5.9  114.09
    15.9  114.09
#Mann= 3 , 0 , 0
   -13.7    .035       0       0    .035       0     2.6    .035       0
#XS Ineff= 2 , 0
               0     125     2.6             125
Permanent Ineff=
       F       F
#Block Obstruct= 2 , 0
                             2.6
Bank Sta=0,2.6
XS Rating Curve= 0
Exp/Cntr=.3,.1

Type RM Length L Ch R = 1 ,2400.00 ,2,2,2
BEGIN DESCRIPTION:
48
END DESCRIPTION:
#Sta/Elev= 13
   -15.1  113.82    -5.1  113.82    -4.9  114.02    -4.7  114.02    -3.7  113.72
       0  113.72       0  112.12       2  112.12       2  113.72     2.3  113.72
     2.9  113.32     4.7  112.32    14.7  112.32
#Mann= 3 , 0 , 0
   -15.1    .035       0       0    .035       0       2    .035       0
#XS Ineff= 2 , 0
               0     125       2             125
Permanent Ineff=
       F       F
#Block Obstruct= 2 , 0
                               2
Bank Sta=0,2
XS Rating Curve= 0
Exp/Cntr=.3,.1

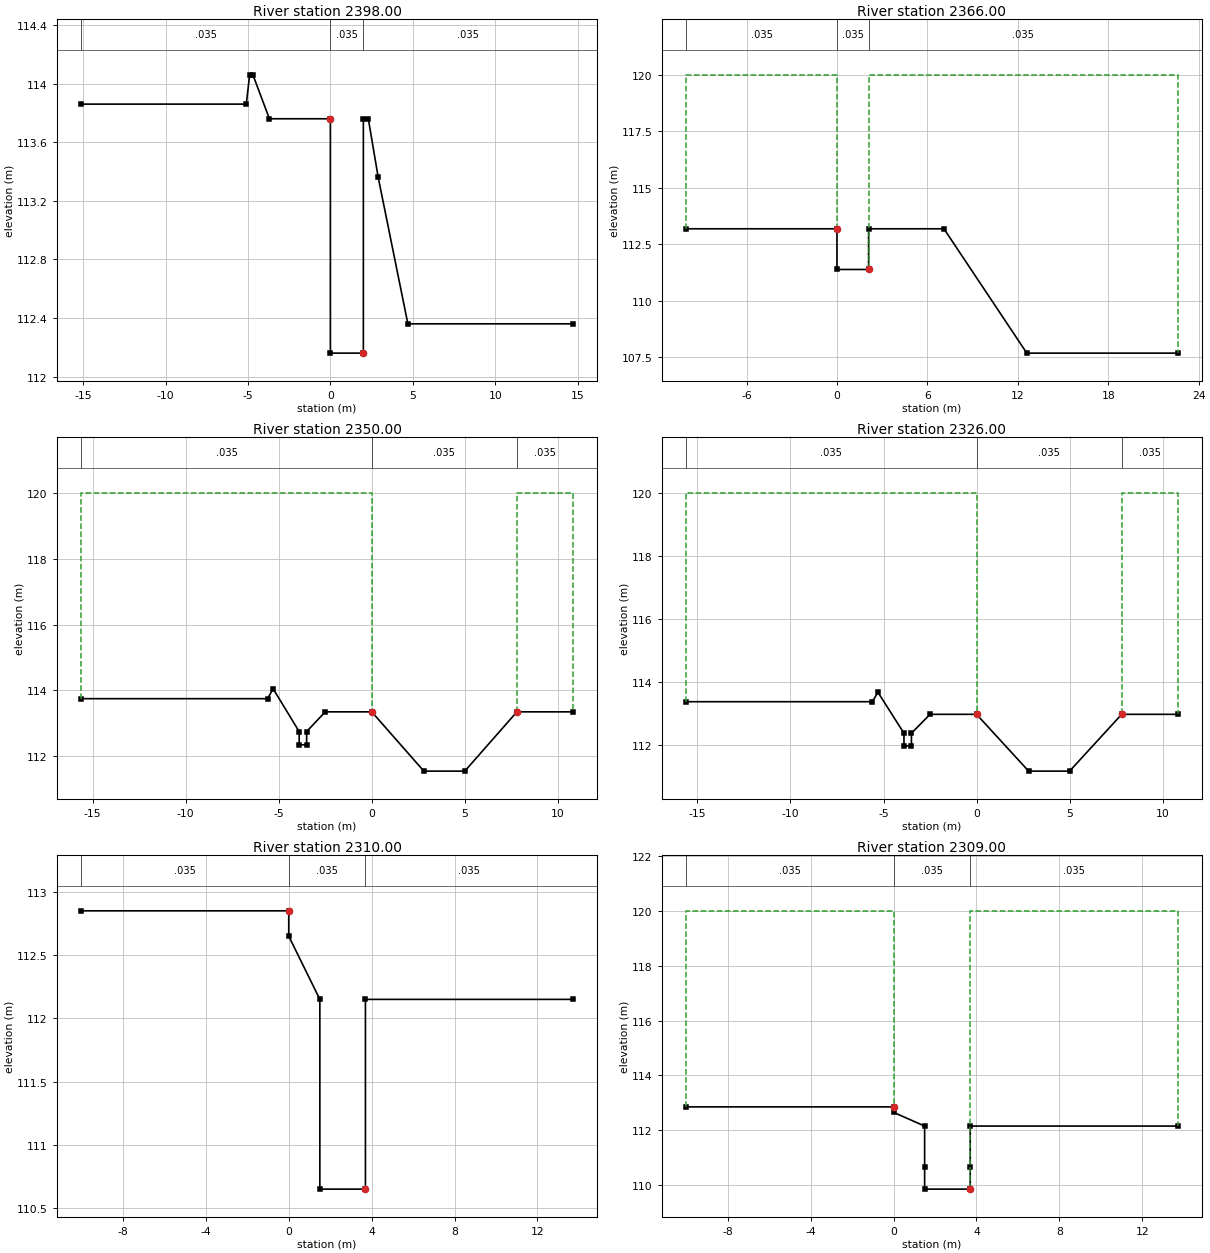
Type RM Length L Ch R = 1 ,2398.00 ,32,32,32
BEGIN DESCRIPTION:
47.048
END DESCRIPTION:
#Sta/Elev= 13
   -15.1  113.86    -5.1  113.86    -4.9  114.06    -4.7  114.06    -3.7  113.76
       0  113.76       0  112.16       2  112.16       2  113.76     2.3  113.76
     2.9  113.36     4.7  112.36    14.7  112.36
#Mann= 3 , 0 , 0
   -15.1    .035       0       0    .035       0       2    .035       0
#XS Ineff= 2 , 0
               0     125       2             125
Permanent Ineff=
       F       F
#Block Obstruct= 2 , 0
                               2
Bank Sta=0,2
XS Rating Curve= 0
Exp/Cntr=.3,.1

Type RM Length L Ch R = 1 ,2366.00 ,16,16,16
BEGIN DESCRIPTION:
47.016
END DESCRIPTION:
#Sta/Elev= 8
     -10  113.19       0  113.19       0  111.39     2.1  111.39     2.1  113.19
     7.1  113.19    12.6  107.69    22.6  107.69
#Mann= 3 , 0 , 0
     -10    .035       0       0    .035       0     2.1    .035       0
#XS Ineff= 2 , 0
               0     120     2.1             120
Permanent Ineff=
       F       F
#Block Obstruct= 2 , 0
                             2.1
Bank Sta=0,2.1
XS Rating Curve= 0
Exp/Cntr=.3,.1

Type RM Length L Ch R = 1 ,2350.00 ,24,24,24
BEGIN DESCRIPTION:
47
END DESCRIPTION:
#Sta/Elev= 13
   -15.6  113.75    -5.6  113.75    -5.3  114.05    -3.9  112.75    -3.9  112.35
    -3.5  112.35    -3.5  112.75    -2.5  113.35       0  113.35     2.8  111.55
       5  111.55     7.8  113.35    10.8  113.35
#Mann= 3 , 0 , 0
   -15.6    .035       0       0    .035       0     7.8    .035       0
#XS Ineff= 2 , 0
               0     120     7.8             120
Permanent Ineff=
       F       F
#Block Obstruct= 2 , 0
                             7.8
Bank Sta=0,7.8
XS Rating Curve= 0
Exp/Cntr=.3,.1

Type RM Length L Ch R = 1 ,2326.00 ,16,16,16
BEGIN DESCRIPTION:
46.026
END DESCRIPTION:
#Sta/Elev= 13
   -15.6  113.38    -5.6  113.38    -5.3  113.68    -3.9  112.38    -3.9  111.98
    -3.5  111.98    -3.5  112.38    -2.5  112.98       0  112.98     2.8  111.18
       5  111.18     7.8  112.98    10.8  112.98
#Mann= 3 , 0 , 0
   -15.6    .035       0       0    .035       0     7.8    .035       0
#XS Ineff= 2 , 0
               0     120     7.8             120
Permanent Ineff=
       F       F
#Block Obstruct= 2 , 0
                             7.8
Bank Sta=0,7.8
XS Rating Curve= 0
Exp/Cntr=.3,.1

Type RM Length L Ch R = 1 ,2310.00 ,1,1,1
BEGIN DESCRIPTION:
46.01
END DESCRIPTION:
#Sta/Elev= 8
     -10  112.85       0  112.85       0  112.65     1.5  112.15     1.5  110.65
     3.7  110.65     3.7  112.15    13.7  112.15
#Mann= 3 , 0 , 0
     -10    .035       0       0    .035       0     3.7    .035       0
#XS Ineff= 2 , 0
               0     120     3.7             120
Permanent Ineff=
       F       F
#Block Obstruct= 2 , 0
                             3.7
Bank Sta=0,3.7
XS Rating Curve= 0
Exp/Cntr=.3,.1

Type RM Length L Ch R = 1 ,2309.00 ,9,9,9
BEGIN DESCRIPTION:
46.009
END DESCRIPTION:
#Sta/Elev= 10
     -10  112.85       0  112.85       0  112.65     1.5  112.15     1.5  110.65
     1.5  109.85     3.7  109.85     3.7  110.65     3.7  112.15    13.7  112.15
#Mann= 3 , 0 , 0
     -10    .035       0       0    .035       0     3.7    .035       0
#XS Ineff= 2 , 0
               0     120     3.7             120
Permanent Ineff=
       F       F
#Block Obstruct= 2 , 0
                             3.7
Bank Sta=0,3.7
XS Rating Curve= 0
Exp/Cntr=.3,.1

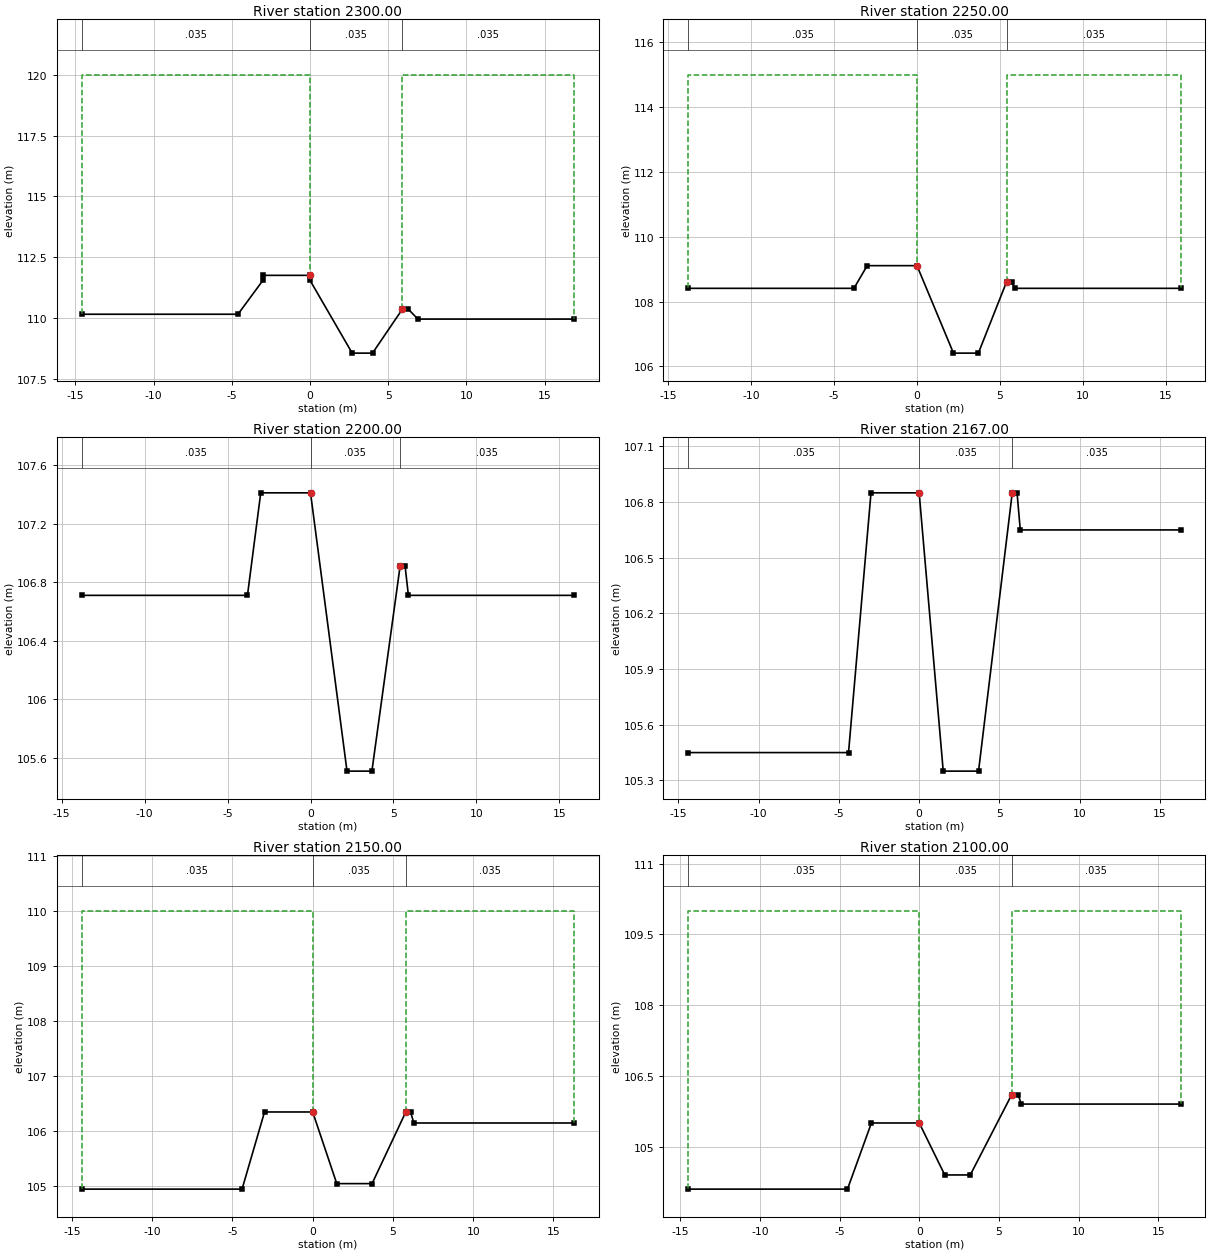
Type RM Length L Ch R = 1 ,2300.00 ,50,50,50
BEGIN DESCRIPTION:
46
END DESCRIPTION:
#Sta/Elev= 12
   -14.6  110.15    -4.6  110.15      -3  111.55      -3  111.75       0  111.75
       0  111.55     2.7  108.55       4  108.55     5.9  110.35     6.3  110.35
     6.9  109.95    16.9  109.95
#Mann= 3 , 0 , 0
   -14.6    .035       0       0    .035       0     5.9    .035       0
#XS Ineff= 2 , 0
               0     120     5.9             120
Permanent Ineff=
       F       F
#Block Obstruct= 2 , 0
                             5.9
Bank Sta=0,5.9
XS Rating Curve= 0
Exp/Cntr=.3,.1

Type RM Length L Ch R = 1 ,2250.00 ,50,50,50
BEGIN DESCRIPTION:
45
END DESCRIPTION:
#Sta/Elev= 10
   -13.8  108.41    -3.8  108.41      -3  109.11       0  109.11     2.2  106.41
     3.7  106.41     5.4  108.61     5.7  108.61     5.9  108.41    15.9  108.41
#Mann= 3 , 0 , 0
   -13.8    .035       0       0    .035       0     5.4    .035       0
#XS Ineff= 2 , 0
               0     115     5.4             115
Permanent Ineff=
       F       F
#Block Obstruct= 2 , 0
                             5.4
Bank Sta=0,5.4
XS Rating Curve= 0
Exp/Cntr=.3,.1

Type RM Length L Ch R = 1 ,2200.00 ,33,33,33
BEGIN DESCRIPTION:
44
END DESCRIPTION:
#Sta/Elev= 10
   -13.8  106.71    -3.8  106.71      -3  107.41       0  107.41     2.2  105.51
     3.7  105.51     5.4  106.91     5.7  106.91     5.9  106.71    15.9  106.71
#Mann= 3 , 0 , 0
   -13.8    .035       0       0    .035       0     5.4    .035       0
#XS Ineff= 2 , 0
               0     115     5.4             115
Permanent Ineff=
       F       F
#Block Obstruct= 2 , 0
                             5.4
Bank Sta=0,5.4
XS Rating Curve= 0
Exp/Cntr=.3,.1

Type RM Length L Ch R = 1 ,2167.00 ,17,17,17
BEGIN DESCRIPTION:
43.017
END DESCRIPTION:
#Sta/Elev= 10
   -14.4  105.45    -4.4  105.45      -3  106.85       0  106.85     1.5  105.35
     3.7  105.35     5.8  106.85     6.1  106.85     6.3  106.65    16.3  106.65
#Mann= 3 , 0 , 0
   -14.4    .035       0       0    .035       0     5.8    .035       0
#XS Ineff= 2 , 0
               0     115     5.8             115
Permanent Ineff=
       F       F
#Block Obstruct= 2 , 0
                             5.8
Bank Sta=0,5.8
XS Rating Curve= 0
Exp/Cntr=.3,.1

Type RM Length L Ch R = 1 ,2150.00 ,50,50,50
BEGIN DESCRIPTION:
43
END DESCRIPTION:
#Sta/Elev= 10
   -14.4  104.95    -4.4  104.95      -3  106.35       0  106.35     1.5  105.05
     3.7  105.05     5.8  106.35     6.1  106.35     6.3  106.15    16.3  106.15
#Mann= 3 , 0 , 0
   -14.4    .035       0       0    .035       0     5.8    .035       0
#XS Ineff= 2 , 0
               0     110     5.8             110
Permanent Ineff=
       F       F
#Block Obstruct= 2 , 0
                             5.8
Bank Sta=0,5.8
XS Rating Curve= 0
Exp/Cntr=.3,.1

Type RM Length L Ch R = 1 ,2100.00 ,50,50,50
BEGIN DESCRIPTION:
42
END DESCRIPTION:
#Sta/Elev= 10
   -14.5  104.11    -4.5  104.11      -3  105.51       0  105.51     1.6  104.41
     3.2  104.41     5.8  106.11     6.2  106.11     6.4  105.91    16.4  105.91
#Mann= 3 , 0 , 0
   -14.5    .035       0       0    .035       0     5.8    .035       0
#XS Ineff= 2 , 0
               0     110     5.8             110
Permanent Ineff=
       F       F
#Block Obstruct= 2 , 0
                             5.8
Bank Sta=0,5.8
XS Rating Curve= 0
Exp/Cntr=.3,.1

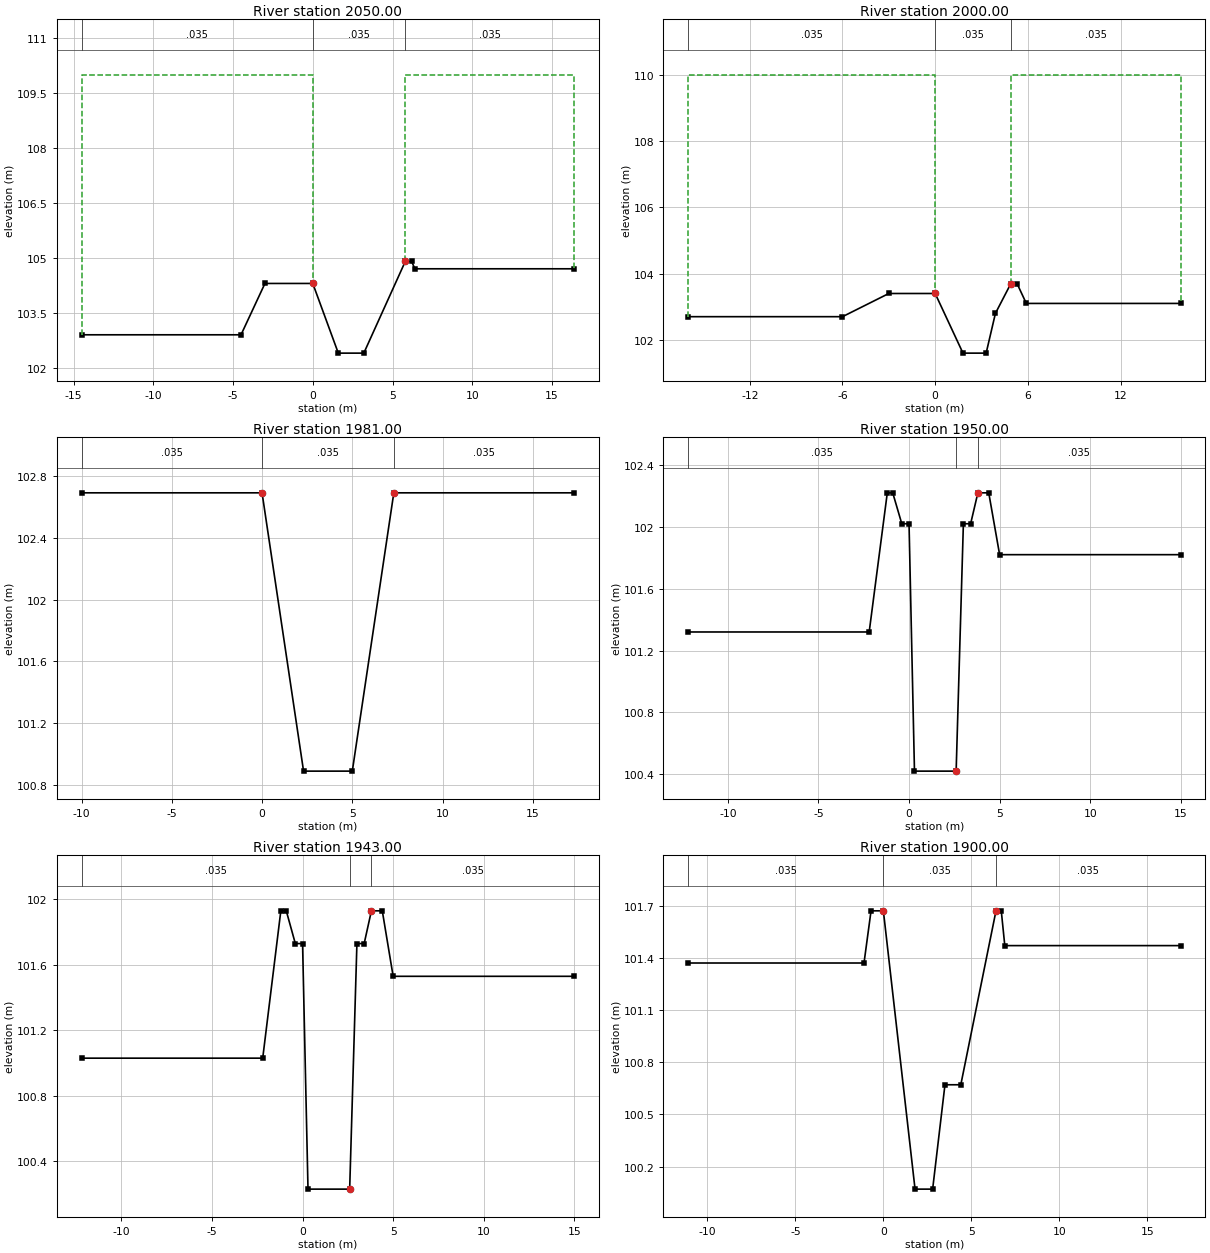
Type RM Length L Ch R = 1 ,2050.00 ,50,50,50
BEGIN DESCRIPTION:
41
END DESCRIPTION:
#Sta/Elev= 10
   -14.5  102.91    -4.5  102.91      -3  104.31       0  104.31     1.6  102.41
     3.2  102.41     5.8  104.91     6.2  104.91     6.4  104.71    16.4  104.71
#Mann= 3 , 0 , 0
   -14.5    .035       0       0    .035       0     5.8    .035       0
#XS Ineff= 2 , 0
               0     110     5.8             110
Permanent Ineff=
       F       F
#Block Obstruct= 2 , 0
                             5.8
Bank Sta=0,5.8
XS Rating Curve= 0
Exp/Cntr=.3,.1

Type RM Length L Ch R = 1 ,2000.00 ,19,19,19
BEGIN DESCRIPTION:
40
END DESCRIPTION:
#Sta/Elev= 11
     -16   102.7      -6   102.7      -3   103.4       0   103.4     1.8   101.6
     3.3   101.6     3.9   102.8     4.9   103.7     5.3   103.7     5.9   103.1
    15.9   103.1
#Mann= 3 , 0 , 0
     -16    .035       0       0    .035       0     4.9    .035       0
#XS Ineff= 2 , 0
               0     110     4.9             110
Permanent Ineff=
       F       F
#Block Obstruct= 2 , 0
                             4.9
Bank Sta=0,4.9
XS Rating Curve= 0
Exp/Cntr=.3,.1

Type RM Length L Ch R = 1 ,1981.00 ,31,31,31
BEGIN DESCRIPTION:
39.031
END DESCRIPTION:
#Sta/Elev= 6
     -10  102.69       0  102.69     2.3  100.89       5  100.89     7.3  102.69
    17.3  102.69
#Mann= 3 , 0 , 0
     -10    .035       0       0    .035       0     7.3    .035       0
#XS Ineff= 2 , 0
               0     110     7.3             110
Permanent Ineff=
       F       F
#Block Obstruct= 2 , 0
                             7.3
Bank Sta=0,7.3
XS Rating Curve= 0
Exp/Cntr=.3,.1

Type RM Length L Ch R = 1 ,1950.00 ,7,7,7
BEGIN DESCRIPTION:
39
END DESCRIPTION:
#Sta/Elev= 14
   -12.2  101.32    -2.2  101.32    -1.2  102.22     -.9  102.22     -.4  102.02
       0  102.02      .3  100.42     2.6  100.42       3  102.02     3.4  102.02
     3.8  102.22     4.4  102.22       5  101.82      15  101.82
#Mann= 3 , 0 , 0
   -12.2    .035       0     2.6    .035       0     3.8    .035       0
#XS Ineff= 2 , 0
             2.6     110     3.8             110
Permanent Ineff=
       F       F
#Block Obstruct= 2 , 0
                             3.8
Bank Sta=2.6,3.8
XS Rating Curve= 0
Exp/Cntr=.3,.1

Type RM Length L Ch R = 1 ,1943.00 ,43,43,43
BEGIN DESCRIPTION:
38.043
END DESCRIPTION:
#Sta/Elev= 14
   -12.2  101.03    -2.2  101.03    -1.2  101.93     -.9  101.93     -.4  101.73
       0  101.73      .3  100.23     2.6  100.23       3  101.73     3.4  101.73
     3.8  101.93     4.4  101.93       5  101.53      15  101.53
#Mann= 3 , 0 , 0
   -12.2    .035       0     2.6    .035       0     3.8    .035       0
#XS Ineff= 2 , 0
             2.6     110     3.8             110
Permanent Ineff=
       F       F
#Block Obstruct= 2 , 0
                             3.8
Bank Sta=2.6,3.8
XS Rating Curve= 0
Exp/Cntr=.3,.1

Type RM Length L Ch R = 1 ,1900.00 ,50,50,50
BEGIN DESCRIPTION:
38
END DESCRIPTION:
#Sta/Elev= 12
   -11.1  101.37    -1.1  101.37     -.7  101.67       0  101.67     1.8  100.07
     2.8  100.07     3.5  100.67     4.4  100.67     6.4  101.67     6.7  101.67
     6.9  101.47    16.9  101.47
#Mann= 3 , 0 , 0
   -11.1    .035       0       0    .035       0     6.4    .035       0
#XS Ineff= 2 , 0
               0     110     6.4             110
Permanent Ineff=
       F       F
#Block Obstruct= 2 , 0
                             6.4
Bank Sta=0,6.4
XS Rating Curve= 0
Exp/Cntr=.3,.1

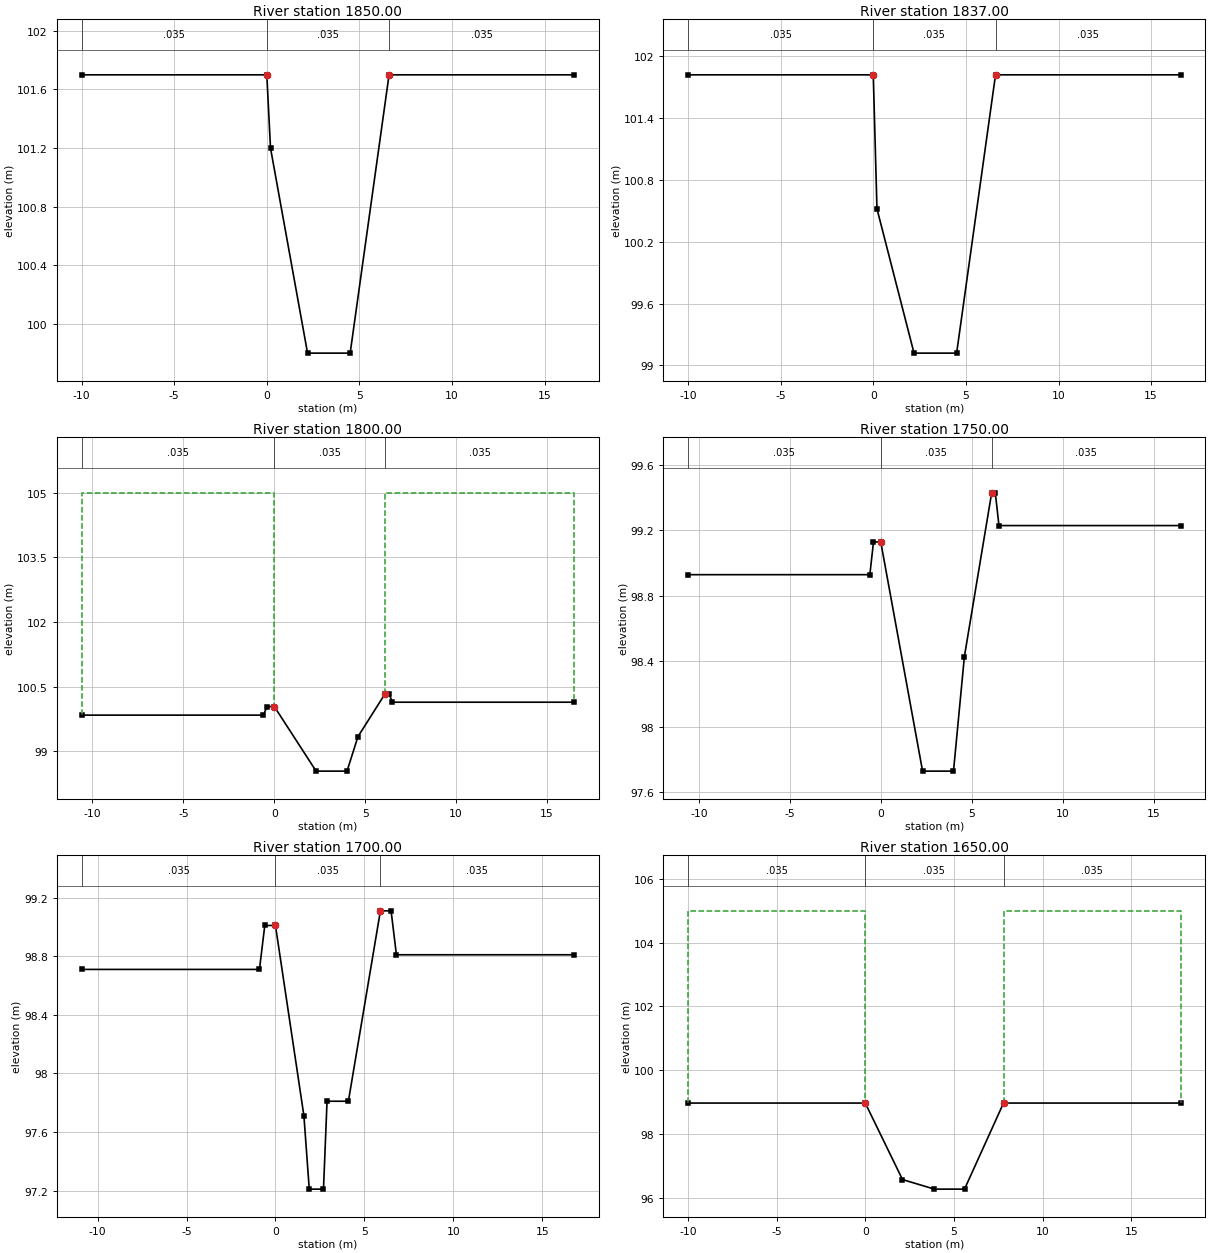
Type RM Length L Ch R = 1 ,1850.00 ,13,13,13
BEGIN DESCRIPTION:
37
END DESCRIPTION:
#Sta/Elev= 7
     -10   101.7       0   101.7      .2   101.2     2.2    99.8     4.5    99.8
     6.6   101.7    16.6   101.7
#Mann= 3 , 0 , 0
     -10    .035       0       0    .035       0     6.6    .035       0
#XS Ineff= 2 , 0
               0     110     6.6             110
Permanent Ineff=
       F       F
#Block Obstruct= 2 , 0
                             6.6
Bank Sta=0,6.6
XS Rating Curve= 0
Exp/Cntr=.3,.1

Type RM Length L Ch R = 1 ,1837.00 ,37,37,37
BEGIN DESCRIPTION:
36.037
END DESCRIPTION:
#Sta/Elev= 7
     -10  101.82       0  101.82      .2  100.52     2.2   99.12     4.5   99.12
     6.6  101.82    16.6  101.82
#Mann= 3 , 0 , 0
     -10    .035       0       0    .035       0     6.6    .035       0
#XS Ineff= 2 , 0
               0     110     6.6             110
Permanent Ineff=
       F       F
#Block Obstruct= 2 , 0
                             6.6
Bank Sta=0,6.6
XS Rating Curve= 0
Exp/Cntr=.3,.1

Type RM Length L Ch R = 1 ,1800.00 ,50,50,50
BEGIN DESCRIPTION:
36
END DESCRIPTION:
#Sta/Elev= 11
   -10.6   99.84     -.6   99.84     -.4  100.04       0  100.04     2.3   98.54
       4   98.54     4.6   99.34     6.1  100.34     6.3  100.34     6.5  100.14
    16.5  100.14
#Mann= 3 , 0 , 0
   -10.6    .035       0       0    .035       0     6.1    .035       0
#XS Ineff= 2 , 0
               0     105     6.1             105
Permanent Ineff=
       F       F
#Block Obstruct= 2 , 0
                             6.1
Bank Sta=0,6.1
XS Rating Curve= 0
Exp/Cntr=.3,.1

Type RM Length L Ch R = 1 ,1750.00 ,50,50,50
BEGIN DESCRIPTION:
35
END DESCRIPTION:
#Sta/Elev= 11
   -10.6   98.93     -.6   98.93     -.4   99.13       0   99.13     2.3   97.73
       4   97.73     4.6   98.43     6.1   99.43     6.3   99.43     6.5   99.23
    16.5   99.23
#Mann= 3 , 0 , 0
   -10.6    .035       0       0    .035       0     6.1    .035       0
#XS Ineff= 2 , 0
               0     105     6.1             105
Permanent Ineff=
       F       F
#Block Obstruct= 2 , 0
                             6.1
Bank Sta=0,6.1
XS Rating Curve= 0
Exp/Cntr=.3,.1

Type RM Length L Ch R = 1 ,1700.00 ,50,50,50
BEGIN DESCRIPTION:
34
END DESCRIPTION:
#Sta/Elev= 13
   -10.9   98.71     -.9   98.71     -.6   99.01       0   99.01     1.6   97.71
     1.9   97.21     2.7   97.21     2.9   97.81     4.1   97.81     5.9   99.11
     6.5   99.11     6.8   98.81    16.8   98.81
#Mann= 3 , 0 , 0
   -10.9    .035       0       0    .035       0     5.9    .035       0
#XS Ineff= 2 , 0
               0     105     5.9             105
Permanent Ineff=
       F       F
#Block Obstruct= 2 , 0
                             5.9
Bank Sta=0,5.9
XS Rating Curve= 0
Exp/Cntr=.3,.1

Type RM Length L Ch R = 1 ,1650.00 ,7,7,7
BEGIN DESCRIPTION:
33
END DESCRIPTION:
#Sta/Elev= 7
     -10   98.97       0   98.97     2.1   96.57     3.9   96.27     5.6   96.27
     7.8   98.97    17.8   98.97
#Mann= 3 , 0 , 0
     -10    .035       0       0    .035       0     7.8    .035       0
#XS Ineff= 2 , 0
               0     105     7.8             105
Permanent Ineff=
       F       F
#Block Obstruct= 2 , 0
                             7.8
Bank Sta=0,7.8
XS Rating Curve= 0
Exp/Cntr=.3,.1

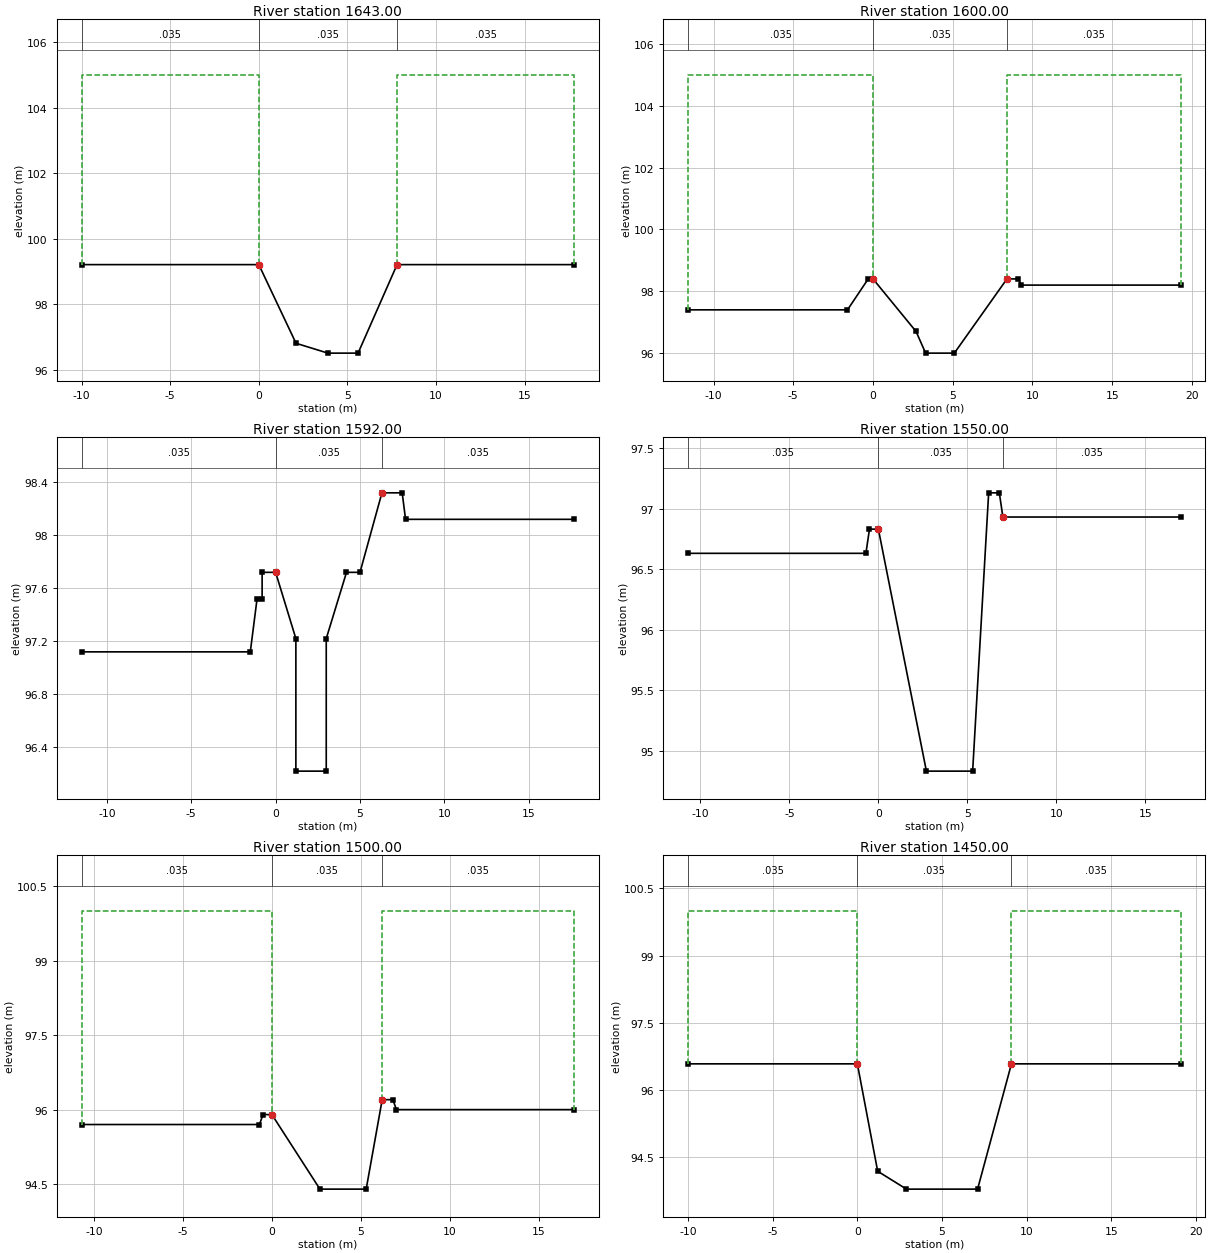
Type RM Length L Ch R = 1 ,1643.00 ,43,43,43
BEGIN DESCRIPTION:
32.043
END DESCRIPTION:
#Sta/Elev= 7
     -10   99.21       0   99.21     2.1   96.81     3.9   96.51     5.6   96.51
     7.8   99.21    17.8   99.21
#Mann= 3 , 0 , 0
     -10    .035       0       0    .035       0     7.8    .035       0
#XS Ineff= 2 , 0
               0     105     7.8             105
Permanent Ineff=
       F       F
#Block Obstruct= 2 , 0
                             7.8
Bank Sta=0,7.8
XS Rating Curve= 0
Exp/Cntr=.3,.1

Type RM Length L Ch R = 1 ,1600.00 ,8,8,8
BEGIN DESCRIPTION:
32
END DESCRIPTION:
#Sta/Elev= 11
   -11.6    97.4    -1.6    97.4     -.3    98.4       0    98.4     2.7    96.7
     3.3      96     5.1      96     8.4    98.4     9.1    98.4     9.3    98.2
    19.3    98.2
#Mann= 3 , 0 , 0
   -11.6    .035       0       0    .035       0     8.4    .035       0
#XS Ineff= 2 , 0
               0     105     8.4             105
Permanent Ineff=
       F       F
#Block Obstruct= 2 , 0
                             8.4
Bank Sta=0,8.4
XS Rating Curve= 0
Exp/Cntr=.3,.1

Type RM Length L Ch R = 1 ,1592.00 ,42,42,42
BEGIN DESCRIPTION:
31.042
END DESCRIPTION:
#Sta/Elev= 16
   -11.5   97.12    -1.5   97.12    -1.1   97.52     -.8   97.52     -.8   97.72
       0   97.72     1.2   97.22     1.2   96.22       3   96.22       3   97.22
     4.2   97.72       5   97.72     6.3   98.32     7.5   98.32     7.7   98.12
    17.7   98.12
#Mann= 3 , 0 , 0
   -11.5    .035       0       0    .035       0     6.3    .035       0
#XS Ineff= 2 , 0
               0     105     6.3             105
Permanent Ineff=
       F       F
#Block Obstruct= 2 , 0
                             6.3
Bank Sta=0,6.3
XS Rating Curve= 0
Exp/Cntr=.3,.1

Type RM Length L Ch R = 1 ,1550.00 ,50,50,50
BEGIN DESCRIPTION:
31
END DESCRIPTION:
#Sta/Elev= 10
   -10.7   96.63     -.7   96.63     -.5   96.83       0   96.83     2.7   94.83
     5.3   94.83     6.2   97.13     6.8   97.13       7   96.93      17   96.93
#Mann= 3 , 0 , 0
   -10.7    .035       0       0    .035       0       7    .035       0
#XS Ineff= 2 , 0
               0     105       7             105
Permanent Ineff=
       F       F
#Block Obstruct= 2 , 0
                               7
Bank Sta=0,7
XS Rating Curve= 0
Exp/Cntr=.3,.1

Type RM Length L Ch R = 1 ,1500.00 ,50,50,50
BEGIN DESCRIPTION:
30
END DESCRIPTION:
#Sta/Elev= 10
   -10.7    95.7     -.7    95.7     -.5    95.9       0    95.9     2.7    94.4
     5.3    94.4     6.2    96.2     6.8    96.2       7      96      17      96
#Mann= 3 , 0 , 0
   -10.7    .035       0       0    .035       0     6.2    .035       0
#XS Ineff= 2 , 0
               0     100     6.2             100
Permanent Ineff=
       F       F
#Block Obstruct= 2 , 0
                             6.2
Bank Sta=0,6.2
XS Rating Curve= 0
Exp/Cntr=.3,.1

Type RM Length L Ch R = 1 ,1450.00 ,50,50,50
BEGIN DESCRIPTION:
29
END DESCRIPTION:
#Sta/Elev= 7
     -10   96.58       0   96.58     1.2   94.18     2.9   93.78     7.1   93.78
     9.1   96.58    19.1   96.58
#Mann= 3 , 0 , 0
     -10    .035       0       0    .035       0     9.1    .035       0
#XS Ineff= 2 , 0
               0     100     9.1             100
Permanent Ineff=
       F       F
#Block Obstruct= 2 , 0
                             9.1
Bank Sta=0,9.1
XS Rating Curve= 0
Exp/Cntr=.3,.1