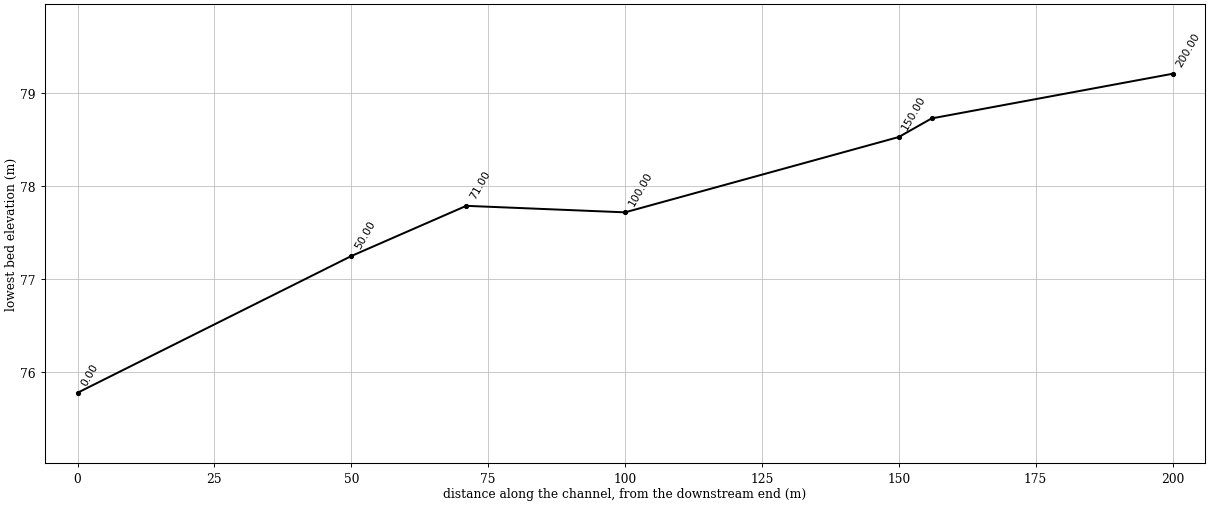
HEC-RAS study SIN.prj: SIN

--- SIN.g01 (geometry) --- (continued)

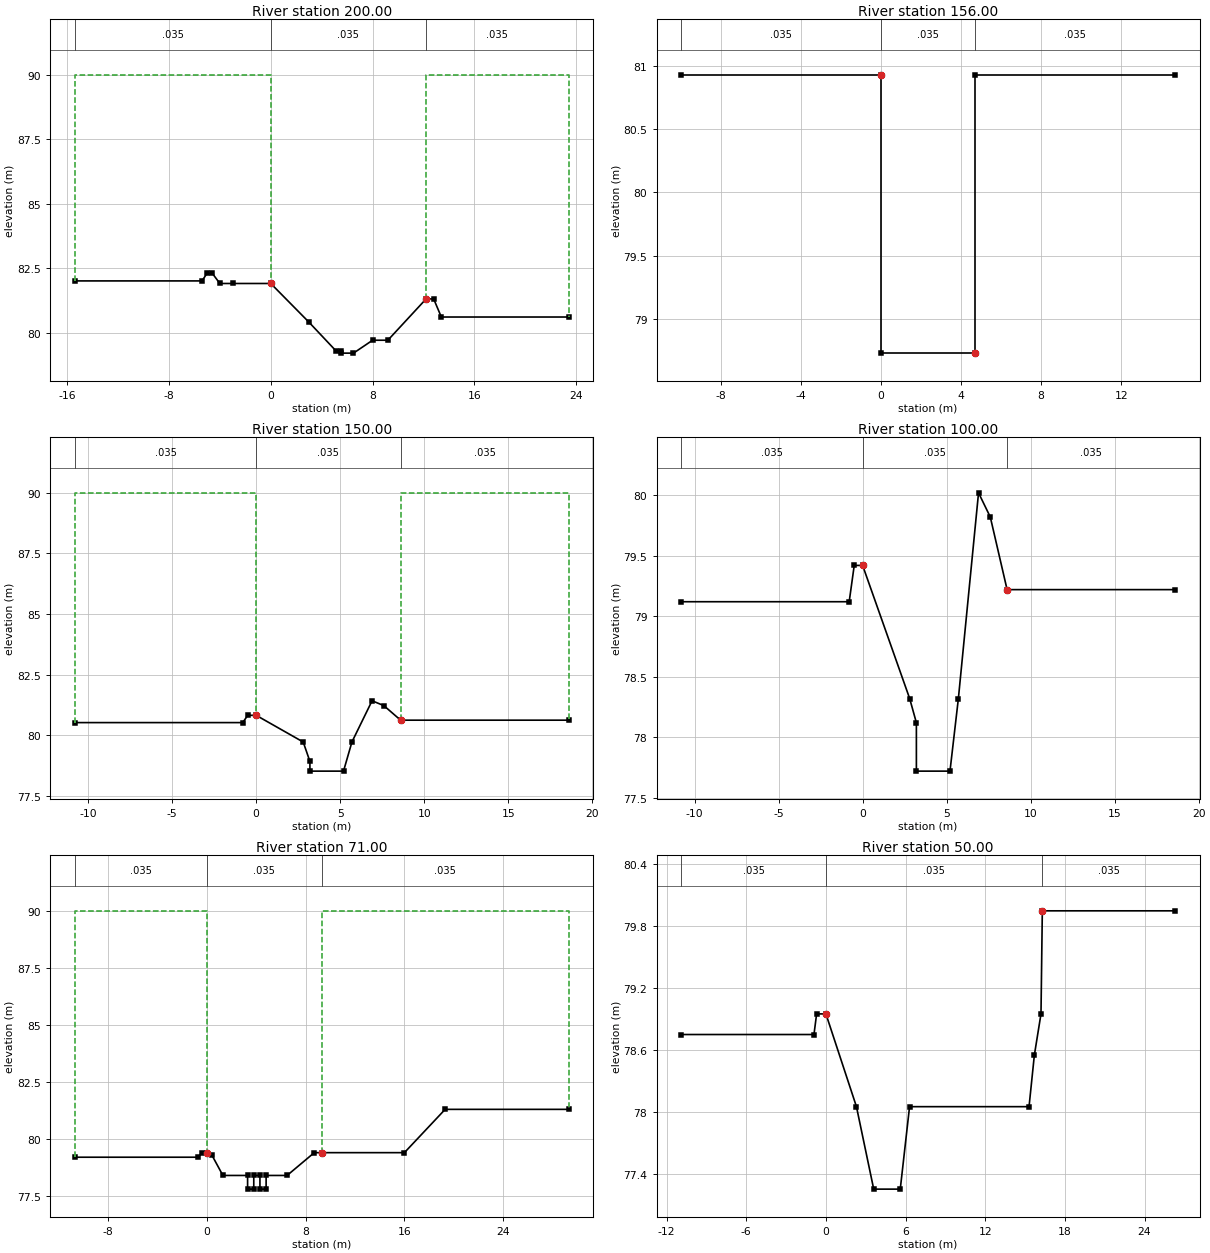
Type RM Length L Ch R = 1 ,200.00  ,44,44,44
BEGIN DESCRIPTION:
4
END DESCRIPTION:
#Sta/Elev= 18
   -15.4   82.01    -5.4   82.01      -5   82.31    -4.6   82.31      -4   81.91
      -3   81.91       0   81.91       3   80.41     5.1   79.31     5.5   79.31
     5.5   79.21     6.5   79.21       8   79.71     9.2   79.71    12.2   81.31
    12.8   81.31    13.4   80.61    23.4   80.61
#Mann= 3 , 0 , 0
   -15.4    .035       0       0    .035       0    12.2    .035       0
#XS Ineff= 2 , 0
               0      90    12.2              90
Permanent Ineff=
       F       F
#Block Obstruct= 2 , 0
                            12.2
Bank Sta=0,12.2
XS Rating Curve= 0
Exp/Cntr=.3,.1

Type RM Length L Ch R = 1 ,156.00  ,6,6,6
BEGIN DESCRIPTION:
3.006
END DESCRIPTION:
#Sta/Elev= 6
     -10   80.93       0   80.93       0   78.73     4.7   78.73     4.7   80.93
    14.7   80.93
#Mann= 3 , 0 , 0
     -10    .035       0       0    .035       0     4.7    .035       0
#XS Ineff= 2 , 0
               0      90     4.7              90
Permanent Ineff=
       F       F
#Block Obstruct= 2 , 0
                             4.7
Bank Sta=0,4.7
XS Rating Curve= 0
Exp/Cntr=.3,.1

Type RM Length L Ch R = 1 ,150.00  ,50,50,50
BEGIN DESCRIPTION:
3
END DESCRIPTION:
#Sta/Elev= 13
   -10.8   80.53     -.8   80.53     -.5   80.83       0   80.83     2.8   79.73
     3.2   78.93     3.2   78.53     5.2   78.53     5.7   79.73     6.9   81.43
     7.6   81.23     8.6   80.63    18.6   80.63
#Mann= 3 , 0 , 0
   -10.8    .035       0       0    .035       0     8.6    .035       0
#XS Ineff= 2 , 0
               0      90     8.6              90
Permanent Ineff=
       F       F
#Block Obstruct= 2 , 0
                             8.6
Bank Sta=0,8.6
XS Rating Curve= 0
Exp/Cntr=.3,.1

Type RM Length L Ch R = 1 ,100.00  ,29,29,29
BEGIN DESCRIPTION:
2
END DESCRIPTION:
#Sta/Elev= 13
   -10.8   79.12     -.8   79.12     -.5   79.42       0   79.42     2.8   78.32
     3.2   78.12     3.2   77.72     5.2   77.72     5.7   78.32     6.9   80.02
     7.6   79.82     8.6   79.22    18.6   79.22
#Mann= 3 , 0 , 0
   -10.8    .035       0       0    .035       0     8.6    .035       0
#XS Ineff= 2 , 0
               0      90     8.6              90
Permanent Ineff=
       F       F
#Block Obstruct= 2 , 0
                             8.6
Bank Sta=0,8.6
XS Rating Curve= 0
Exp/Cntr=.3,.1

Type RM Length L Ch R = 1 ,71.00   ,21,21,21
BEGIN DESCRIPTION:
1.021
END DESCRIPTION:
#Sta/Elev= 20
   -10.7   79.19     -.7   79.19     -.4   79.39       0   79.39      .4   79.29
     1.3   78.39     3.3   78.39     3.3   77.79     3.8   77.79     3.8   78.39
     4.3   78.39     4.3   77.79     4.8   77.79     4.8   78.39     6.5   78.39
     8.7   79.39     9.3   79.39      16   79.39    19.3   81.29    29.3   81.29
#Mann= 3 , 0 , 0
   -10.7    .035       0       0    .035       0     9.3    .035       0
#XS Ineff= 2 , 0
               0      90     9.3              90
Permanent Ineff=
       F       F
#Block Obstruct= 2 , 0
                             9.3
Bank Sta=0,9.3
XS Rating Curve= 0
Exp/Cntr=.3,.1

Type RM Length L Ch R = 1 ,50.00   ,50,50,50
BEGIN DESCRIPTION:
1
END DESCRIPTION:
#Sta/Elev= 13
   -10.9   78.75     -.9   78.75     -.7   78.95       0   78.95     2.3   78.05
     3.6   77.25     5.6   77.25     6.3   78.05    15.3   78.05    15.7   78.55
    16.2   78.95    16.3   79.95    26.3   79.95
#Mann= 3 , 0 , 0
   -10.9    .035       0       0    .035       0    16.3    .035       0
#XS Ineff= 2 , 0
               0      90    16.3              90
Permanent Ineff=
       F       F
#Block Obstruct= 2 , 0
                            16.3
Bank Sta=0,16.3
XS Rating Curve= 0
Exp/Cntr=.3,.1

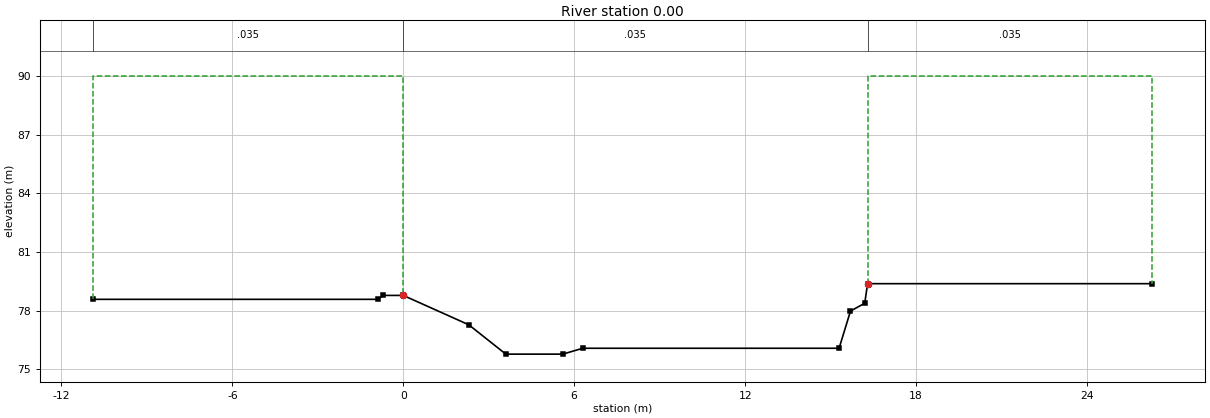
Type RM Length L Ch R = 1 ,0.00    ,0,0,0
BEGIN DESCRIPTION:
0
END DESCRIPTION:
#Sta/Elev= 13
   -10.9   78.58     -.9   78.58     -.7   78.78       0   78.78     2.3   77.28
     3.6   75.78     5.6   75.78     6.3   76.08    15.3   76.08    15.7   77.98
    16.2   78.38    16.3   79.38    26.3   79.38
#Mann= 3 , 0 , 0
   -10.9    .035       0       0    .035       0    16.3    .035       0
#XS Ineff= 2 , 0
               0      90    16.3              90
Permanent Ineff=
       F       F
#Block Obstruct= 2 , 0
                            16.3
Bank Sta=0,16.3
XS Rating Curve= 0
Exp/Cntr=.3,.1

Chan Stop Cuts=-1