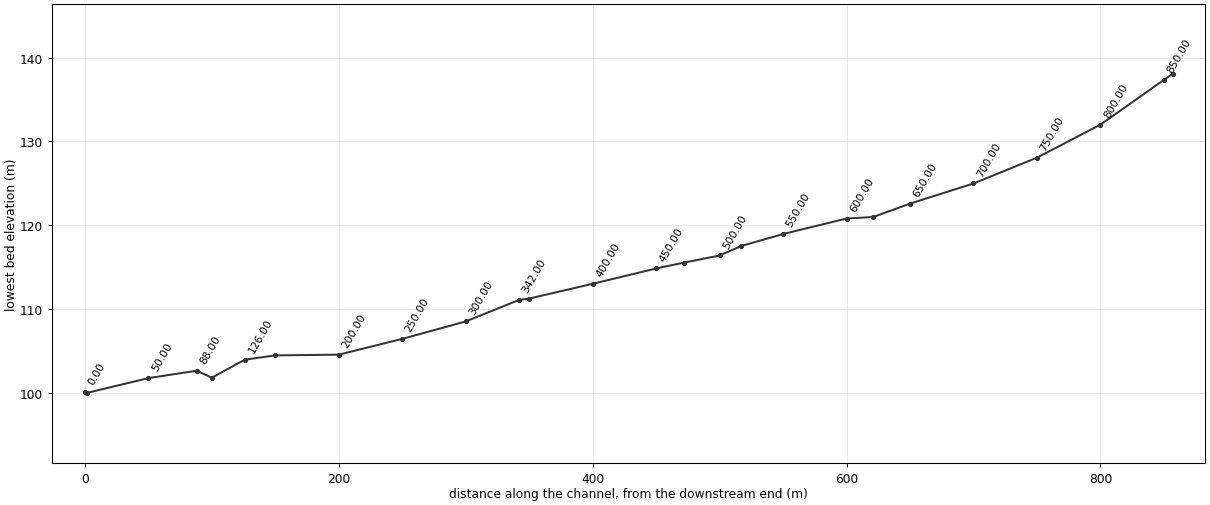
--- BSC.prj (project) ---

Proj Title=BAPSAN
Current Plan=p01
Default Exp/Contr=.3,.1
SI Units
Geom File=g01
Flow File=f01
Plan File=p01
Y Axis Title=Elevation
X Axis Title(PF)=Main Channel Distance
X Axis Title(XS)=Station
BEGIN DESCRIPTION:
           BACK WATER COMPUTATION
      APPLICATION OF HEC-2 BY Samju Construction Engineering
      babsan-ch: 10,20,30,50,80 yr
END DESCRIPTION:
DSS Export Rating Curves= 0
DSS Export Rating Curve Sorted= 0
DSS Export Volume Flow Curves= 0
DXF OffsetX= 0
DXF OffsetY= 0
DXF ScaleX= 1
DXF ScaleY= 10

--- BSC.p01 (plan) ---

Plan Title=Imported Plan 01
Version=Version 3.0.1  Mar 2001
Short Identifier=Imported Pla
Geom File=g01
Flow File=f01
Subcritical Flow
K Sum by GR= 0
Std Step Tol= 0.003
Critical Tol= 0.003
Num of Std Step Trials= 20
Max Error Tol= 0.1
Flow Tol Ratio= 0.001
Split Flow NTrial= 30
Split Flow Tol= 0.02
Split Flow Ratio= 0.02
Log Output Level= 0
Friction Slope Method= 1
Unsteady Friction Slope Method= 2
Parabolic Critical Depth
Global Vel Dist= 0 , 0 , 0
Global Log Level= 0
CheckData=True
Encroach Param=-1 ,0,0, 0
Computation Interval=1HOUR
Output Interval=1HOUR
Run HTab= 0
Run UNet= 0
Run PostProcess= 0
UNET Theta= 1
UNET ZTol= 0.02
UNET ZSATol= 0.1
UNET MxIter= 20
UNET MaxInSteps= 20
UNET DtIC= 0
UNET DtMin= 0
UNET MaxCRTS= 20
UNET WFStab= 2
UNET SFStab= 1
UNET WFX= 1
UNET SFX= 1
UNET Convert EG Bridges=-1
UNET Use Existing IB Tables=-1
Instantaneous Interval=1HOUR
Write IC File= 0
Write Velocity= 0
Write Detailed= 0

--- BSC.f01 (steady flow) ---

Flow Title=Imported Flow 01
Version=Version 3.0.1  Mar 2001
Number of Profiles= 5
Profile Names=10YR,20YR,30YR,50YR,80YR
River Rch & RM=RIVER-1,Reach-1         ,857.00
    4.66    5.13    5.41    5.75    6.07
Boundary for River Rch & Prof#=RIVER-1,Reach-1         , 1
Up Type= 0
Dn Type= 3
Dn Slope=.036
Boundary for River Rch & Prof#=RIVER-1,Reach-1         , 2
Up Type= 0
Dn Type= 3
Dn Slope=.036
Boundary for River Rch & Prof#=RIVER-1,Reach-1         , 3
Up Type= 0
Dn Type= 3
Dn Slope=.036
Boundary for River Rch & Prof#=RIVER-1,Reach-1         , 4
Up Type= 0
Dn Type= 3
Dn Slope=.036
Boundary for River Rch & Prof#=RIVER-1,Reach-1         , 5
Up Type= 0
Dn Type= 3
Dn Slope=.036
DSS Import GetInterval= 0
DSS Import GetPeak= 0
DSS Import FillOption= 0

--- BSC.g01 (geometry) ---

Geom Title=Imported Geom 01
Version=Version 3.0.1  Mar 2001

River Reach=RIVER-1         ,Reach-1
Reach XY= 2
              .5             .95              .5             .05

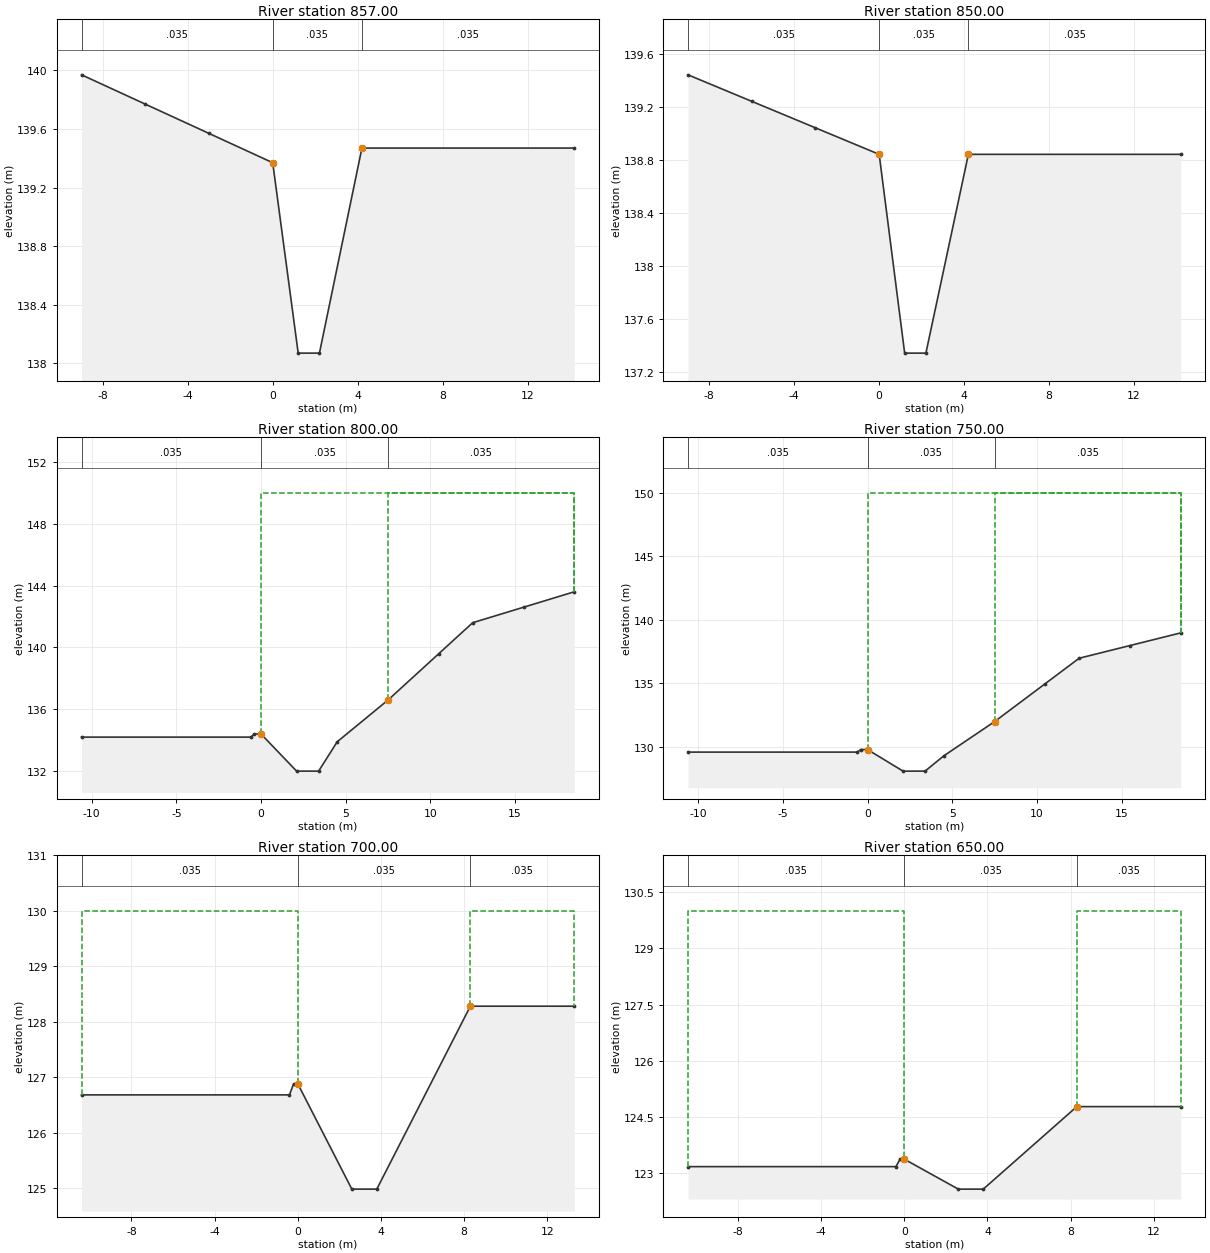
Type RM Length L Ch R = 1 ,857.00  ,7,7,7
BEGIN DESCRIPTION:
17.007
END DESCRIPTION:
#Sta/Elev= 8
      -9  139.97      -6  139.77      -3  139.57       0  139.37     1.2  138.07
     2.2  138.07     4.2  139.47    14.2  139.47
#Mann= 3 , 0 , 0
      -9    .035       0       0    .035       0     4.2    .035       0
#XS Ineff= 2 , 0
       0       0     150     4.2       0     150
Permanent Ineff=
       F       F
#Block Obstruct= 2 , 0
                             4.2
Bank Sta=0,4.2
XS Rating Curve= 0
Exp/Cntr=.3,.1

Type RM Length L Ch R = 1 ,850.00  ,50,50,50
BEGIN DESCRIPTION:
17
END DESCRIPTION:
#Sta/Elev= 8
      -9  139.44      -6  139.24      -3  139.04       0  138.84     1.2  137.34
     2.2  137.34     4.2  138.84    14.2  138.84
#Mann= 3 , 0 , 0
      -9    .035       0       0    .035       0     4.2    .035       0
#XS Ineff= 2 , 0
       0       0     150     4.2       0     150
Permanent Ineff=
       F       F
#Block Obstruct= 2 , 0
                             4.2
Bank Sta=0,4.2
XS Rating Curve= 0
Exp/Cntr=.3,.1

Type RM Length L Ch R = 1 ,800.00  ,50,50,50
BEGIN DESCRIPTION:
16
END DESCRIPTION:
#Sta/Elev= 12
   -10.6   134.2     -.6   134.2     -.4   134.4       0   134.4     2.1     132
     3.4     132     4.5   133.9     7.5   136.6    10.5   139.6    12.5   141.6
    15.5   142.6    18.5   143.6
#Mann= 3 , 0 , 0
   -10.6    .035       0       0    .035       0     7.5    .035       0
#XS Ineff= 2 , 0
       0       0     150     7.5       0     150
Permanent Ineff=
       F       F
#Block Obstruct= 2 , 0
                             7.5
Bank Sta=0,7.5
XS Rating Curve= 0
Exp/Cntr=.3,.1

Type RM Length L Ch R = 1 ,750.00  ,50,50,50
BEGIN DESCRIPTION:
15
END DESCRIPTION:
#Sta/Elev= 12
   -10.6  129.56     -.6  129.56     -.4  129.76       0  129.76     2.1  128.06
     3.4  128.06     4.5  129.26     7.5  131.96    10.5  134.96    12.5  136.96
    15.5  137.96    18.5  138.96
#Mann= 3 , 0 , 0
   -10.6    .035       0       0    .035       0     7.5    .035       0
#XS Ineff= 2 , 0
       0       0     150     7.5       0     150
Permanent Ineff=
       F       F
#Block Obstruct= 2 , 0
                             7.5
Bank Sta=0,7.5
XS Rating Curve= 0
Exp/Cntr=.3,.1

Type RM Length L Ch R = 1 ,700.00  ,50,50,50
BEGIN DESCRIPTION:
14
END DESCRIPTION:
#Sta/Elev= 8
   -10.4  126.68     -.4  126.68     -.2  126.88       0  126.88     2.6  124.98
     3.8  124.98     8.3  128.28    13.3  128.28
#Mann= 3 , 0 , 0
   -10.4    .035       0       0    .035       0     8.3    .035       0
#XS Ineff= 2 , 0
               0     130     8.3             130
Permanent Ineff=
       F       F
#Block Obstruct= 2 , 0
                             8.3
Bank Sta=0,8.3
XS Rating Curve= 0
Exp/Cntr=.3,.1

Type RM Length L Ch R = 1 ,650.00  ,29,29,29
BEGIN DESCRIPTION:
13
END DESCRIPTION:
#Sta/Elev= 8
   -10.4  123.18     -.4  123.18     -.2  123.38       0  123.38     2.6  122.58
     3.8  122.58     8.3  124.78    13.3  124.78
#Mann= 3 , 0 , 0
   -10.4    .035       0       0    .035       0     8.3    .035       0
#XS Ineff= 2 , 0
               0     130     8.3             130
Permanent Ineff=
       F       F
#Block Obstruct= 2 , 0
                             8.3
Bank Sta=0,8.3
XS Rating Curve= 0
Exp/Cntr=.3,.1

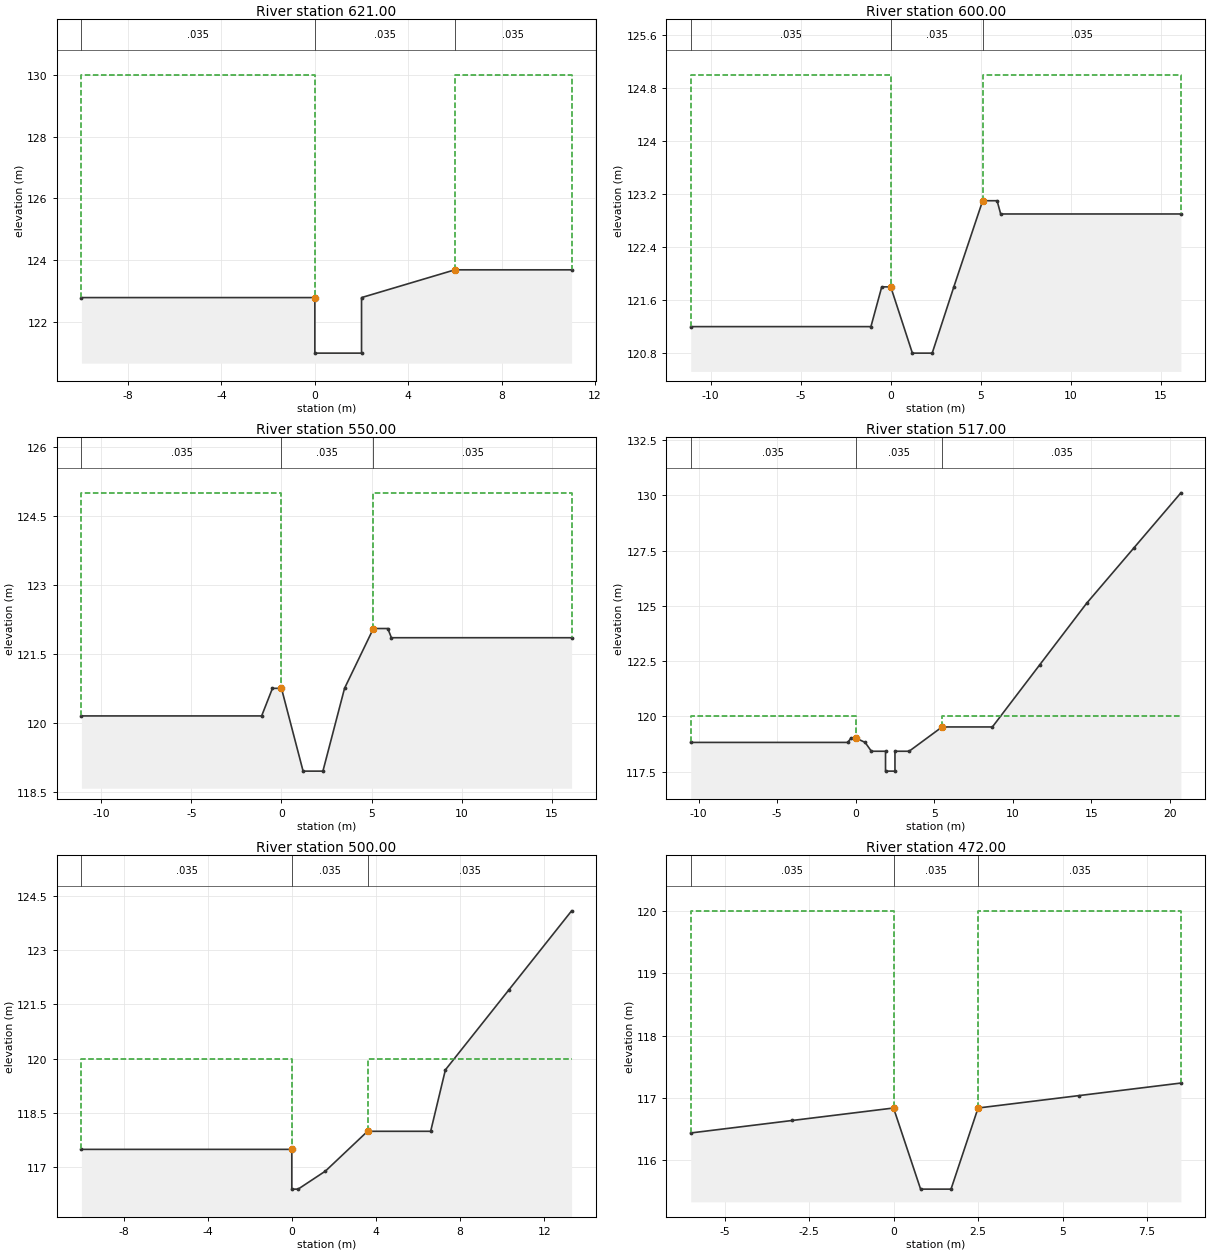
Type RM Length L Ch R = 1 ,621.00  ,21,21,21
BEGIN DESCRIPTION:
12.021
END DESCRIPTION:
#Sta/Elev= 7
     -10  122.78       0  122.78       0  120.98       2  120.98       2  122.78
       6  123.68      11  123.68
#Mann= 3 , 0 , 0
     -10    .035       0       0    .035       0       6    .035       0
#XS Ineff= 2 , 0
               0     130       6             130
Permanent Ineff=
       F       F
#Block Obstruct= 2 , 0
                               6
Bank Sta=0,6
XS Rating Curve= 0
Exp/Cntr=.3,.1

Type RM Length L Ch R = 1 ,600.00  ,50,50,50
BEGIN DESCRIPTION:
12
END DESCRIPTION:
#Sta/Elev= 11
   -11.1   121.2    -1.1   121.2     -.5   121.8       0   121.8     1.2   120.8
     2.3   120.8     3.5   121.8     5.1   123.1     5.9   123.1     6.1   122.9
    16.1   122.9
#Mann= 3 , 0 , 0
   -11.1    .035       0       0    .035       0     5.1    .035       0
#XS Ineff= 2 , 0
               0     125     5.1             125
Permanent Ineff=
       F       F
#Block Obstruct= 2 , 0
                             5.1
Bank Sta=0,5.1
XS Rating Curve= 0
Exp/Cntr=.3,.1

Type RM Length L Ch R = 1 ,550.00  ,33,33,33
BEGIN DESCRIPTION:
11
END DESCRIPTION:
#Sta/Elev= 11
   -11.1  120.15    -1.1  120.15     -.5  120.75       0  120.75     1.2  118.95
     2.3  118.95     3.5  120.75     5.1  122.05     5.9  122.05     6.1  121.85
    16.1  121.85
#Mann= 3 , 0 , 0
   -11.1    .035       0       0    .035       0     5.1    .035       0
#XS Ineff= 2 , 0
               0     125     5.1             125
Permanent Ineff=
       F       F
#Block Obstruct= 2 , 0
                             5.1
Bank Sta=0,5.1
XS Rating Curve= 0
Exp/Cntr=.3,.1

Type RM Length L Ch R = 1 ,517.00  ,17,17,17
BEGIN DESCRIPTION:
10.017
END DESCRIPTION:
#Sta/Elev= 17
   -10.5  118.82     -.5  118.82     -.3  119.02       0  119.02      .6  118.82
       1  118.42     1.9  118.42     1.9  117.52     2.5  117.52     2.5  118.42
     3.4  118.42     5.5  119.52     8.7  119.52    11.7  122.32    14.7  125.12
    17.7  127.62    20.7  130.12
#Mann= 3 , 0 , 0
   -10.5    .035       0       0    .035       0     5.5    .035       0
#XS Ineff= 2 , 0
               0     120     5.5             120
Permanent Ineff=
       F       F
#Block Obstruct= 2 , 0
                             5.5
Bank Sta=0,5.5
XS Rating Curve= 0
Exp/Cntr=.3,.1

Type RM Length L Ch R = 1 ,500.00  ,28,28,28
BEGIN DESCRIPTION:
10
END DESCRIPTION:
#Sta/Elev= 10
     -10  117.49       0  117.49       0  116.39      .3  116.39     1.6  116.89
     3.6  117.99     6.6  117.99     7.3  119.69    10.3  121.89    13.3  124.09
#Mann= 3 , 0 , 0
     -10    .035       0       0    .035       0     3.6    .035       0
#XS Ineff= 2 , 0
               0     120     3.6             120
Permanent Ineff=
       F       F
#Block Obstruct= 2 , 0
                             3.6
Bank Sta=0,3.6
XS Rating Curve= 0
Exp/Cntr=.3,.1

Type RM Length L Ch R = 1 ,472.00  ,22,22,22
BEGIN DESCRIPTION:
9.022
END DESCRIPTION:
#Sta/Elev= 8
      -6  116.44      -3  116.64       0  116.84      .8  115.54     1.7  115.54
     2.5  116.84     5.5  117.04     8.5  117.24
#Mann= 3 , 0 , 0
      -6    .035       0       0    .035       0     2.5    .035       0
#XS Ineff= 2 , 0
               0     120     2.5             120
Permanent Ineff=
       F       F
#Block Obstruct= 2 , 0
                             2.5
Bank Sta=0,2.5
XS Rating Curve= 0
Exp/Cntr=.3,.1

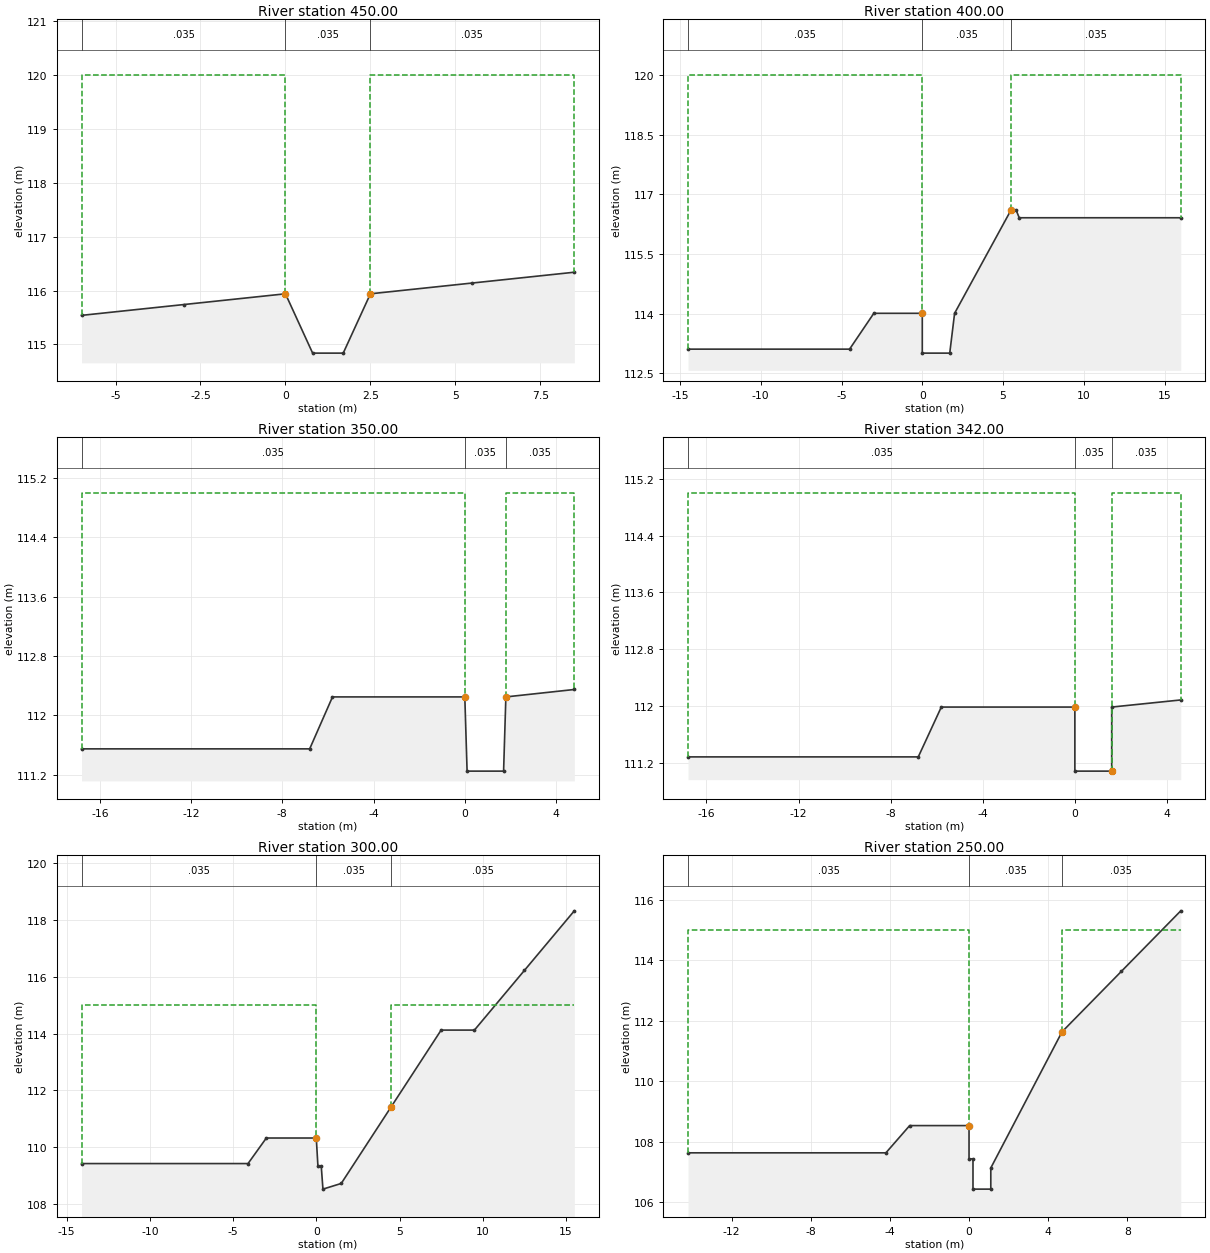
Type RM Length L Ch R = 1 ,450.00  ,50,50,50
BEGIN DESCRIPTION:
9
END DESCRIPTION:
#Sta/Elev= 8
      -6  115.54      -3  115.74       0  115.94      .8  114.84     1.7  114.84
     2.5  115.94     5.5  116.14     8.5  116.34
#Mann= 3 , 0 , 0
      -6    .035       0       0    .035       0     2.5    .035       0
#XS Ineff= 2 , 0
               0     120     2.5             120
Permanent Ineff=
       F       F
#Block Obstruct= 2 , 0
                             2.5
Bank Sta=0,2.5
XS Rating Curve= 0
Exp/Cntr=.3,.1

Type RM Length L Ch R = 1 ,400.00  ,50,50,50
BEGIN DESCRIPTION:
8
END DESCRIPTION:
#Sta/Elev= 11
   -14.5  113.11    -4.5  113.11      -3  114.01       0  114.01       0  113.01
     1.7  113.01       2  114.01     5.5  116.61     5.8  116.61       6  116.41
      16  116.41
#Mann= 3 , 0 , 0
   -14.5    .035       0       0    .035       0     5.5    .035       0
#XS Ineff= 2 , 0
               0     120     5.5             120
Permanent Ineff=
       F       F
#Block Obstruct= 2 , 0
                             5.5
Bank Sta=0,5.5
XS Rating Curve= 0
Exp/Cntr=.3,.1

Type RM Length L Ch R = 1 ,350.00  ,8,8,8
BEGIN DESCRIPTION:
7
END DESCRIPTION:
#Sta/Elev= 8
   -16.8  111.55    -6.8  111.55    -5.8  112.25       0  112.25      .1  111.25
     1.7  111.25     1.8  112.25     4.8  112.35
#Mann= 3 , 0 , 0
   -16.8    .035       0       0    .035       0     1.8    .035       0
#XS Ineff= 2 , 0
               0     115     1.8             115
Permanent Ineff=
       F       F
#Block Obstruct= 2 , 0
                             1.8
Bank Sta=0,1.8
XS Rating Curve= 0
Exp/Cntr=.3,.1

Type RM Length L Ch R = 1 ,342.00  ,42,42,42
BEGIN DESCRIPTION:
6.042
END DESCRIPTION:
#Sta/Elev= 8
   -16.8  111.29    -6.8  111.29    -5.8  111.99       0  111.99       0  111.09
     1.6  111.09     1.6  111.99     4.6  112.09
#Mann= 3 , 0 , 0
   -16.8    .035       0       0    .035       0     1.6    .035       0
#XS Ineff= 2 , 0
               0     115     1.6             115
Permanent Ineff=
       F       F
#Block Obstruct= 2 , 0
                             1.6
Bank Sta=0,1.6
XS Rating Curve= 0
Exp/Cntr=.3,.1

Type RM Length L Ch R = 1 ,300.00  ,50,50,50
BEGIN DESCRIPTION:
6
END DESCRIPTION:
#Sta/Elev= 13
   -14.1  109.42    -4.1  109.42      -3  110.32       0  110.32      .1  109.32
      .3  109.32      .4  108.52     1.5  108.72     4.5  111.42     7.5  114.12
     9.5  114.12    12.5  116.22    15.5  118.32
#Mann= 3 , 0 , 0
   -14.1    .035       0       0    .035       0     4.5    .035       0
#XS Ineff= 2 , 0
               0     115     4.5             115
Permanent Ineff=
       F       F
#Block Obstruct= 2 , 0
                             4.5
Bank Sta=0,4.5
XS Rating Curve= 0
Exp/Cntr=.3,.1

Type RM Length L Ch R = 1 ,250.00  ,50,50,50
BEGIN DESCRIPTION:
5
END DESCRIPTION:
#Sta/Elev= 12
   -14.2  107.64    -4.2  107.64      -3  108.54       0  108.54       0  107.44
      .2  107.44      .2  106.44     1.1  106.44     1.1  107.14     4.7  111.64
     7.7  113.64    10.7  115.64
#Mann= 3 , 0 , 0
   -14.2    .035       0       0    .035       0     4.7    .035       0
#XS Ineff= 2 , 0
               0     115     4.7             115
Permanent Ineff=
       F       F
#Block Obstruct= 2 , 0
                             4.7
Bank Sta=0,4.7
XS Rating Curve= 0
Exp/Cntr=.3,.1

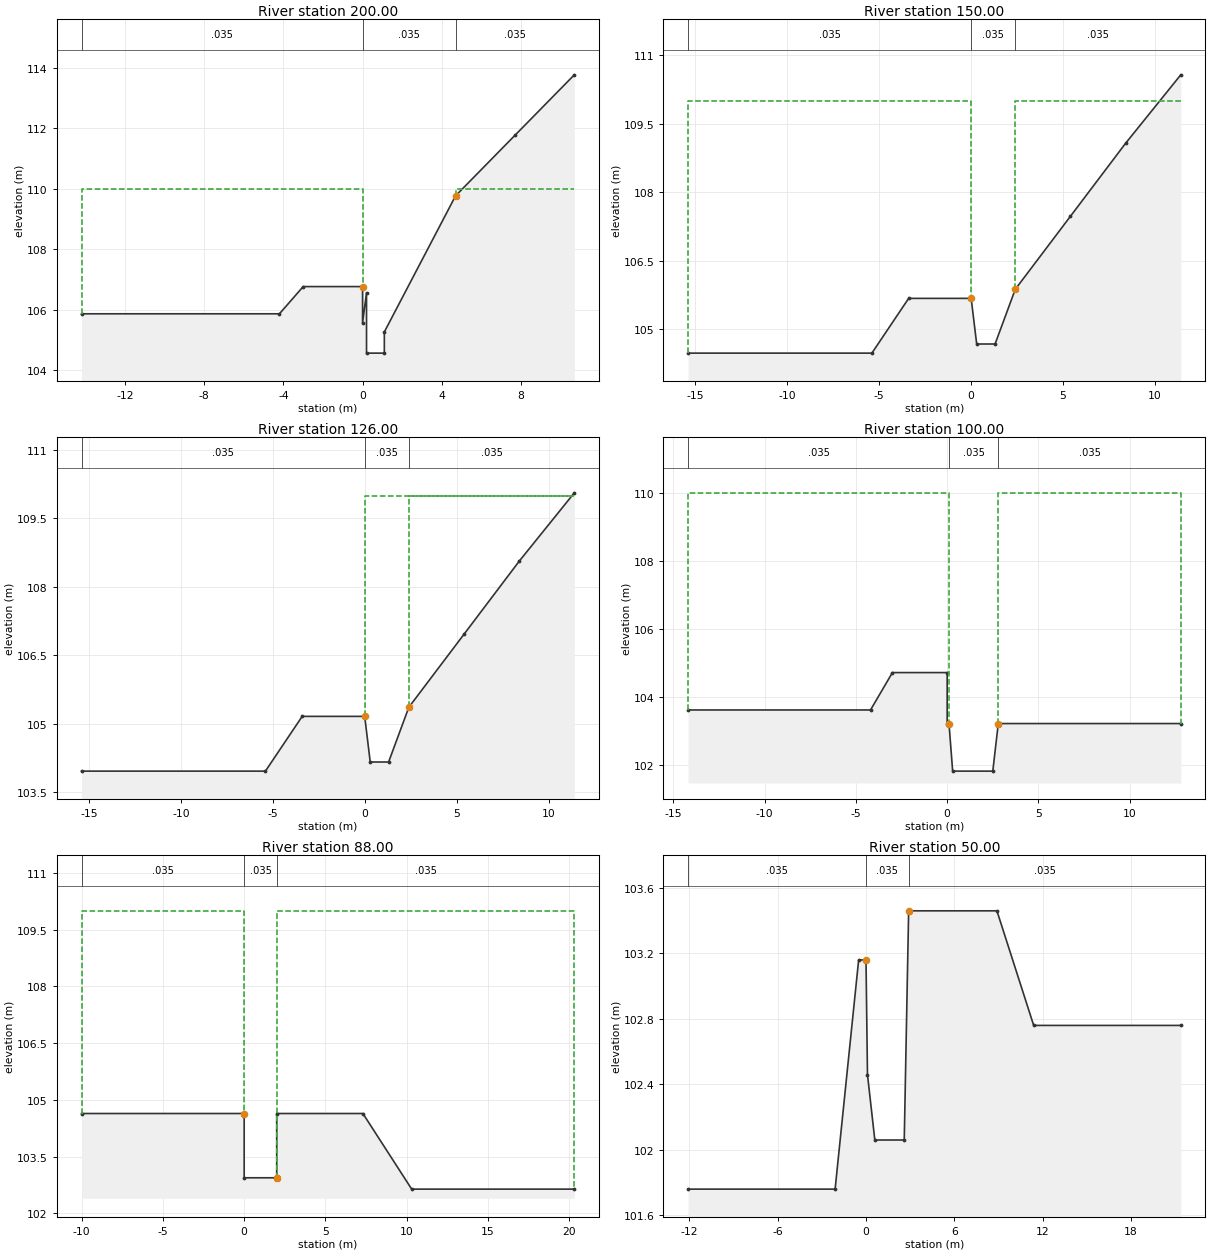
Type RM Length L Ch R = 1 ,200.00  ,50,50,50
BEGIN DESCRIPTION:
4
END DESCRIPTION:
#Sta/Elev= 12
   -14.2  105.86    -4.2  105.86      -3  106.76       0  106.76       0  105.56
      .2  106.56      .2  104.56     1.1  104.56     1.1  105.26     4.7  109.76
     7.7  111.76    10.7  113.76
#Mann= 3 , 0 , 0
   -14.2    .035       0       0    .035       0     4.7    .035       0
#XS Ineff= 2 , 0
               0     110     4.7             110
Permanent Ineff=
       F       F
#Block Obstruct= 2 , 0
                             4.7
Bank Sta=0,4.7
XS Rating Curve= 0
Exp/Cntr=.3,.1

Type RM Length L Ch R = 1 ,150.00  ,24,24,24
BEGIN DESCRIPTION:
3
END DESCRIPTION:
#Sta/Elev= 10
   -15.4  104.47    -5.4  104.47    -3.4  105.67       0  105.67      .3  104.67
     1.3  104.67     2.4  105.87     5.4  107.47     8.4  109.07    11.4  110.57
#Mann= 3 , 0 , 0
   -15.4    .035       0       0    .035       0     2.4    .035       0
#XS Ineff= 2 , 0
               0     110     2.4             110
Permanent Ineff=
       F       F
#Block Obstruct= 2 , 0
                             2.4
Bank Sta=0,2.4
XS Rating Curve= 0
Exp/Cntr=.3,.1

Type RM Length L Ch R = 1 ,126.00  ,26,26,26
BEGIN DESCRIPTION:
2.026
END DESCRIPTION:
#Sta/Elev= 10
   -15.4  103.96    -5.4  103.96    -3.4  105.16       0  105.16      .3  104.16
     1.3  104.16     2.4  105.36     5.4  106.96     8.4  108.56    11.4  110.06
#Mann= 3 , 0 , 0
   -15.4    .035       0       0    .035       0     2.4    .035       0
#XS Ineff= 2 , 0
       0       0     110     2.4       0     110
Permanent Ineff=
       F       F
#Block Obstruct= 2 , 0
                             2.4
Bank Sta=0,2.4
XS Rating Curve= 0
Exp/Cntr=.3,.1

Type RM Length L Ch R = 1 ,100.00  ,12,12,12
BEGIN DESCRIPTION:
2
END DESCRIPTION:
#Sta/Elev= 10
   -14.2  103.61    -4.2  103.61      -3  104.71       0  104.71       0  103.21
      .1  103.21      .3  101.81     2.5  101.81     2.8  103.21    12.8  103.21
#Mann= 3 , 0 , 0
   -14.2    .035       0      .1    .035       0     2.8    .035       0
#XS Ineff= 2 , 0
              .1     110     2.8             110
Permanent Ineff=
       F       F
#Block Obstruct= 2 , 0
              .1             2.8
Bank Sta=.1,2.8
XS Rating Curve= 0
Exp/Cntr=.3,.1

Type RM Length L Ch R = 1 ,88.00   ,38,38,38
BEGIN DESCRIPTION:
1.038
END DESCRIPTION:
#Sta/Elev= 8
     -10  104.64       0  104.64       0  102.94       2  102.94       2  104.64
     7.3  104.64    10.3  102.64    20.3  102.64
#Mann= 3 , 0 , 0
     -10    .035       0       0    .035       0       2    .035       0
#XS Ineff= 2 , 0
               0     110       2             110
Permanent Ineff=
       F       F
#Block Obstruct= 2 , 0
                               2
Bank Sta=0,2
XS Rating Curve= 0
Exp/Cntr=.3,.1

Type RM Length L Ch R = 1 ,50.00   ,48,48,48
BEGIN DESCRIPTION:
1
END DESCRIPTION:
#Sta/Elev= 11
   -12.1  101.76    -2.1  101.76     -.5  103.16       0  103.16      .1  102.46
      .6  102.06     2.6  102.06     2.9  103.46     8.9  103.46    11.4  102.76
    21.4  102.76
#Mann= 3 , 0 , 0
   -12.1    .035       0       0    .035       0     2.9    .035       0
#XS Ineff= 2 , 0
               0     110     2.9             110
Permanent Ineff=
       F       F
#Block Obstruct= 2 , 0
                             2.9
Bank Sta=0,2.9
XS Rating Curve= 0
Exp/Cntr=.3,.1

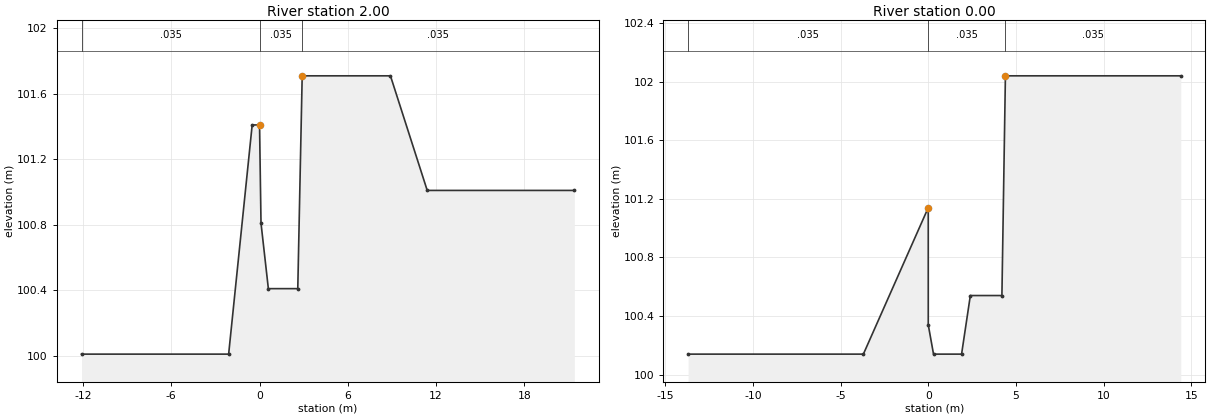
Type RM Length L Ch R = 1 ,2.00    ,2,2,2
BEGIN DESCRIPTION:
0.002
END DESCRIPTION:
#Sta/Elev= 11
   -12.1  100.01    -2.1  100.01     -.5  101.41       0  101.41      .1  100.81
      .6  100.41     2.6  100.41     2.9  101.71     8.9  101.71    11.4  101.01
    21.4  101.01
#Mann= 3 , 0 , 0
   -12.1    .035       0       0    .035       0     2.9    .035       0
#XS Ineff= 2 , 0
               0     110     2.9             110
Permanent Ineff=
       F       F
#Block Obstruct= 2 , 0
                             2.9
Bank Sta=0,2.9
XS Rating Curve= 0
Exp/Cntr=.3,.1

Type RM Length L Ch R = 1 ,0.00    ,0,0,0
BEGIN DESCRIPTION:
0
END DESCRIPTION:
#Sta/Elev= 10
   -13.7  100.14    -3.7  100.14       0  101.14       0  100.34      .3  100.14
     1.9  100.14     2.4  100.54     4.2  100.54     4.4  102.04    14.4  102.04
#Mann= 3 , 0 , 0
   -13.7    .035       0       0    .035       0     4.4    .035       0
#XS Ineff= 2 , 0
               0     110     4.4             110
Permanent Ineff=
       F       F
#Block Obstruct= 2 , 0
                             4.4
Bank Sta=0,4.4
XS Rating Curve= 0
Exp/Cntr=.3,.1

Chan Stop Cuts=-1