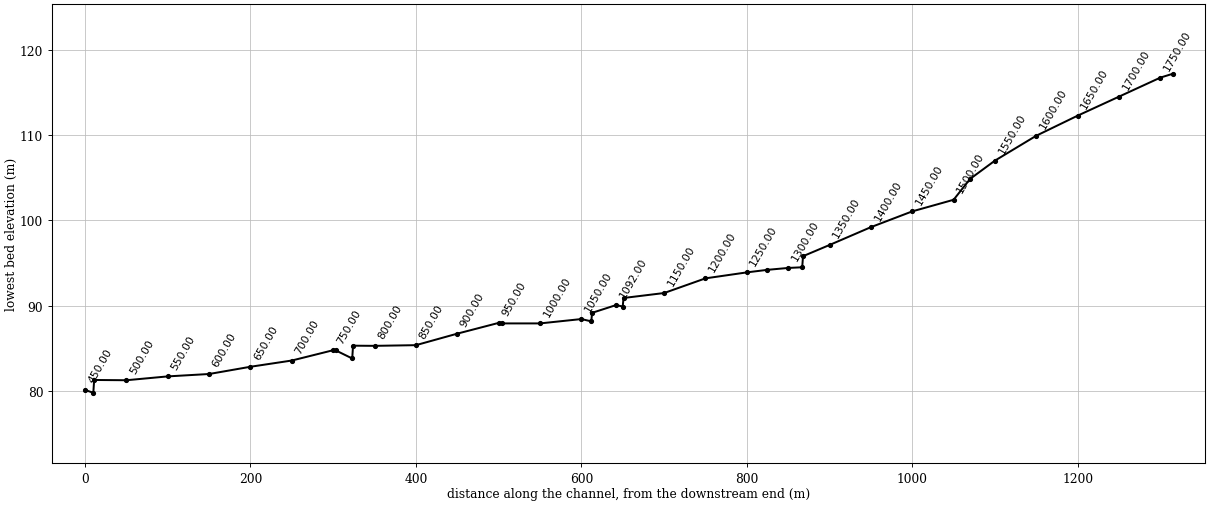
--- EUM.prj (project) ---

Proj Title=EUM
Current Plan=p01
Default Exp/Contr=.3,.1
SI Units
Geom File=g01
Flow File=f01
Plan File=p01
Y Axis Title=Elevation
X Axis Title(PF)=Main Channel Distance
X Axis Title(XS)=Station
BEGIN DESCRIPTION:
           BACK WATER COMPUTATION
      APPLICATION OF HEC-2 BY Samju Construction Engineering
      eumhyun-ch: 10,20,30,50,80 yr
END DESCRIPTION:
DSS Export Rating Curves= 0
DSS Export Rating Curve Sorted= 0
DSS Export Volume Flow Curves= 0
DXF OffsetX= 0
DXF OffsetY= 0
DXF ScaleX= 1
DXF ScaleY= 10

--- EUM.p01 (plan) ---

Plan Title=Imported Plan 01
Version=Version 3.0.1  Mar 2001
Short Identifier=Imported Pla
Geom File=g01
Flow File=f01
Subcritical Flow
K Sum by GR= 0
Std Step Tol= 0.003
Critical Tol= 0.003
Num of Std Step Trials= 20
Max Error Tol= 0.1
Flow Tol Ratio= 0.001
Split Flow NTrial= 30
Split Flow Tol= 0.02
Split Flow Ratio= 0.02
Log Output Level= 0
Friction Slope Method= 1
Unsteady Friction Slope Method= 2
Parabolic Critical Depth
Global Vel Dist= 0 , 0 , 0
Global Log Level= 0
CheckData=True
Encroach Param=-1 ,0,0, 0
Computation Interval=1HOUR
Output Interval=1HOUR
Run HTab= 0
Run UNet= 0
Run PostProcess= 0
UNET Theta= 1
UNET ZTol= 0.02
UNET ZSATol= 0.1
UNET MxIter= 20
UNET MaxInSteps= 20
UNET DtIC= 0
UNET DtMin= 0
UNET MaxCRTS= 20
UNET WFStab= 2
UNET SFStab= 1
UNET WFX= 1
UNET SFX= 1
UNET Convert EG Bridges=-1
UNET Use Existing IB Tables=-1
Instantaneous Interval=1HOUR
Write IC File= 0
Write Velocity= 0
Write Detailed= 0

--- EUM.f01 (steady flow) ---

Flow Title=Imported Flow 01
Version=Version 3.0.1  Mar 2001
Number of Profiles= 5
Profile Names=10YR,20YR,30YR,50YR,80YR
River Rch & RM=RIVER-1,Reach-1         ,1765.00
   13.85   15.26   16.08   17.11   18.06
River Rch & RM=RIVER-1,Reach-1         ,1000.00
   22.93   25.27   26.63   28.35   29.94
Boundary for River Rch & Prof#=RIVER-1,Reach-1         , 1
Up Type= 0
Dn Type= 3
Dn Slope=.03
Boundary for River Rch & Prof#=RIVER-1,Reach-1         , 2
Up Type= 0
Dn Type= 3
Dn Slope=.03
Boundary for River Rch & Prof#=RIVER-1,Reach-1         , 3
Up Type= 0
Dn Type= 3
Dn Slope=.03
Boundary for River Rch & Prof#=RIVER-1,Reach-1         , 4
Up Type= 0
Dn Type= 3
Dn Slope=.03
Boundary for River Rch & Prof#=RIVER-1,Reach-1         , 5
Up Type= 0
Dn Type= 3
Dn Slope=.03
DSS Import GetInterval= 0
DSS Import GetPeak= 0
DSS Import FillOption= 0

--- EUM.g01 (geometry) ---

Geom Title=Imported Geom 01
Version=Version 3.0.1  Mar 2001

River Reach=RIVER-1         ,Reach-1
Reach XY= 2
              .5             .95              .5             .05

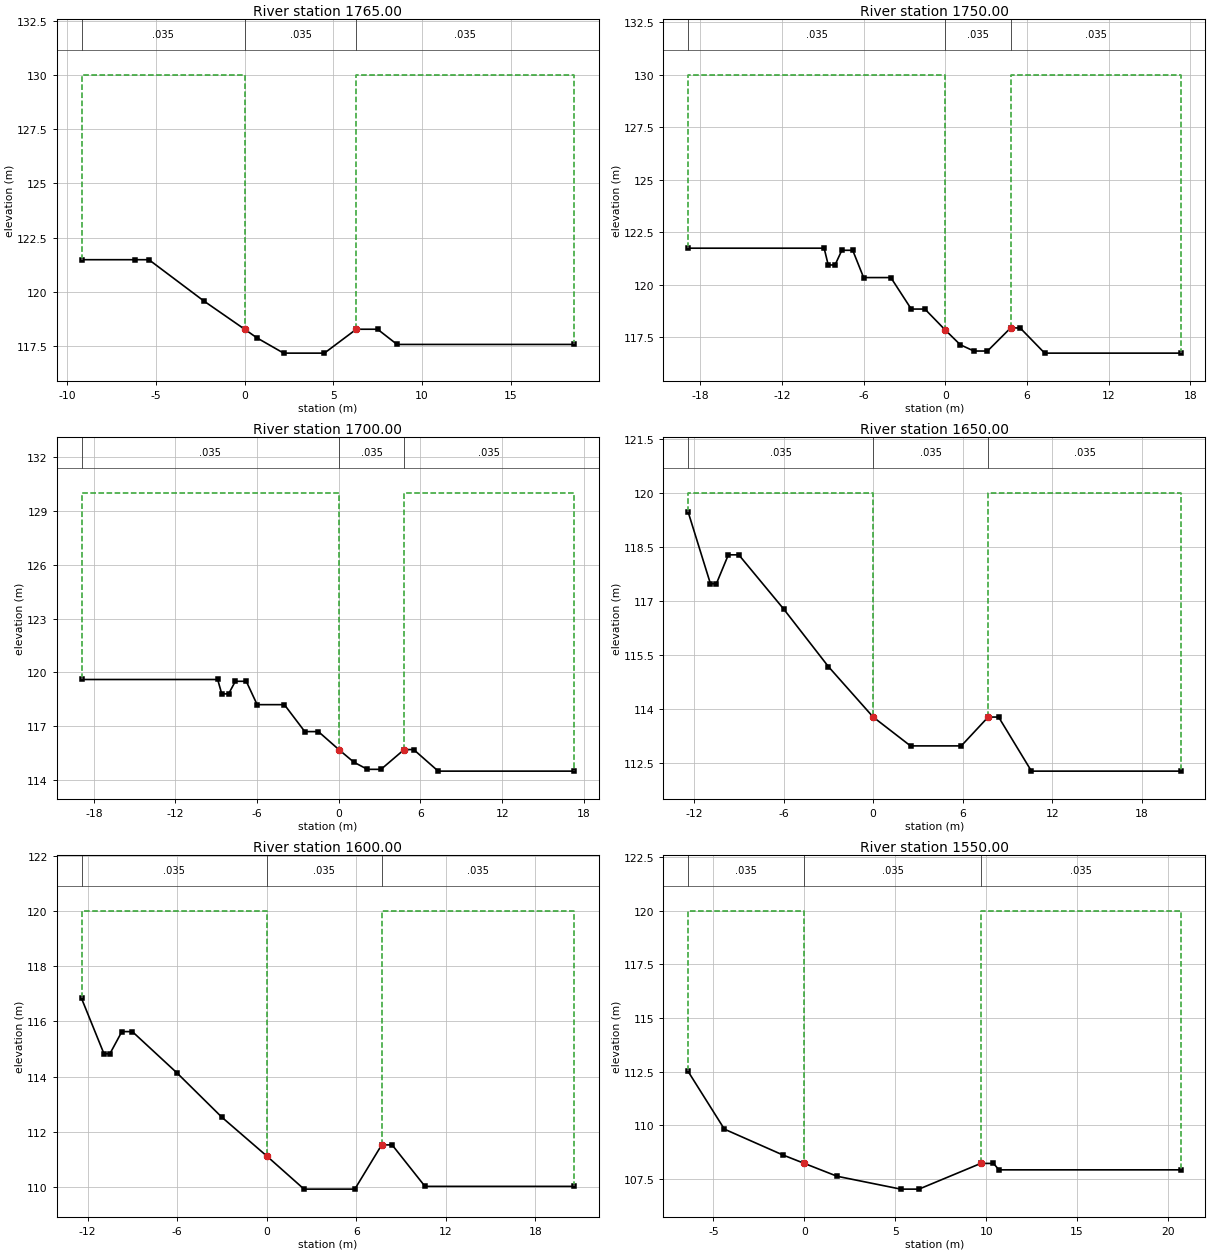
Type RM Length L Ch R = 1 ,1765.00 ,15,15,15
BEGIN DESCRIPTION:
35.015
END DESCRIPTION:
#Sta/Elev= 12
    -9.2  121.49    -6.2  121.49    -5.4  121.49    -2.3  119.59       0  118.29
      .7  117.89     2.2  117.19     4.5  117.19     6.3  118.29     7.5  118.29
     8.6  117.59    18.6  117.59
#Mann= 3 , 0 , 0
    -9.2    .035       0       0    .035       0     6.3    .035       0
#XS Ineff= 2 , 0
               0     130     6.3             130
Permanent Ineff=
       F       F
#Block Obstruct= 2 , 0
                             6.3
Bank Sta=0,6.3
XS Rating Curve= 0
Exp/Cntr=.3,.1

Type RM Length L Ch R = 1 ,1750.00 ,50,50,50
BEGIN DESCRIPTION:
35
END DESCRIPTION:
#Sta/Elev= 18
   -18.9  121.74    -8.9  121.74    -8.6  120.94    -8.1  120.94    -7.6  121.64
    -6.8  121.64      -6  120.34      -4  120.34    -2.5  118.84    -1.5  118.84
       0  117.84     1.1  117.14     2.1  116.84     3.1  116.84     4.8  117.94
     5.5  117.94     7.3  116.74    17.3  116.74
#Mann= 3 , 0 , 0
   -18.9    .035       0       0    .035       0     4.8    .035       0
#XS Ineff= 2 , 0
               0     130     4.8             130
Permanent Ineff=
       F       F
#Block Obstruct= 2 , 0
                             4.8
Bank Sta=0,4.8
XS Rating Curve= 0
Exp/Cntr=.3,.1

Type RM Length L Ch R = 1 ,1700.00 ,50,50,50
BEGIN DESCRIPTION:
34
END DESCRIPTION:
#Sta/Elev= 18
   -18.9  119.61    -8.9  119.61    -8.6  118.81    -8.1  118.81    -7.6  119.51
    -6.8  119.51      -6  118.21      -4  118.21    -2.5  116.71    -1.5  116.71
       0  115.71     1.1  115.01     2.1  114.61     3.1  114.61     4.8  115.71
     5.5  115.71     7.3  114.51    17.3  114.51
#Mann= 3 , 0 , 0
   -18.9    .035       0       0    .035       0     4.8    .035       0
#XS Ineff= 2 , 0
               0     130     4.8             130
Permanent Ineff=
       F       F
#Block Obstruct= 2 , 0
                             4.8
Bank Sta=0,4.8
XS Rating Curve= 0
Exp/Cntr=.3,.1

Type RM Length L Ch R = 1 ,1650.00 ,50,50,50
BEGIN DESCRIPTION:
33
END DESCRIPTION:
#Sta/Elev= 14
   -12.4  119.48   -10.9  117.48   -10.5  117.48    -9.7  118.28      -9  118.28
      -6  116.78      -3  115.18       0  113.78     2.5  112.98     5.9  112.98
     7.7  113.78     8.4  113.78    10.6  112.28    20.6  112.28
#Mann= 3 , 0 , 0
   -12.4    .035       0       0    .035       0     7.7    .035       0
#XS Ineff= 2 , 0
               0     120     7.7             120
Permanent Ineff=
       F       F
#Block Obstruct= 2 , 0
                             7.7
Bank Sta=0,7.7
XS Rating Curve= 0
Exp/Cntr=.3,.1

Type RM Length L Ch R = 1 ,1600.00 ,50,50,50
BEGIN DESCRIPTION:
32
END DESCRIPTION:
#Sta/Elev= 14
   -12.4  116.83   -10.9  114.83   -10.5  114.83    -9.7  115.63      -9  115.63
      -6  114.13      -3  112.53       0  111.13     2.5  109.93     5.9  109.93
     7.7  111.53     8.4  111.53    10.6  110.03    20.6  110.03
#Mann= 3 , 0 , 0
   -12.4    .035       0       0    .035       0     7.7    .035       0
#XS Ineff= 2 , 0
               0     120     7.7             120
Permanent Ineff=
       F       F
#Block Obstruct= 2 , 0
                             7.7
Bank Sta=0,7.7
XS Rating Curve= 0
Exp/Cntr=.3,.1

Type RM Length L Ch R = 1 ,1550.00 ,30,30,30
BEGIN DESCRIPTION:
31
END DESCRIPTION:
#Sta/Elev= 11
    -6.4  112.51    -4.4  109.81    -1.2  108.61       0  108.21     1.8  107.61
     5.3  107.01     6.3  107.01     9.7  108.21    10.4  108.21    10.7  107.91
    20.7  107.91
#Mann= 3 , 0 , 0
    -6.4    .035       0       0    .035       0     9.7    .035       0
#XS Ineff= 2 , 0
               0     120     9.7             120
Permanent Ineff=
       F       F
#Block Obstruct= 2 , 0
                             9.7
Bank Sta=0,9.7
XS Rating Curve= 0
Exp/Cntr=.3,.1

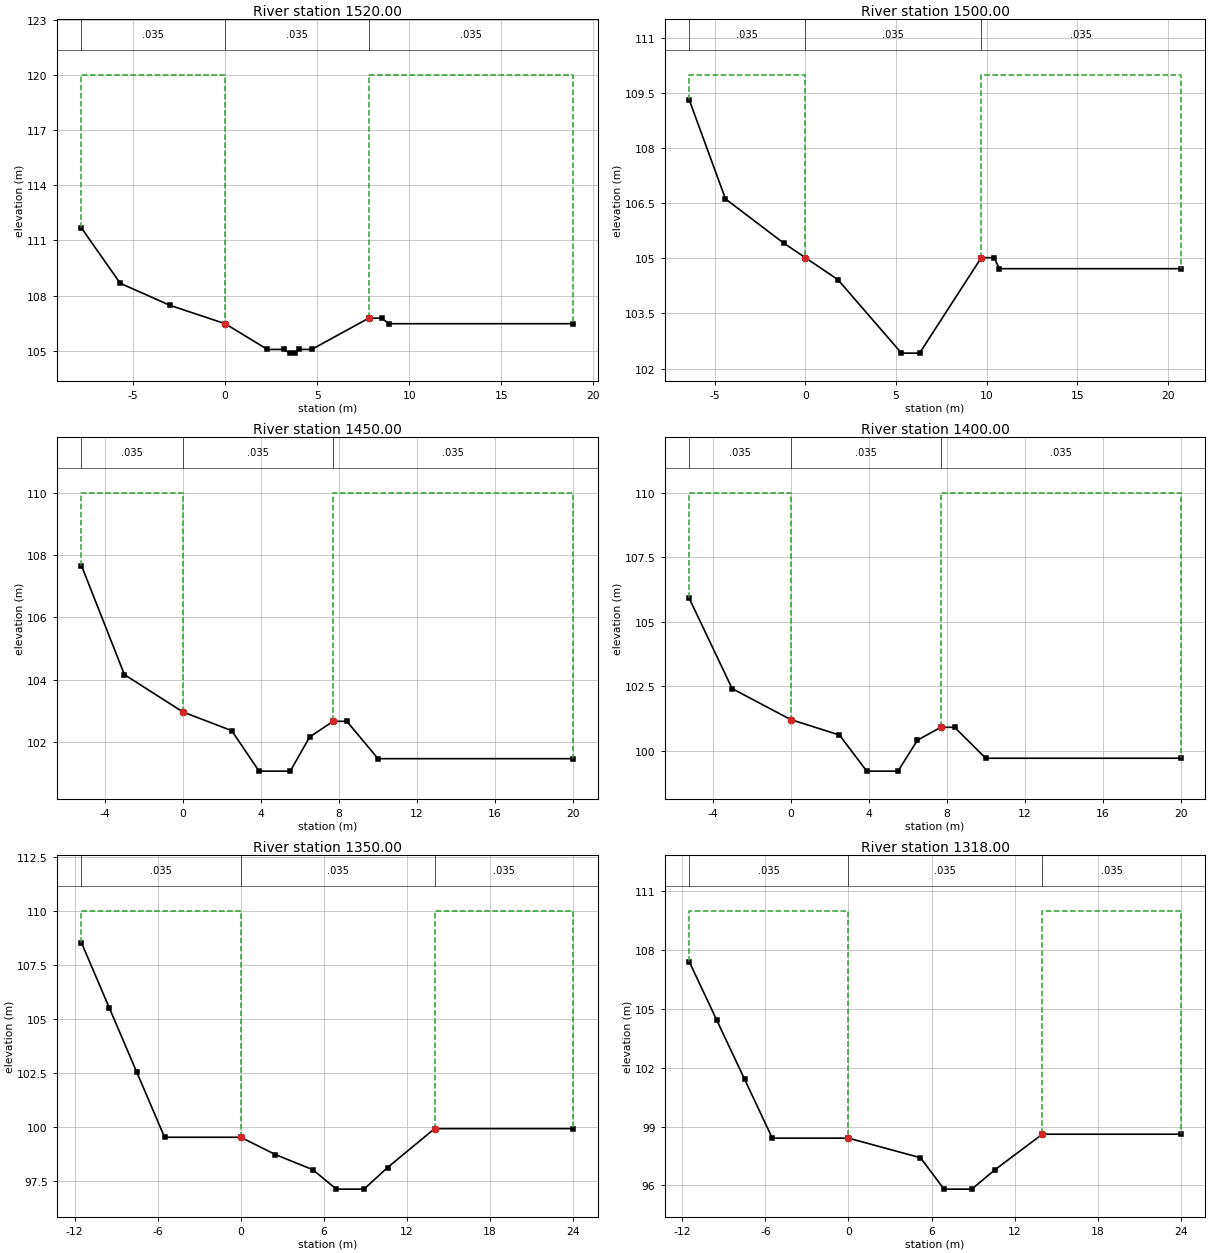
Type RM Length L Ch R = 1 ,1520.00 ,20,20,20
BEGIN DESCRIPTION:
30.02
END DESCRIPTION:
#Sta/Elev= 14
    -7.8  111.67    -5.7  108.67      -3  107.47       0  106.47     2.3  105.07
     3.2  105.07     3.5  104.87     3.8  104.87       4  105.07     4.7  105.07
     7.8  106.77     8.5  106.77     8.9  106.47    18.9  106.47
#Mann= 3 , 0 , 0
    -7.8    .035       0       0    .035       0     7.8    .035       0
#XS Ineff= 2 , 0
               0     120     7.8             120
Permanent Ineff=
       F       F
#Block Obstruct= 2 , 0
                             7.8
Bank Sta=0,7.8
XS Rating Curve= 0
Exp/Cntr=.3,.1

Type RM Length L Ch R = 1 ,1500.00 ,50,50,50
BEGIN DESCRIPTION:
30
END DESCRIPTION:
#Sta/Elev= 11
    -6.4  109.32    -4.4  106.62    -1.2  105.42       0  105.02     1.8  104.42
     5.3  102.42     6.3  102.42     9.7  105.02    10.4  105.02    10.7  104.72
    20.7  104.72
#Mann= 3 , 0 , 0
    -6.4    .035       0       0    .035       0     9.7    .035       0
#XS Ineff= 2 , 0
               0     110     9.7             110
Permanent Ineff=
       F       F
#Block Obstruct= 2 , 0
                             9.7
Bank Sta=0,9.7
XS Rating Curve= 0
Exp/Cntr=.3,.1

Type RM Length L Ch R = 1 ,1450.00 ,50,50,50
BEGIN DESCRIPTION:
29
END DESCRIPTION:
#Sta/Elev= 11
    -5.2  107.66      -3  104.16       0  102.96     2.5  102.36     3.9  101.06
     5.5  101.06     6.5  102.16     7.7  102.66     8.4  102.66      10  101.46
      20  101.46
#Mann= 3 , 0 , 0
    -5.2    .035       0       0    .035       0     7.7    .035       0
#XS Ineff= 2 , 0
               0     110     7.7             110
Permanent Ineff=
       F       F
#Block Obstruct= 2 , 0
                             7.7
Bank Sta=0,7.7
XS Rating Curve= 0
Exp/Cntr=.3,.1

Type RM Length L Ch R = 1 ,1400.00 ,50,50,50
BEGIN DESCRIPTION:
28
END DESCRIPTION:
#Sta/Elev= 11
    -5.2  105.91      -3  102.41       0  101.21     2.5  100.61     3.9   99.21
     5.5   99.21     6.5  100.41     7.7  100.91     8.4  100.91      10   99.71
      20   99.71
#Mann= 3 , 0 , 0
    -5.2    .035       0       0    .035       0     7.7    .035       0
#XS Ineff= 2 , 0
               0     110     7.7             110
Permanent Ineff=
       F       F
#Block Obstruct= 2 , 0
                             7.7
Bank Sta=0,7.7
XS Rating Curve= 0
Exp/Cntr=.3,.1

Type RM Length L Ch R = 1 ,1350.00 ,32,32,32
BEGIN DESCRIPTION:
27
END DESCRIPTION:
#Sta/Elev= 12
   -11.5  108.52    -9.5  105.52    -7.5  102.52    -5.5   99.52       0   99.52
     2.5   98.72     5.2   98.02     6.9   97.12     8.9   97.12    10.6   98.12
      14   99.92      24   99.92
#Mann= 3 , 0 , 0
   -11.5    .035       0       0    .035       0      14    .035       0
#XS Ineff= 2 , 0
               0     110      14             110
Permanent Ineff=
       F       F
#Block Obstruct= 2 , 0
                              14
Bank Sta=0,14
XS Rating Curve= 0
Exp/Cntr=.3,.1

Type RM Length L Ch R = 1 ,1318.00 ,1,1,1
BEGIN DESCRIPTION:
26.018
END DESCRIPTION:
#Sta/Elev= 11
   -11.5  107.41    -9.5  104.41    -7.5  101.41    -5.5   98.41       0   98.41
     5.2   97.41     6.9   95.81     8.9   95.81    10.6   96.81      14   98.61
      24   98.61
#Mann= 3 , 0 , 0
   -11.5    .035       0       0    .035       0      14    .035       0
#XS Ineff= 2 , 0
               0     110      14             110
Permanent Ineff=
       F       F
#Block Obstruct= 2 , 0
                              14
Bank Sta=0,14
XS Rating Curve= 0
Exp/Cntr=.3,.1

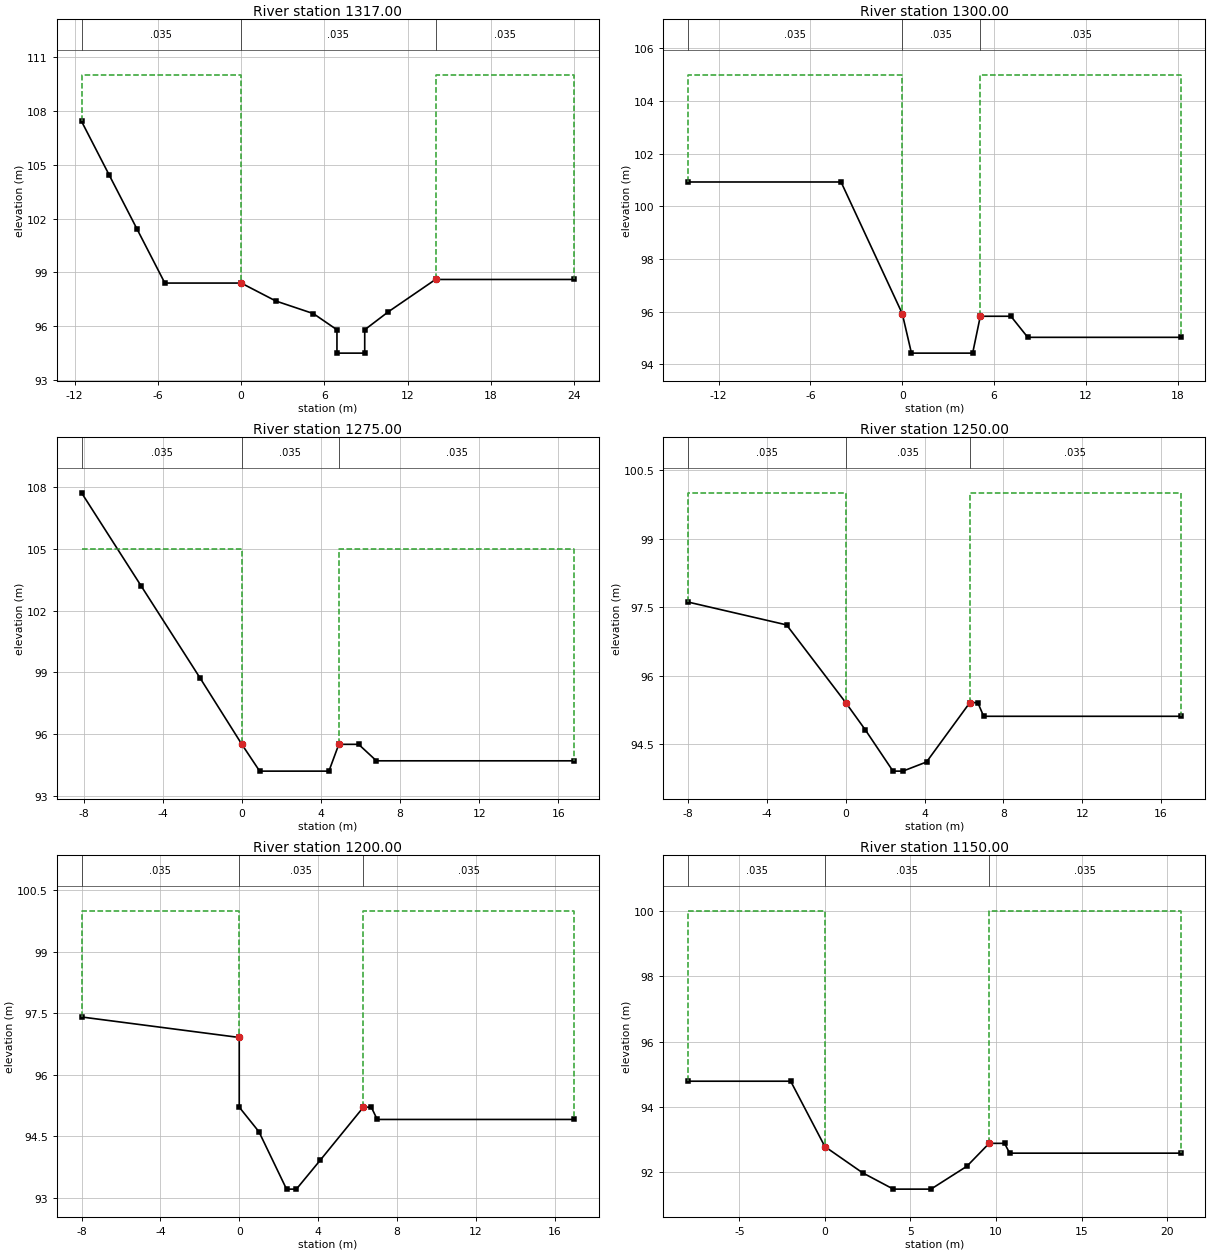
Type RM Length L Ch R = 1 ,1317.00 ,17,17,17
BEGIN DESCRIPTION:
26.017
END DESCRIPTION:
#Sta/Elev= 14
   -11.5  107.41    -9.5  104.41    -7.5  101.41    -5.5   98.41       0   98.41
     2.5   97.41     5.2   96.71     6.9   95.81     6.9   94.51     8.9   94.51
     8.9   95.81    10.6   96.81      14   98.61      24   98.61
#Mann= 3 , 0 , 0
   -11.5    .035       0       0    .035       0      14    .035       0
#XS Ineff= 2 , 0
               0     110      14             110
Permanent Ineff=
       F       F
#Block Obstruct= 2 , 0
                              14
Bank Sta=0,14
XS Rating Curve= 0
Exp/Cntr=.3,.1

Type RM Length L Ch R = 1 ,1300.00 ,25,25,25
BEGIN DESCRIPTION:
26
END DESCRIPTION:
#Sta/Elev= 9
     -14  100.93      -4  100.93       0   95.93      .6   94.43     4.6   94.43
     5.1   95.83     7.1   95.83     8.2   95.03    18.2   95.03
#Mann= 3 , 0 , 0
     -14    .035       0       0    .035       0     5.1    .035       0
#XS Ineff= 2 , 0
               0     105     5.1             105
Permanent Ineff=
       F       F
#Block Obstruct= 2 , 0
                             5.1
Bank Sta=0,5.1
XS Rating Curve= 0
Exp/Cntr=.3,.1

Type RM Length L Ch R = 1 ,1275.00 ,25,25,25
BEGIN DESCRIPTION:
25.025
END DESCRIPTION:
#Sta/Elev= 10
    -8.1  107.71    -5.1  103.21    -2.1   98.71       0   95.51      .9   94.21
     4.4   94.21     4.9   95.51     5.9   95.51     6.8   94.71    16.8   94.71
#Mann= 3 , 0 , 0
    -8.1    .035       0       0    .035       0     4.9    .035       0
#XS Ineff= 2 , 0
               0     105     4.9             105
Permanent Ineff=
       F       F
#Block Obstruct= 2 , 0
                             4.9
Bank Sta=0,4.9
XS Rating Curve= 0
Exp/Cntr=.3,.1

Type RM Length L Ch R = 1 ,1250.00 ,50,50,50
BEGIN DESCRIPTION:
25
END DESCRIPTION:
#Sta/Elev= 11
      -8   97.61      -3   97.11       0   95.41       1   94.81     2.4   93.91
     2.9   93.91     4.1   94.11     6.3   95.41     6.7   95.41       7   95.11
      17   95.11
#Mann= 3 , 0 , 0
      -8    .035       0       0    .035       0     6.3    .035       0
#XS Ineff= 2 , 0
               0     100     6.3             100
Permanent Ineff=
       F       F
#Block Obstruct= 2 , 0
                             6.3
Bank Sta=0,6.3
XS Rating Curve= 0
Exp/Cntr=.3,.1

Type RM Length L Ch R = 1 ,1200.00 ,50,50,50
BEGIN DESCRIPTION:
24
END DESCRIPTION:
#Sta/Elev= 11
      -8   97.41       0   96.91       0   95.21       1   94.61     2.4   93.21
     2.9   93.21     4.1   93.91     6.3   95.21     6.7   95.21       7   94.91
      17   94.91
#Mann= 3 , 0 , 0
      -8    .035       0       0    .035       0     6.3    .035       0
#XS Ineff= 2 , 0
               0     100     6.3             100
Permanent Ineff=
       F       F
#Block Obstruct= 2 , 0
                             6.3
Bank Sta=0,6.3
XS Rating Curve= 0
Exp/Cntr=.3,.1

Type RM Length L Ch R = 1 ,1150.00 ,49,49,49
BEGIN DESCRIPTION:
23
END DESCRIPTION:
#Sta/Elev= 11
      -8   94.79      -2   94.79       0   92.79     2.2   91.99       4   91.49
     6.2   91.49     8.3   92.19     9.6   92.89    10.5   92.89    10.8   92.59
    20.8   92.59
#Mann= 3 , 0 , 0
      -8    .035       0       0    .035       0     9.6    .035       0
#XS Ineff= 2 , 0
               0     100     9.6             100
Permanent Ineff=
       F       F
#Block Obstruct= 2 , 0
                             9.6
Bank Sta=0,9.6
XS Rating Curve= 0
Exp/Cntr=.3,.1

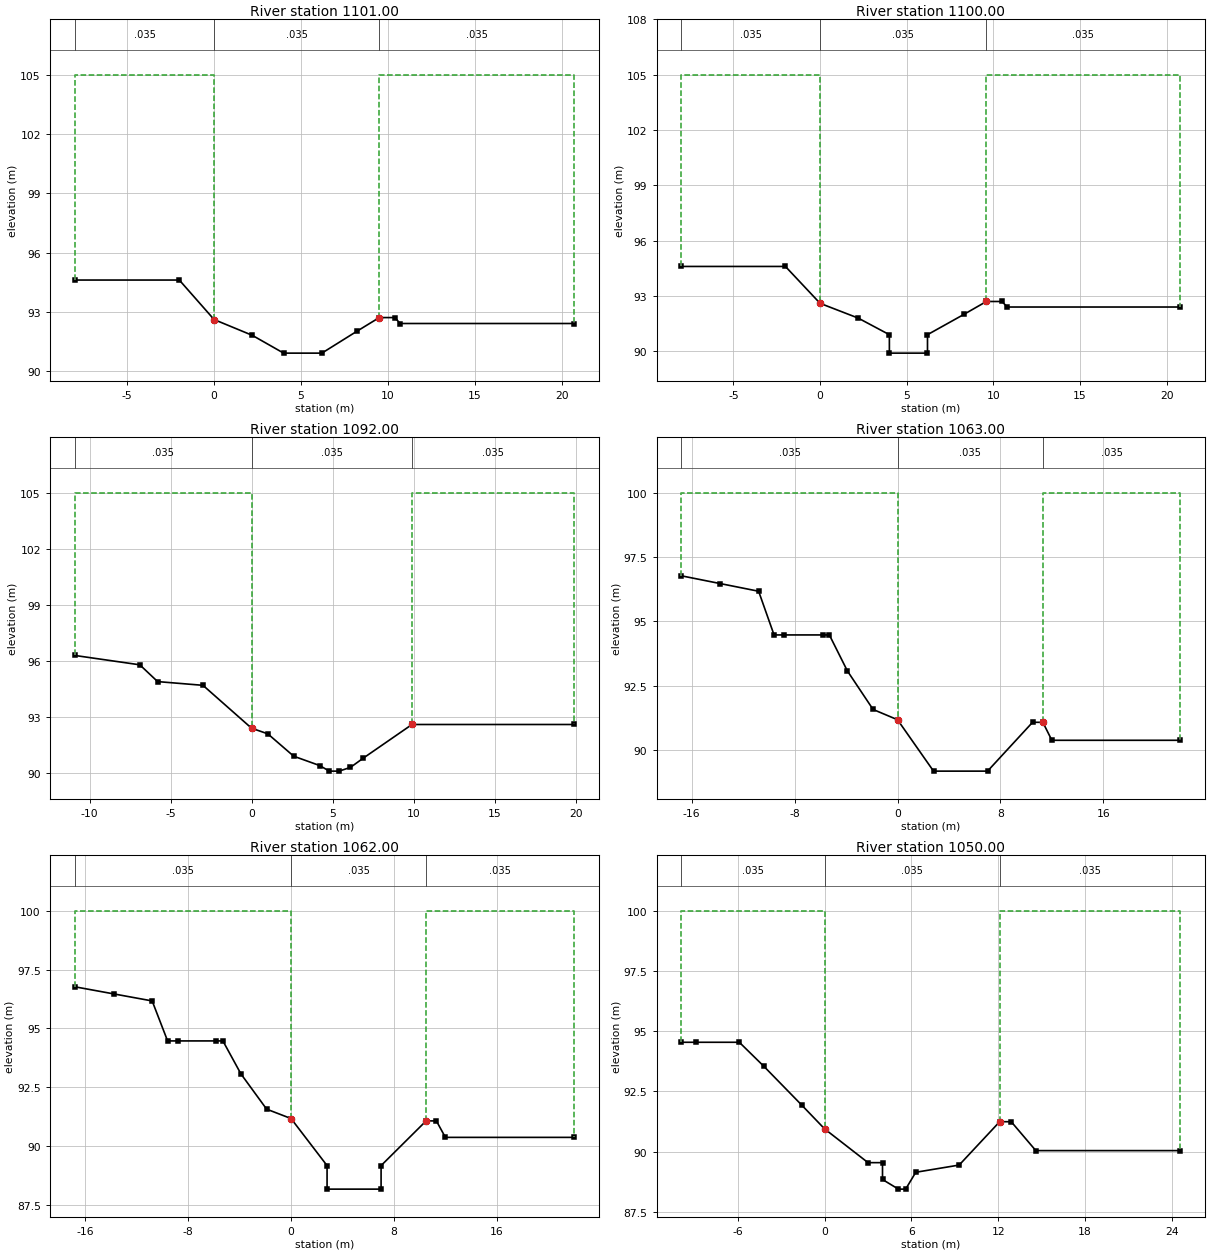
Type RM Length L Ch R = 1 ,1101.00 ,1,1,1
BEGIN DESCRIPTION:
22.001
END DESCRIPTION:
#Sta/Elev= 11
      -8   94.61      -2   94.61       0   92.61     2.2   91.81       4   90.91
     6.2   90.91     8.2   92.01     9.5   92.71    10.4   92.71    10.7   92.41
    20.7   92.41
#Mann= 3 , 0 , 0
      -8    .035       0       0    .035       0     9.5    .035       0
#XS Ineff= 2 , 0
               0     105     9.5             105
Permanent Ineff=
       F       F
#Block Obstruct= 2 , 0
                             9.5
Bank Sta=0,9.5
XS Rating Curve= 0
Exp/Cntr=.3,.1

Type RM Length L Ch R = 1 ,1100.00 ,8,8,8
BEGIN DESCRIPTION:
22
END DESCRIPTION:
#Sta/Elev= 13
      -8   94.61      -2   94.61       0   92.61     2.2   91.81       4   90.91
       4   89.91     6.2   89.91     6.2   90.91     8.3   92.01     9.6   92.71
    10.5   92.71    10.8   92.41    20.8   92.41
#Mann= 3 , 0 , 0
      -8    .035       0       0    .035       0     9.6    .035       0
#XS Ineff= 2 , 0
               0     105     9.6             105
Permanent Ineff=
       F       F
#Block Obstruct= 2 , 0
                             9.6
Bank Sta=0,9.6
XS Rating Curve= 0
Exp/Cntr=.3,.1

Type RM Length L Ch R = 1 ,1092.00 ,29,29,29
BEGIN DESCRIPTION:
21.042
END DESCRIPTION:
#Sta/Elev= 14
   -10.9   96.28    -6.9   95.78    -5.8   94.88      -3   94.68       0   92.38
       1   92.08     2.6   90.88     4.2   90.38     4.8   90.08     5.4   90.08
     6.1   90.28     6.9   90.78     9.9   92.58    19.9   92.58
#Mann= 3 , 0 , 0
   -10.9    .035       0       0    .035       0     9.9    .035       0
#XS Ineff= 2 , 0
               0     105     9.9             105
Permanent Ineff=
       F       F
#Block Obstruct= 2 , 0
                             9.9
Bank Sta=0,9.9
XS Rating Curve= 0
Exp/Cntr=.3,.1

Type RM Length L Ch R = 1 ,1063.00 ,1,1,1
BEGIN DESCRIPTION:
21.013
END DESCRIPTION:
#Sta/Elev= 16
   -16.8   96.77   -13.8   96.47   -10.8   96.17    -9.6   94.47    -8.8   94.47
    -5.8   94.47    -5.3   94.47    -3.9   93.07    -1.9   91.57       0   91.17
     2.8   89.17       7   89.17    10.5   91.07    11.3   91.07      12   90.37
      22   90.37
#Mann= 3 , 0 , 0
   -16.8    .035       0       0    .035       0    11.3    .035       0
#XS Ineff= 2 , 0
               0     100    11.3             100
Permanent Ineff=
       F       F
#Block Obstruct= 2 , 0
                            11.3
Bank Sta=0,11.3
XS Rating Curve= 0
Exp/Cntr=.3,.1

Type RM Length L Ch R = 1 ,1062.00 ,12,12,12
BEGIN DESCRIPTION:
21.012
END DESCRIPTION:
#Sta/Elev= 18
   -16.8   96.77   -13.8   96.47   -10.8   96.17    -9.6   94.47    -8.8   94.47
    -5.8   94.47    -5.3   94.47    -3.9   93.07    -1.9   91.57       0   91.17
     2.8   89.17     2.8   88.17       7   88.17       7   89.17    10.5   91.07
    11.3   91.07      12   90.37      22   90.37
#Mann= 3 , 0 , 0
   -16.8    .035       0       0    .035       0    10.5    .035       0
#XS Ineff= 2 , 0
               0     100    10.5             100
Permanent Ineff=
       F       F
#Block Obstruct= 2 , 0
                            10.5
Bank Sta=0,10.5
XS Rating Curve= 0
Exp/Cntr=.3,.1

Type RM Length L Ch R = 1 ,1050.00 ,50,50,50
BEGIN DESCRIPTION:
21
END DESCRIPTION:
#Sta/Elev= 17
    -9.9   94.54    -8.9   94.54    -5.9   94.54    -4.2   93.54    -1.6   91.94
       0   90.94       3   89.54       4   89.54       4   88.84     5.1   88.44
     5.6   88.44     6.3   89.14     9.3   89.44    12.1   91.24    12.9   91.24
    14.6   90.04    24.6   90.04
#Mann= 3 , 0 , 0
    -9.9    .035       0       0    .035       0    12.1    .035       0
#XS Ineff= 2 , 0
               0     100    12.1             100
Permanent Ineff=
       F       F
#Block Obstruct= 2 , 0
                            12.1
Bank Sta=0,12.1
XS Rating Curve= 0
Exp/Cntr=.3,.1

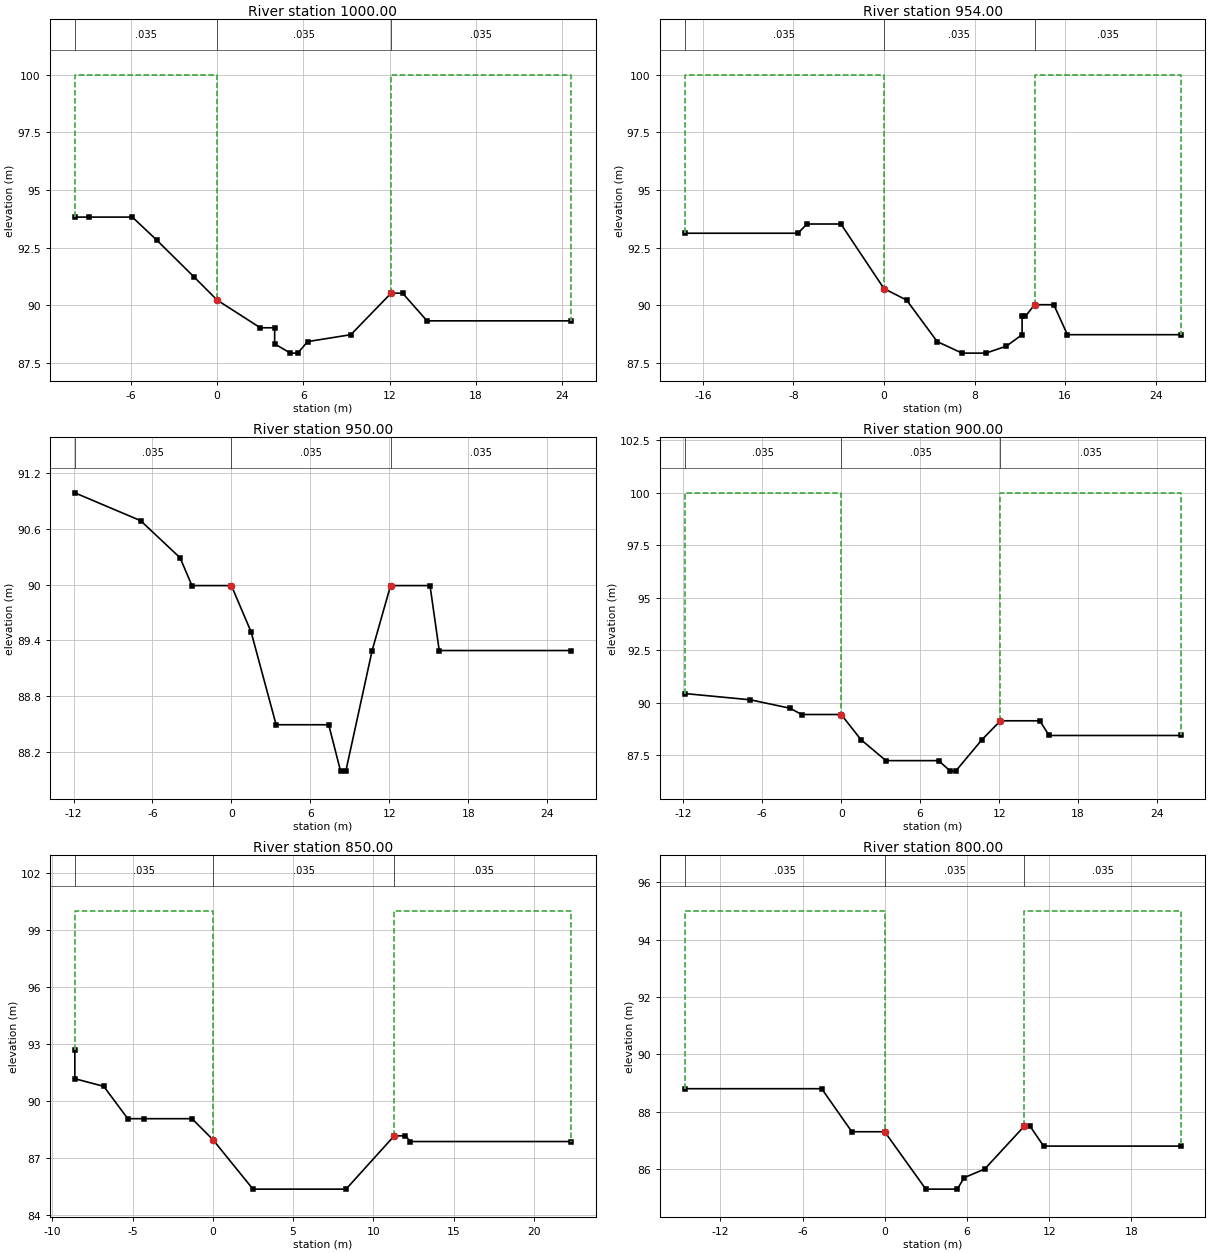
Type RM Length L Ch R = 1 ,1000.00 ,46,46,46
BEGIN DESCRIPTION:
20
END DESCRIPTION:
#Sta/Elev= 17
    -9.9   93.83    -8.9   93.83    -5.9   93.83    -4.2   92.83    -1.6   91.23
       0   90.23       3   89.03       4   89.03       4   88.33     5.1   87.93
     5.6   87.93     6.3   88.43     9.3   88.73    12.1   90.53    12.9   90.53
    14.6   89.33    24.6   89.33
#Mann= 3 , 0 , 0
    -9.9    .035       0       0    .035       0    12.1    .035       0
#XS Ineff= 2 , 0
               0     100    12.1             100
Permanent Ineff=
       F       F
#Block Obstruct= 2 , 0
                            12.1
Bank Sta=0,12.1
XS Rating Curve= 0
Exp/Cntr=.3,.1

Type RM Length L Ch R = 1 ,954.00  ,4,4,4
BEGIN DESCRIPTION:
19.004
END DESCRIPTION:
#Sta/Elev= 17
   -17.6   93.13    -7.6   93.13    -6.8   93.53    -3.8   93.53       0   90.73
       2   90.23     4.7   88.43     6.9   87.93       9   87.93    10.8   88.23
    12.2   88.73    12.2   89.53    12.5   89.53    13.3   90.03      15   90.03
    16.2   88.73    26.2   88.73
#Mann= 3 , 0 , 0
   -17.6    .035       0       0    .035       0    13.3    .035       0
#XS Ineff= 2 , 0
               0     100    13.3             100
Permanent Ineff=
       F       F
#Block Obstruct= 2 , 0
                            13.3
Bank Sta=0,13.3
XS Rating Curve= 0
Exp/Cntr=.3,.1

Type RM Length L Ch R = 1 ,950.00  ,50,50,50
BEGIN DESCRIPTION:
19
END DESCRIPTION:
#Sta/Elev= 15
   -11.9   90.99    -6.9   90.69    -3.9   90.29      -3   89.99       0   89.99
     1.5   89.49     3.4   88.49     7.4   88.49     8.3   87.99     8.7   87.99
    10.7   89.29    12.1   89.99    15.1   89.99    15.8   89.29    25.8   89.29
#Mann= 3 , 0 , 0
   -11.9    .035       0       0    .035       0    12.1    .035       0
#XS Ineff= 2 , 0
               0     100    12.1             100
Permanent Ineff=
       F       F
#Block Obstruct= 2 , 0
                            12.1
Bank Sta=0,12.1
XS Rating Curve= 0
Exp/Cntr=.3,.1

Type RM Length L Ch R = 1 ,900.00  ,50,50,50
BEGIN DESCRIPTION:
18
END DESCRIPTION:
#Sta/Elev= 15
   -11.9   90.43    -6.9   90.13    -3.9   89.73      -3   89.43       0   89.43
     1.5   88.23     3.4   87.23     7.4   87.23     8.3   86.73     8.7   86.73
    10.7   88.23    12.1   89.13    15.1   89.13    15.8   88.43    25.8   88.43
#Mann= 3 , 0 , 0
   -11.9    .035       0       0    .035       0    12.1    .035       0
#XS Ineff= 2 , 0
               0     100    12.1             100
Permanent Ineff=
       F       F
#Block Obstruct= 2 , 0
                            12.1
Bank Sta=0,12.1
XS Rating Curve= 0
Exp/Cntr=.3,.1

Type RM Length L Ch R = 1 ,850.00  ,50,50,50
BEGIN DESCRIPTION:
17
END DESCRIPTION:
#Sta/Elev= 13
    -8.6   92.68    -8.6   91.18    -6.8   90.78    -5.3   89.08    -4.3   89.08
    -1.3   89.08       0   87.98     2.5   85.38     8.3   85.38    11.3   88.18
      12   88.18    12.3   87.88    22.3   87.88
#Mann= 3 , 0 , 0
    -8.6    .035       0       0    .035       0    11.3    .035       0
#XS Ineff= 2 , 0
               0     100    11.3             100
Permanent Ineff=
       F       F
#Block Obstruct= 2 , 0
                            11.3
Bank Sta=0,11.3
XS Rating Curve= 0
Exp/Cntr=.3,.1

Type RM Length L Ch R = 1 ,800.00  ,26,26,26
BEGIN DESCRIPTION:
16
END DESCRIPTION:
#Sta/Elev= 12
   -14.6    88.8    -4.6    88.8    -2.4    87.3       0    87.3       3    85.3
     5.3    85.3     5.8    85.7     7.3      86    10.2    87.5    10.6    87.5
    11.6    86.8    21.6    86.8
#Mann= 3 , 0 , 0
   -14.6    .035       0       0    .035       0    10.2    .035       0
#XS Ineff= 2 , 0
               0      95    10.2              95
Permanent Ineff=
       F       F
#Block Obstruct= 2 , 0
                            10.2
Bank Sta=0,10.2
XS Rating Curve= 0
Exp/Cntr=.3,.1

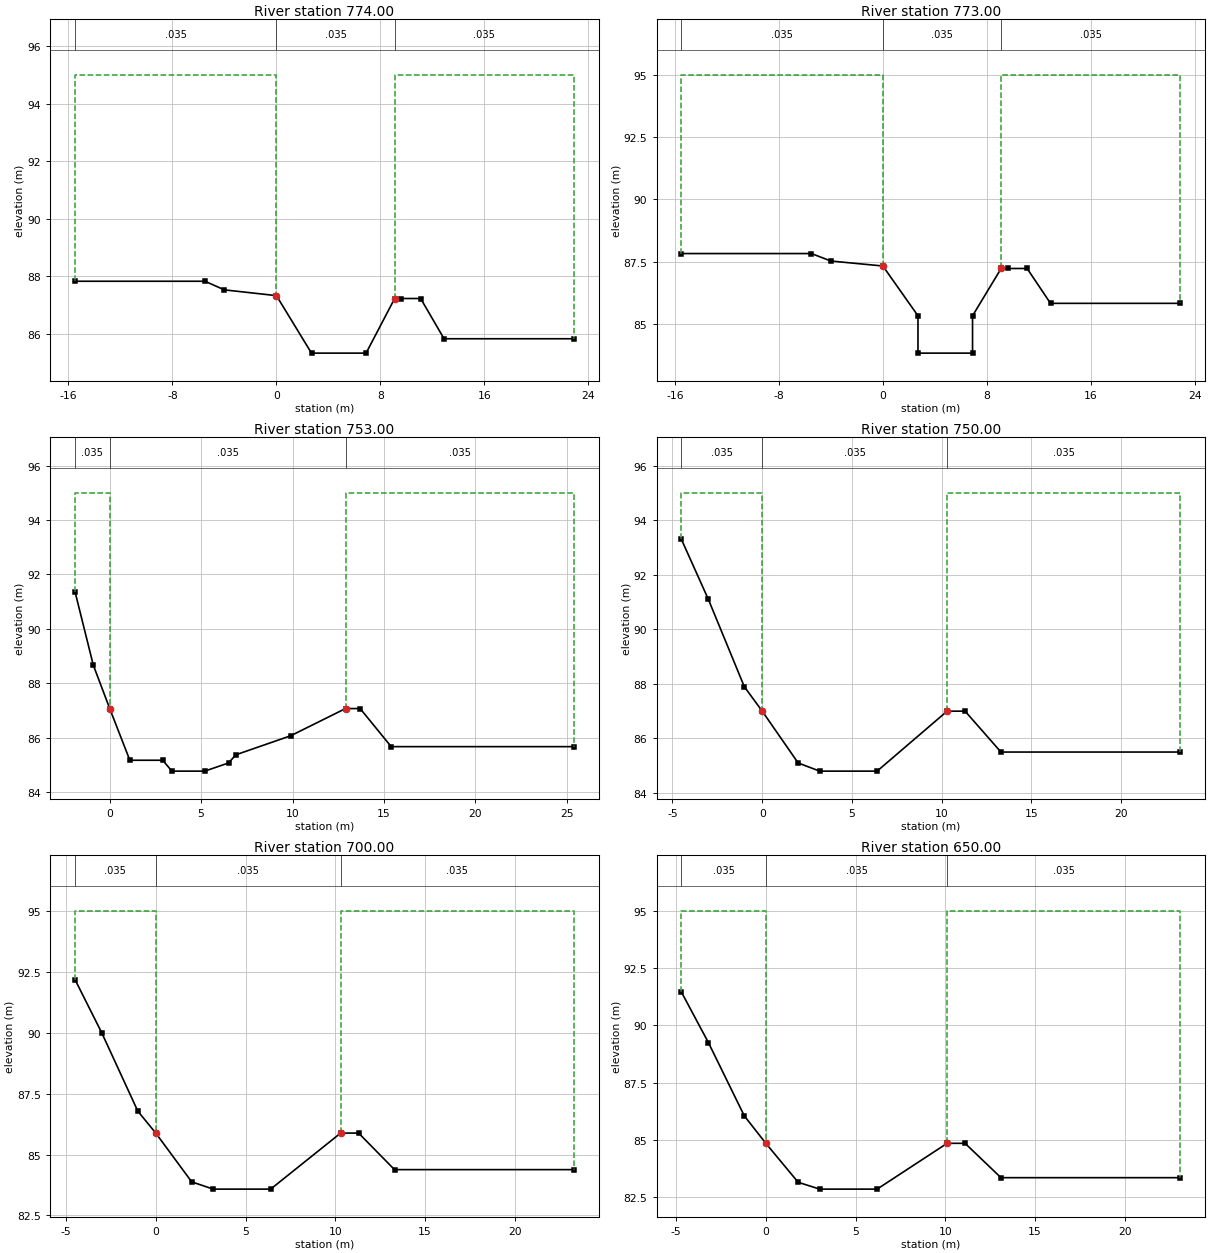
Type RM Length L Ch R = 1 ,774.00  ,1,1,1
BEGIN DESCRIPTION:
15.024
END DESCRIPTION:
#Sta/Elev= 11
   -15.5   87.82    -5.5   87.82      -4   87.52       0   87.32     2.7   85.32
     6.9   85.32     9.1   87.22     9.6   87.22    11.1   87.22    12.9   85.82
    22.9   85.82
#Mann= 3 , 0 , 0
   -15.5    .035       0       0    .035       0     9.1    .035       0
#XS Ineff= 2 , 0
               0      95     9.1              95
Permanent Ineff=
       F       F
#Block Obstruct= 2 , 0
                             9.1
Bank Sta=0,9.1
XS Rating Curve= 0
Exp/Cntr=.3,.1

Type RM Length L Ch R = 1 ,773.00  ,20,20,20
BEGIN DESCRIPTION:
15.023
END DESCRIPTION:
#Sta/Elev= 13
   -15.5   87.82    -5.5   87.82      -4   87.52       0   87.32     2.7   85.32
     2.7   83.82     6.9   83.82     6.9   85.32     9.1   87.22     9.6   87.22
    11.1   87.22    12.9   85.82    22.9   85.82
#Mann= 3 , 0 , 0
   -15.5    .035       0       0    .035       0     9.1    .035       0
#XS Ineff= 2 , 0
               0      95     9.1              95
Permanent Ineff=
       F       F
#Block Obstruct= 2 , 0
                             9.1
Bank Sta=0,9.1
XS Rating Curve= 0
Exp/Cntr=.3,.1

Type RM Length L Ch R = 1 ,753.00  ,3,3,3
BEGIN DESCRIPTION:
15.003
END DESCRIPTION:
#Sta/Elev= 14
    -1.9   91.37     -.9   88.67       0   87.07     1.1   85.17     2.9   85.17
     3.4   84.77     5.2   84.77     6.5   85.07     6.9   85.37     9.9   86.07
    12.9   87.07    13.7   87.07    15.4   85.67    25.4   85.67
#Mann= 3 , 0 , 0
    -1.9    .035       0       0    .035       0    12.9    .035       0
#XS Ineff= 2 , 0
               0      95    12.9              95
Permanent Ineff=
       F       F
#Block Obstruct= 2 , 0
                            12.9
Bank Sta=0,12.9
XS Rating Curve= 0
Exp/Cntr=.3,.1

Type RM Length L Ch R = 1 ,750.00  ,50,50,50
BEGIN DESCRIPTION:
15
END DESCRIPTION:
#Sta/Elev= 11
    -4.5   93.29      -3   91.09      -1   87.89       0   86.99       2   85.09
     3.2   84.79     6.4   84.79    10.3   86.99    11.3   86.99    13.3   85.49
    23.3   85.49
#Mann= 3 , 0 , 0
    -4.5    .035       0       0    .035       0    10.3    .035       0
#XS Ineff= 2 , 0
               0      95    10.3              95
Permanent Ineff=
       F       F
#Block Obstruct= 2 , 0
                            10.3
Bank Sta=0,10.3
XS Rating Curve= 0
Exp/Cntr=.3,.1

Type RM Length L Ch R = 1 ,700.00  ,50,50,50
BEGIN DESCRIPTION:
14
END DESCRIPTION:
#Sta/Elev= 11
    -4.5   92.18      -3   89.98      -1   86.78       0   85.88       2   83.88
     3.2   83.58     6.4   83.58    10.3   85.88    11.3   85.88    13.3   84.38
    23.3   84.38
#Mann= 3 , 0 , 0
    -4.5    .035       0       0    .035       0    10.3    .035       0
#XS Ineff= 2 , 0
               0      95    10.3              95
Permanent Ineff=
       F       F
#Block Obstruct= 2 , 0
                            10.3
Bank Sta=0,10.3
XS Rating Curve= 0
Exp/Cntr=.3,.1

Type RM Length L Ch R = 1 ,650.00  ,50,50,50
BEGIN DESCRIPTION:
13
END DESCRIPTION:
#Sta/Elev= 11
    -4.7   91.45    -3.2   89.25    -1.2   86.05       0   84.85     1.8   83.15
       3   82.85     6.2   82.85    10.1   84.85    11.1   84.85    13.1   83.35
    23.1   83.35
#Mann= 3 , 0 , 0
    -4.7    .035       0       0    .035       0    10.1    .035       0
#XS Ineff= 2 , 0
               0      95    10.1              95
Permanent Ineff=
       F       F
#Block Obstruct= 2 , 0
                            10.1
Bank Sta=0,10.1
XS Rating Curve= 0
Exp/Cntr=.3,.1

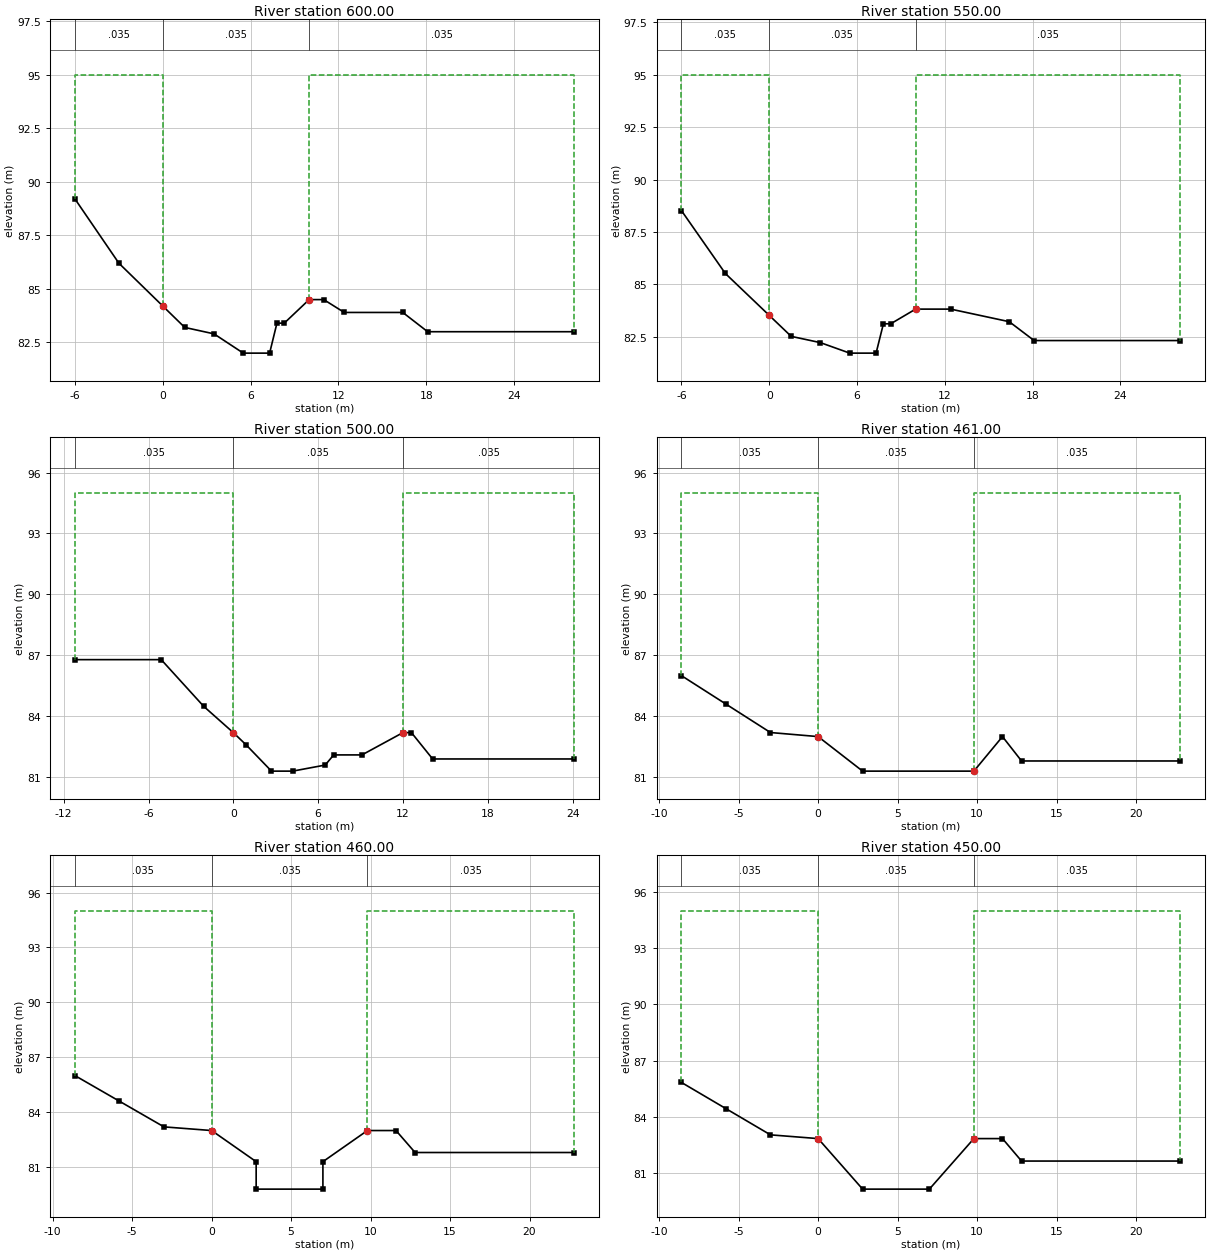
Type RM Length L Ch R = 1 ,600.00  ,50,50,50
BEGIN DESCRIPTION:
12
END DESCRIPTION:
#Sta/Elev= 15
      -6    89.2      -3    86.2       0    84.2     1.5    83.2     3.5    82.9
     5.5      82     7.3      82     7.8    83.4     8.3    83.4      10    84.5
      11    84.5    12.4    83.9    16.4    83.9    18.1      83    28.1      83
#Mann= 3 , 0 , 0
      -6    .035       0       0    .035       0      10    .035       0
#XS Ineff= 2 , 0
               0      95      10              95
Permanent Ineff=
       F       F
#Block Obstruct= 2 , 0
                              10
Bank Sta=0,10
XS Rating Curve= 0
Exp/Cntr=.3,.1

Type RM Length L Ch R = 1 ,550.00  ,50,50,50
BEGIN DESCRIPTION:
11
END DESCRIPTION:
#Sta/Elev= 14
      -6   88.52      -3   85.52       0   83.52     1.5   82.52     3.5   82.22
     5.5   81.72     7.3   81.72     7.8   83.12     8.3   83.12      10   83.82
    12.4   83.82    16.4   83.22    18.1   82.32    28.1   82.32
#Mann= 3 , 0 , 0
      -6    .035       0       0    .035       0      10    .035       0
#XS Ineff= 2 , 0
               0      95      10              95
Permanent Ineff=
       F       F
#Block Obstruct= 2 , 0
                              10
Bank Sta=0,10
XS Rating Curve= 0
Exp/Cntr=.3,.1

Type RM Length L Ch R = 1 ,500.00  ,39,39,39
BEGIN DESCRIPTION:
10
END DESCRIPTION:
#Sta/Elev= 14
   -11.2   86.77    -5.1   86.77    -2.1   84.47       0   83.17      .9   82.57
     2.7   81.27     4.2   81.27     6.5   81.57     7.1   82.07     9.1   82.07
      12   83.17    12.6   83.17    14.1   81.87    24.1   81.87
#Mann= 3 , 0 , 0
   -11.2    .035       0       0    .035       0      12    .035       0
#XS Ineff= 2 , 0
               0      95      12              95
Permanent Ineff=
       F       F
#Block Obstruct= 2 , 0
                              12
Bank Sta=0,12
XS Rating Curve= 0
Exp/Cntr=.3,.1

Type RM Length L Ch R = 1 ,461.00  ,1,1,1
BEGIN DESCRIPTION:
9.011
END DESCRIPTION:
#Sta/Elev= 9
    -8.6      86    -5.8    84.6      -3    83.2       0      83     2.8    81.3
     9.8    81.3    11.6      83    12.8    81.8    22.8    81.8
#Mann= 3 , 0 , 0
    -8.6    .035       0       0    .035       0     9.8    .035       0
#XS Ineff= 2 , 0
               0      95     9.8              95
Permanent Ineff=
       F       F
#Block Obstruct= 2 , 0
                             9.8
Bank Sta=0,9.8
XS Rating Curve= 0
Exp/Cntr=.3,.1

Type RM Length L Ch R = 1 ,460.00  ,10,10,10
BEGIN DESCRIPTION:
9.01
END DESCRIPTION:
#Sta/Elev= 12
    -8.6      86    -5.8    84.6      -3    83.2       0      83     2.8    81.3
     2.8    79.8       7    79.8       7    81.3     9.8      83    11.6      83
    12.8    81.8    22.8    81.8
#Mann= 3 , 0 , 0
    -8.6    .035       0       0    .035       0     9.8    .035       0
#XS Ineff= 2 , 0
               0      95     9.8              95
Permanent Ineff=
       F       F
#Block Obstruct= 2 , 0
                             9.8
Bank Sta=0,9.8
XS Rating Curve= 0
Exp/Cntr=.3,.1

Type RM Length L Ch R = 1 ,450.00  ,50,50,50
BEGIN DESCRIPTION:
9
END DESCRIPTION:
#Sta/Elev= 10
    -8.6   85.83    -5.8   84.43      -3   83.03       0   82.83     2.8   80.13
       7   80.13     9.8   82.83    11.6   82.83    12.8   81.63    22.8   81.63
#Mann= 3 , 0 , 0
    -8.6    .035       0       0    .035       0     9.8    .035       0
#XS Ineff= 2 , 0
               0      95     9.8              95
Permanent Ineff=
       F       F
#Block Obstruct= 2 , 0
                             9.8
Bank Sta=0,9.8
XS Rating Curve= 0
Exp/Cntr=.3,.1