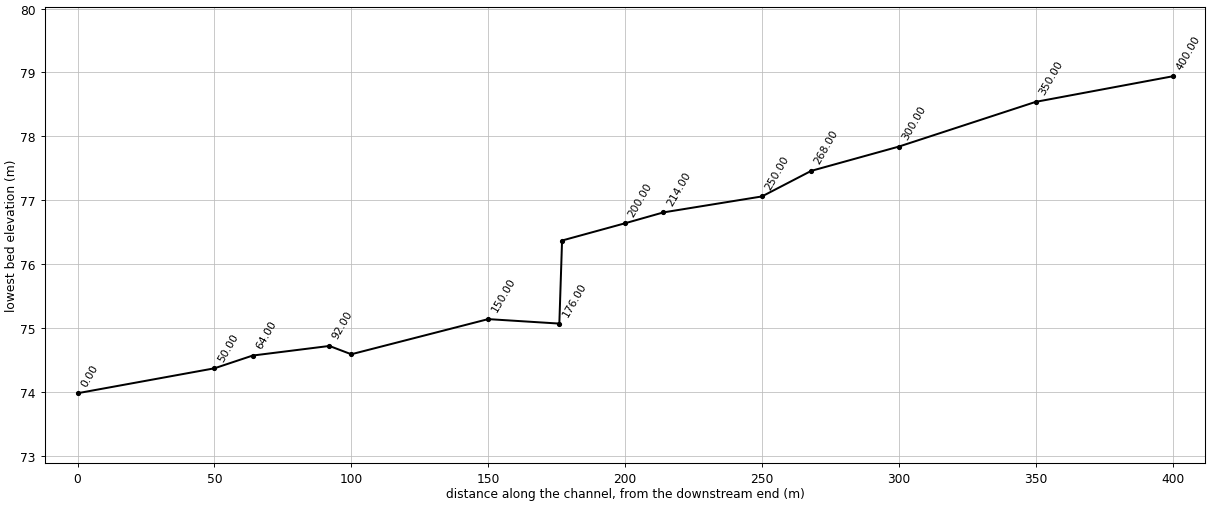
HEC-RAS study EUM.prj: EUM

--- EUM.g01 (geometry) --- (continued)

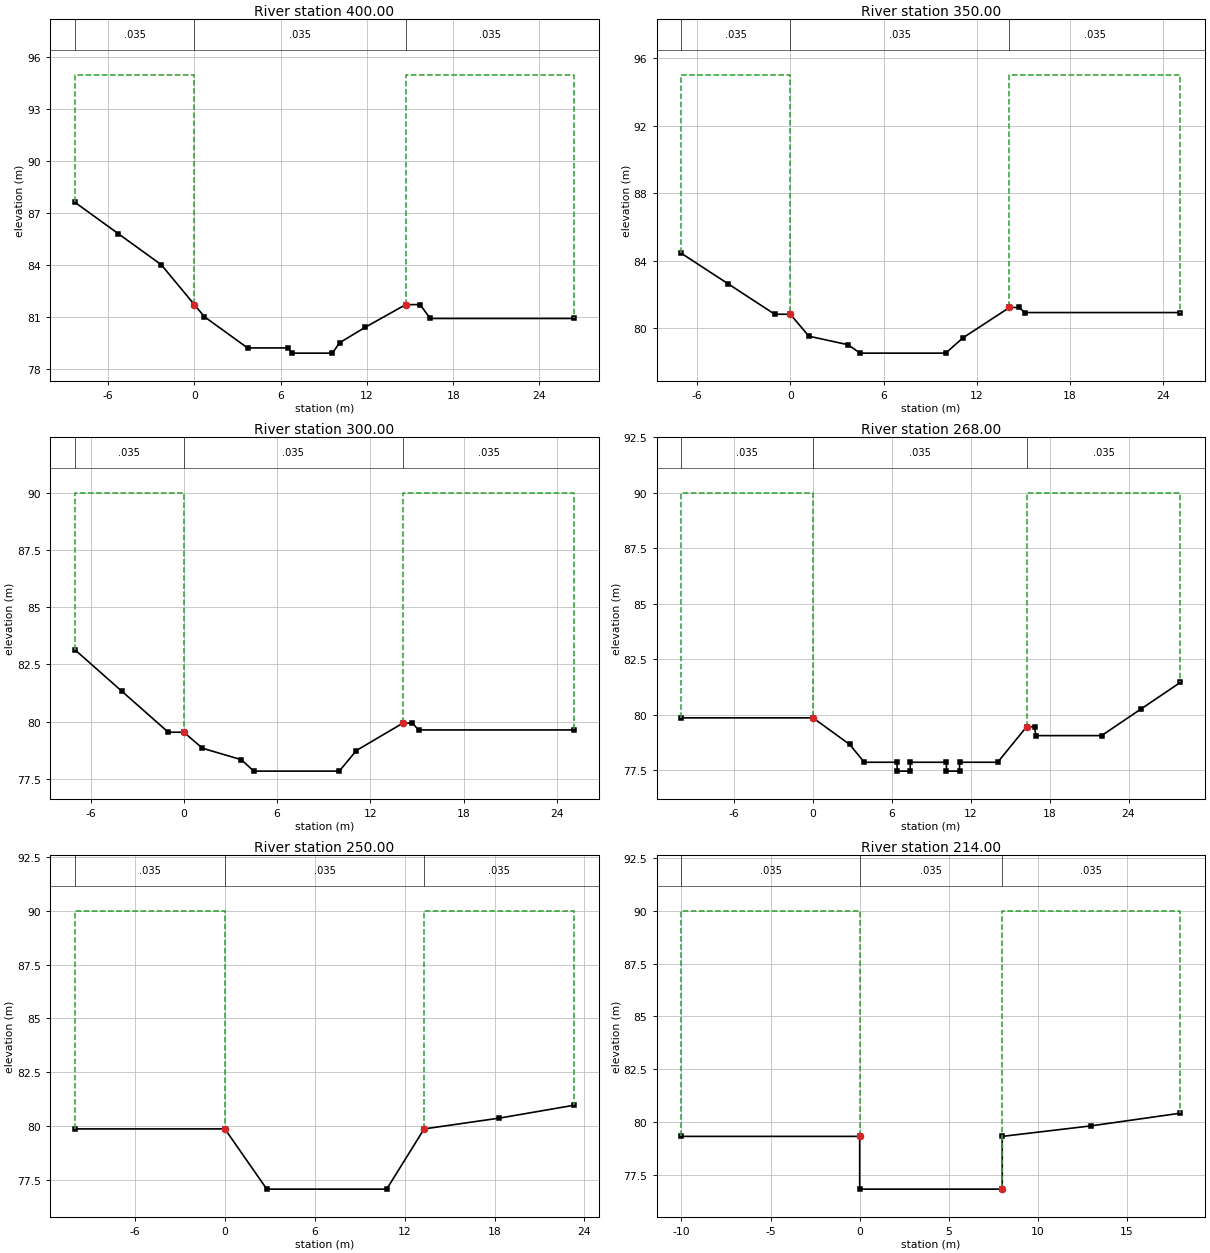
Type RM Length L Ch R = 1 ,400.00  ,50,50,50
BEGIN DESCRIPTION:
8
END DESCRIPTION:
#Sta/Elev= 15
    -8.3   87.64    -5.3   85.84    -2.3   84.04       0   81.74      .7   81.04
     3.7   79.24     6.5   79.24     6.8   78.94     9.6   78.94    10.1   79.54
    11.9   80.44    14.7   81.74    15.7   81.74    16.4   80.94    26.4   80.94
#Mann= 3 , 0 , 0
    -8.3    .035       0       0    .035       0    14.7    .035       0
#XS Ineff= 2 , 0
               0      95    14.7              95
Permanent Ineff=
       F       F
#Block Obstruct= 2 , 0
                            14.7
Bank Sta=0,14.7
XS Rating Curve= 0
Exp/Cntr=.3,.1

Type RM Length L Ch R = 1 ,350.00  ,50,50,50
BEGIN DESCRIPTION:
7
END DESCRIPTION:
#Sta/Elev= 13
      -7   84.44      -4   82.64      -1   80.84       0   80.84     1.2   79.54
     3.7   79.04     4.5   78.54      10   78.54    11.1   79.44    14.1   81.24
    14.7   81.24    15.1   80.94    25.1   80.94
#Mann= 3 , 0 , 0
      -7    .035       0       0    .035       0    14.1    .035       0
#XS Ineff= 2 , 0
               0      95    14.1              95
Permanent Ineff=
       F       F
#Block Obstruct= 2 , 0
                            14.1
Bank Sta=0,14.1
XS Rating Curve= 0
Exp/Cntr=.3,.1

Type RM Length L Ch R = 1 ,300.00  ,32,32,32
BEGIN DESCRIPTION:
6
END DESCRIPTION:
#Sta/Elev= 13
      -7   83.14      -4   81.34      -1   79.54       0   79.54     1.2   78.84
     3.7   78.34     4.5   77.84      10   77.84    11.1   78.74    14.1   79.94
    14.7   79.94    15.1   79.64    25.1   79.64
#Mann= 3 , 0 , 0
      -7    .035       0       0    .035       0    14.1    .035       0
#XS Ineff= 2 , 0
               0      90    14.1              90
Permanent Ineff=
       F       F
#Block Obstruct= 2 , 0
                            14.1
Bank Sta=0,14.1
XS Rating Curve= 0
Exp/Cntr=.3,.1

Type RM Length L Ch R = 1 ,268.00  ,18,18,18
BEGIN DESCRIPTION:
5.018
END DESCRIPTION:
#Sta/Elev= 19
     -10   79.86       0   79.86     2.8   78.66     3.9   77.86     6.4   77.86
     6.4   77.46     7.4   77.46     7.4   77.86   10.15   77.86   10.15   77.46
   11.15   77.46   11.15   77.86   14.05   77.86   16.25   79.46   16.85   79.46
   16.95   79.06   21.95   79.06   24.95   80.26   27.95   81.46
#Mann= 3 , 0 , 0
     -10    .035       0       0    .035       0   16.25    .035       0
#XS Ineff= 2 , 0
               0      90   16.25              90
Permanent Ineff=
       F       F
#Block Obstruct= 2 , 0
                           16.25
Bank Sta=0,16.25
XS Rating Curve= 0
Exp/Cntr=.3,.1

Type RM Length L Ch R = 1 ,250.00  ,36,36,36
BEGIN DESCRIPTION:
5
END DESCRIPTION:
#Sta/Elev= 7
     -10   79.86       0   79.86     2.8   77.06    10.8   77.06    13.3   79.86
    18.3   80.36    23.3   80.96
#Mann= 3 , 0 , 0
     -10    .035       0       0    .035       0    13.3    .035       0
#XS Ineff= 2 , 0
               0      90    13.3              90
Permanent Ineff=
       F       F
#Block Obstruct= 2 , 0
                            13.3
Bank Sta=0,13.3
XS Rating Curve= 0
Exp/Cntr=.3,.1

Type RM Length L Ch R = 1 ,214.00  ,14,14,14
BEGIN DESCRIPTION:
4.014
END DESCRIPTION:
#Sta/Elev= 7
     -10   79.31       0   79.31       0   76.81       8   76.81       8   79.31
      13   79.81      18   80.41
#Mann= 3 , 0 , 0
     -10    .035       0       0    .035       0       8    .035       0
#XS Ineff= 2 , 0
               0      90       8              90
Permanent Ineff=
       F       F
#Block Obstruct= 2 , 0
                               8
Bank Sta=0,8
XS Rating Curve= 0
Exp/Cntr=.3,.1

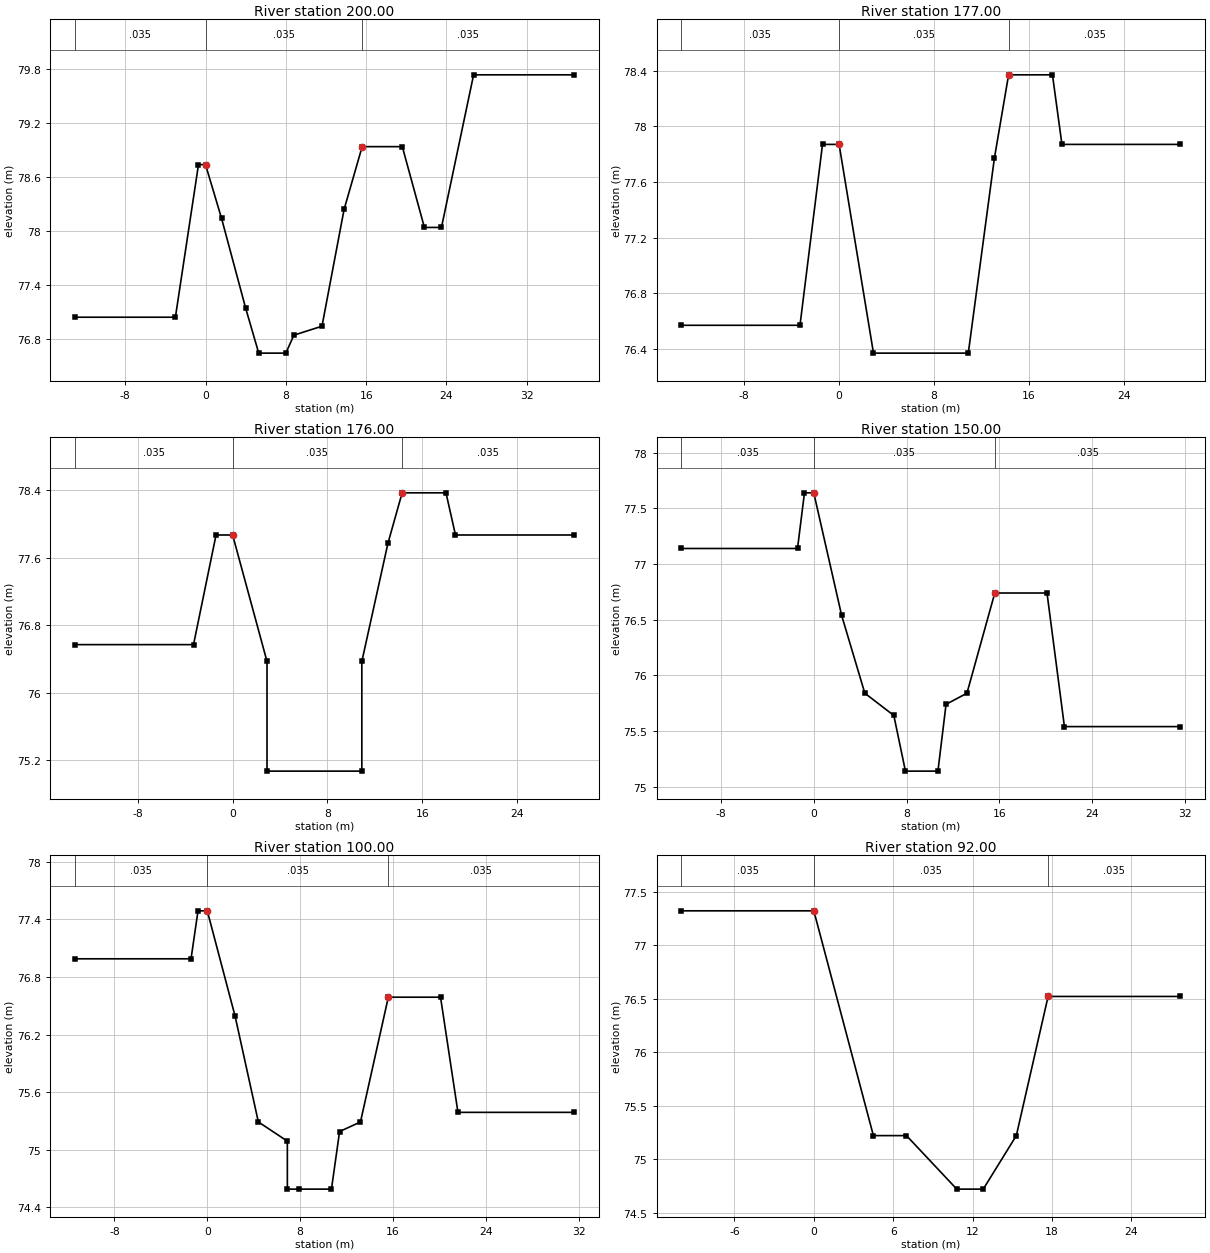
Type RM Length L Ch R = 1 ,200.00  ,23,23,23
BEGIN DESCRIPTION:
4
END DESCRIPTION:
#Sta/Elev= 17
     -13   77.04      -3   77.04     -.7   78.74       0   78.74     1.6   78.14
       4   77.14     5.3   76.64       8   76.64     8.8   76.84    11.6   76.94
    13.8   78.24    15.6   78.94    19.6   78.94    21.8   78.04    23.5   78.04
    26.7   79.74    36.7   79.74
#Mann= 3 , 0 , 0
     -13    .035       0       0    .035       0    15.6    .035       0
#XS Ineff= 2 , 0
               0      90    15.6              90
Permanent Ineff=
       F       F
#Block Obstruct= 2 , 0
                            15.6
Bank Sta=0,15.6
XS Rating Curve= 0
Exp/Cntr=.3,.1

Type RM Length L Ch R = 1 ,177.00  ,1,1,1
BEGIN DESCRIPTION:
3.027
END DESCRIPTION:
#Sta/Elev= 11
   -13.3   76.57    -3.3   76.57    -1.4   77.87       0   77.87     2.9   76.37
    10.9   76.37    13.1   77.77    14.3   78.37      18   78.37    18.8   77.87
    28.8   77.87
#Mann= 3 , 0 , 0
   -13.3    .035       0       0    .035       0    14.3    .035       0
#XS Ineff= 2 , 0
               0      90    14.3              90
Permanent Ineff=
       F       F
#Block Obstruct= 2 , 0
                            14.3
Bank Sta=0,14.3
XS Rating Curve= 0
Exp/Cntr=.3,.1

Type RM Length L Ch R = 1 ,176.00  ,26,26,26
BEGIN DESCRIPTION:
3.026
END DESCRIPTION:
#Sta/Elev= 13
   -13.3   76.57    -3.3   76.57    -1.4   77.87       0   77.87     2.9   76.37
     2.9   75.07    10.9   75.07    10.9   76.37    13.1   77.77    14.3   78.37
      18   78.37    18.8   77.87    28.8   77.87
#Mann= 3 , 0 , 0
   -13.3    .035       0       0    .035       0    14.3    .035       0
#XS Ineff= 2 , 0
               0      90    14.3              90
Permanent Ineff=
       F       F
#Block Obstruct= 2 , 0
                            14.3
Bank Sta=0,14.3
XS Rating Curve= 0
Exp/Cntr=.3,.1

Type RM Length L Ch R = 1 ,150.00  ,50,50,50
BEGIN DESCRIPTION:
3
END DESCRIPTION:
#Sta/Elev= 15
   -11.4   77.14    -1.4   77.14     -.8   77.64       0   77.64     2.4   76.54
     4.4   75.84     6.9   75.64     7.9   75.14    10.7   75.14    11.4   75.74
    13.2   75.84    15.6   76.74    20.1   76.74    21.6   75.54    31.6   75.54
#Mann= 3 , 0 , 0
   -11.4    .035       0       0    .035       0    15.6    .035       0
#XS Ineff= 2 , 0
               0      90    15.6              90
Permanent Ineff=
       F       F
#Block Obstruct= 2 , 0
                            15.6
Bank Sta=0,15.6
XS Rating Curve= 0
Exp/Cntr=.3,.1

Type RM Length L Ch R = 1 ,100.00  ,8,8,8
BEGIN DESCRIPTION:
2
END DESCRIPTION:
#Sta/Elev= 16
   -11.4   76.99    -1.4   76.99     -.8   77.49       0   77.49     2.4   76.39
     4.4   75.29     6.9   75.09     6.9   74.59     7.9   74.59    10.7   74.59
    11.4   75.19    13.2   75.29    15.6   76.59    20.1   76.59    21.6   75.39
    31.6   75.39
#Mann= 3 , 0 , 0
   -11.4    .035       0       0    .035       0    15.6    .035       0
#XS Ineff= 2 , 0
               0      90    15.6              90
Permanent Ineff=
       F       F
#Block Obstruct= 2 , 0
                            15.6
Bank Sta=0,15.6
XS Rating Curve= 0
Exp/Cntr=.3,.1

Type RM Length L Ch R = 1 ,92.00   ,28,28,28
BEGIN DESCRIPTION:
1.042
END DESCRIPTION:
#Sta/Elev= 9
     -10   77.32       0   77.32     4.5   75.22       7   75.22    10.8   74.72
    12.8   74.72    15.3   75.22    17.7   76.52    27.7   76.52
#Mann= 3 , 0 , 0
     -10    .035       0       0    .035       0    17.7    .035       0
#XS Ineff= 2 , 0
               0      90    17.7              90
Permanent Ineff=
       F       F
#Block Obstruct= 2 , 0
                            17.7
Bank Sta=0,17.7
XS Rating Curve= 0
Exp/Cntr=.3,.1

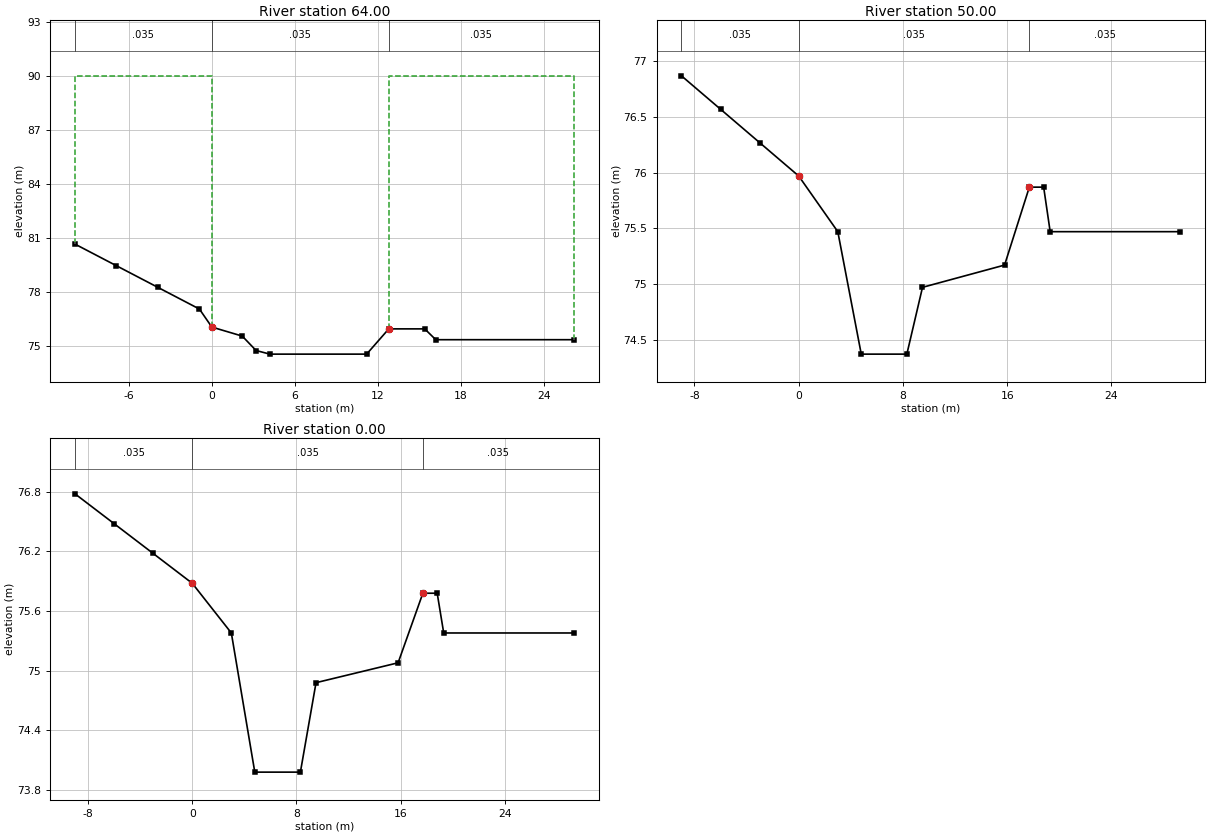
Type RM Length L Ch R = 1 ,64.00   ,14,14,14
BEGIN DESCRIPTION:
1.014
END DESCRIPTION:
#Sta/Elev= 13
    -9.9   80.67    -6.9   79.47    -3.9   78.27     -.9   77.07       0   76.07
     2.2   75.57     3.2   74.77     4.2   74.57    11.2   74.57    12.8   75.97
    15.4   75.97    16.2   75.37    26.2   75.37
#Mann= 3 , 0 , 0
    -9.9    .035       0       0    .035       0    12.8    .035       0
#XS Ineff= 2 , 0
               0      90    12.8              90
Permanent Ineff=
       F       F
#Block Obstruct= 2 , 0
                            12.8
Bank Sta=0,12.8
XS Rating Curve= 0
Exp/Cntr=.3,.1

Type RM Length L Ch R = 1 ,50.00   ,50,50,50
BEGIN DESCRIPTION:
1
END DESCRIPTION:
#Sta/Elev= 13
      -9   76.87      -6   76.57      -3   76.27       0   75.97       3   75.47
     4.8   74.37     8.3   74.37     9.5   74.97    15.8   75.17    17.7   75.87
    18.8   75.87    19.3   75.47    29.3   75.47
#Mann= 3 , 0 , 0
      -9    .035       0       0    .035       0    17.7    .035       0
#XS Ineff= 2 , 0
               0      90    17.7              90
Permanent Ineff=
       F       F
#Block Obstruct= 2 , 0
                            17.7
Bank Sta=0,17.7
XS Rating Curve= 0
Exp/Cntr=.3,.1

Type RM Length L Ch R = 1 ,0.00    ,0,0,0
BEGIN DESCRIPTION:
0
END DESCRIPTION:
#Sta/Elev= 13
      -9   76.78      -6   76.48      -3   76.18       0   75.88       3   75.38
     4.8   73.98     8.3   73.98     9.5   74.88    15.8   75.08    17.7   75.78
    18.8   75.78    19.3   75.38    29.3   75.38
#Mann= 3 , 0 , 0
      -9    .035       0       0    .035       0    17.7    .035       0
#XS Ineff= 2 , 0
               0      90    17.7              90
Permanent Ineff=
       F       F
#Block Obstruct= 2 , 0
                            17.7
Bank Sta=0,17.7
XS Rating Curve= 0
Exp/Cntr=.3,.1

Chan Stop Cuts=-1