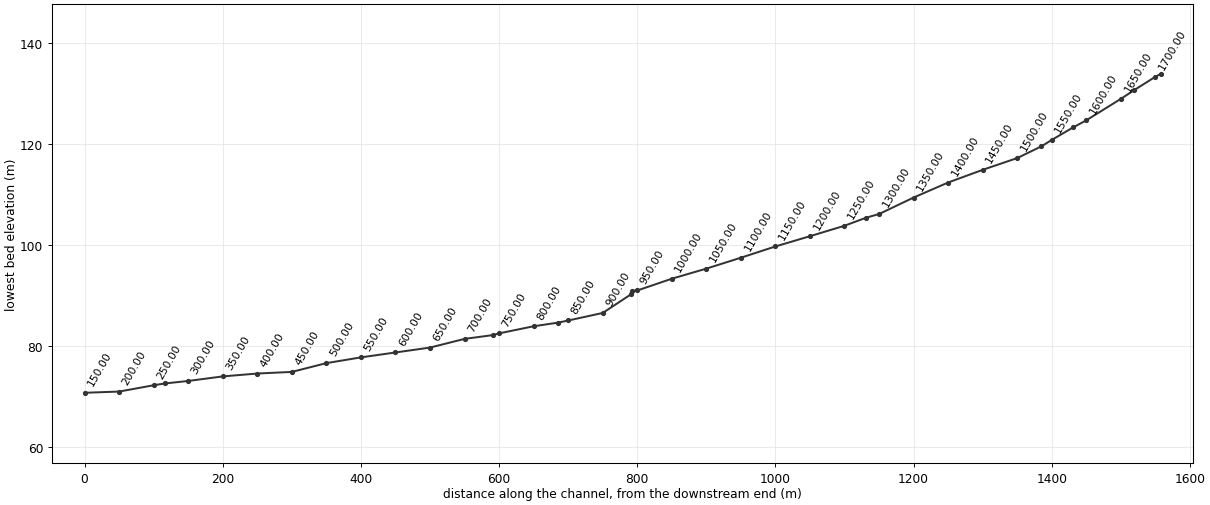
--- EUN.prj (project) ---

Proj Title=EUN
Current Plan=p01
Default Exp/Contr=.3,.1
SI Units
Geom File=g01
Flow File=f01
Plan File=p01
Y Axis Title=Elevation
X Axis Title(PF)=Main Channel Distance
X Axis Title(XS)=Station
BEGIN DESCRIPTION:
           BACK WATER COMPUTATION
      APPLICATION OF HEC-2 BY Samju Construction Engineering
      ensundong-ch: 10,20,30,50,80 yr
END DESCRIPTION:
DSS Export Rating Curves= 0
DSS Export Rating Curve Sorted= 0
DSS Export Volume Flow Curves= 0
DXF OffsetX= 0
DXF OffsetY= 0
DXF ScaleX= 1
DXF ScaleY= 10

--- EUN.p01 (plan) ---

Plan Title=Imported Plan 01
Version=Version 3.0.1  Mar 2001
Short Identifier=Imported Pla
Geom File=g01
Flow File=f01
Subcritical Flow
K Sum by GR= 0
Std Step Tol= 0.003
Critical Tol= 0.003
Num of Std Step Trials= 20
Max Error Tol= 0.1
Flow Tol Ratio= 0.001
Split Flow NTrial= 30
Split Flow Tol= 0.02
Split Flow Ratio= 0.02
Log Output Level= 0
Friction Slope Method= 1
Unsteady Friction Slope Method= 2
Parabolic Critical Depth
Global Vel Dist= 0 , 0 , 0
Global Log Level= 0
CheckData=True
Encroach Param=-1 ,0,0, 0
Computation Interval=1HOUR
Output Interval=1HOUR
Run HTab= 0
Run UNet= 0
Run PostProcess= 0
UNET Theta= 1
UNET ZTol= 0.02
UNET ZSATol= 0.1
UNET MxIter= 20
UNET MaxInSteps= 20
UNET DtIC= 0
UNET DtMin= 0
UNET MaxCRTS= 20
UNET WFStab= 2
UNET SFStab= 1
UNET WFX= 1
UNET SFX= 1
UNET Convert EG Bridges=-1
UNET Use Existing IB Tables=-1
Instantaneous Interval=1HOUR
Write IC File= 0
Write Velocity= 0
Write Detailed= 0

--- EUN.f01 (steady flow) ---

Flow Title=Imported Flow 01
Version=Version 3.0.1  Mar 2001
Number of Profiles= 5
Profile Names=10YR,20YR,30YR,50YR,80YR
River Rch & RM=RIVER-1,Reach-1         ,1708.00
   13.92   15.34   16.17   17.22   18.18
River Rch & RM=RIVER-1,Reach-1         ,500.00
    16.1   17.74    18.7   19.92   21.03
Boundary for River Rch & Prof#=RIVER-1,Reach-1         , 1
Up Type= 0
Dn Type= 3
Dn Slope=.048
Boundary for River Rch & Prof#=RIVER-1,Reach-1         , 2
Up Type= 0
Dn Type= 3
Dn Slope=.048
Boundary for River Rch & Prof#=RIVER-1,Reach-1         , 3
Up Type= 0
Dn Type= 3
Dn Slope=.048
Boundary for River Rch & Prof#=RIVER-1,Reach-1         , 4
Up Type= 0
Dn Type= 3
Dn Slope=.048
Boundary for River Rch & Prof#=RIVER-1,Reach-1         , 5
Up Type= 0
Dn Type= 3
Dn Slope=.048
DSS Import GetInterval= 0
DSS Import GetPeak= 0
DSS Import FillOption= 0

--- EUN.g01 (geometry) ---

Geom Title=Imported Geom 01
Version=Version 3.0.1  Mar 2001

River Reach=RIVER-1         ,Reach-1
Reach XY= 2
              .5             .95              .5             .05

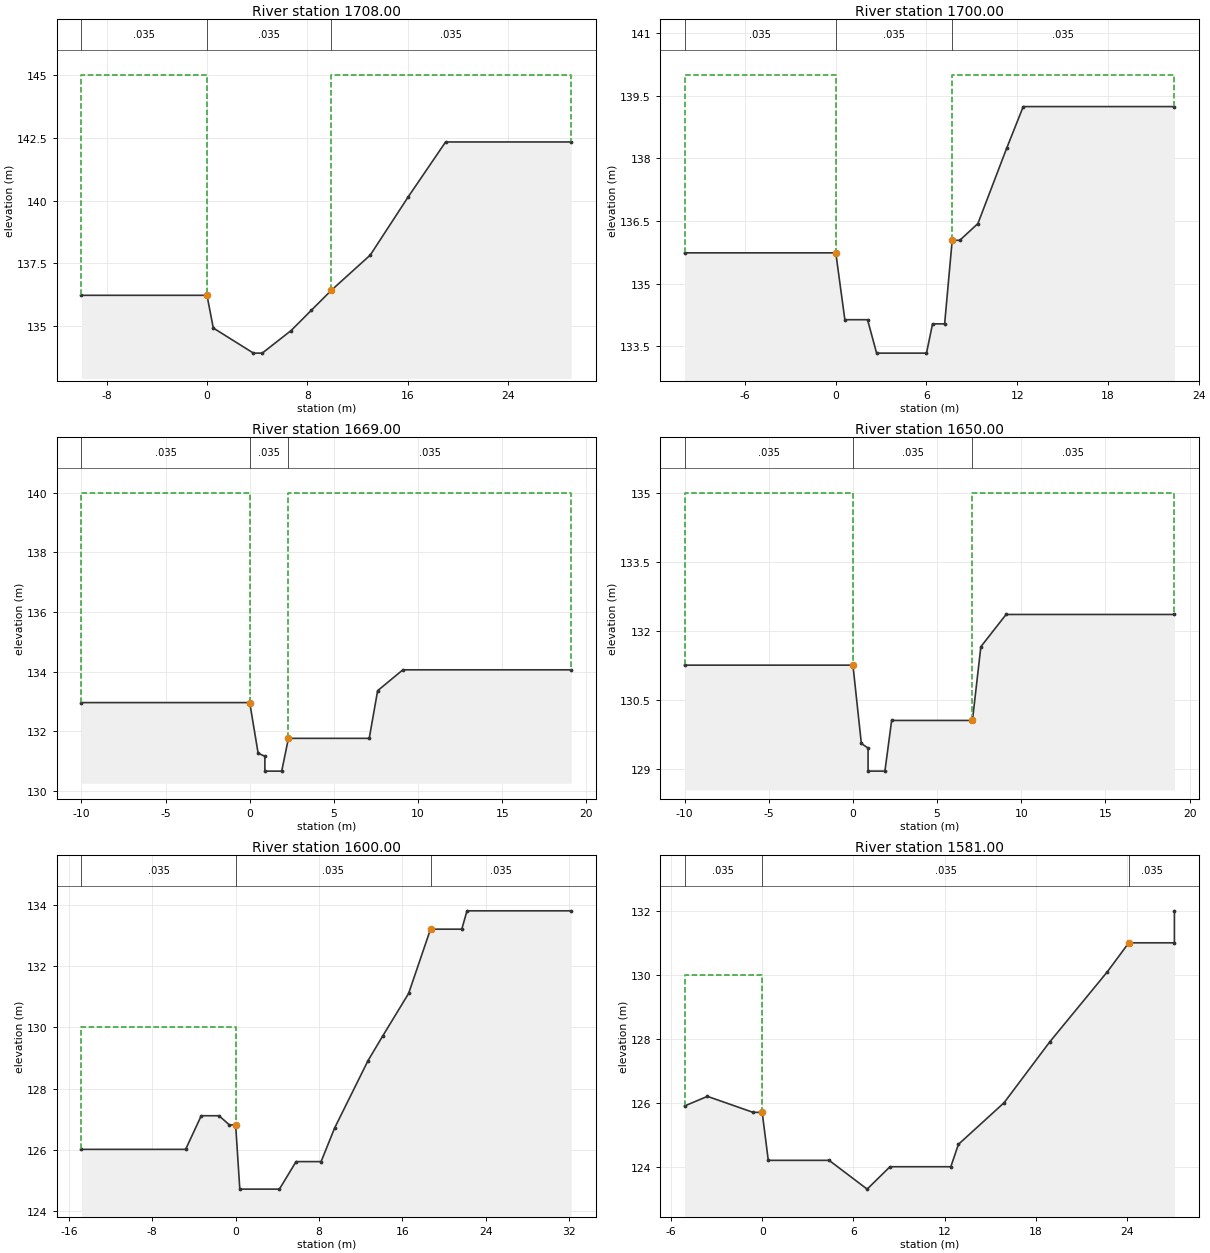
Type RM Length L Ch R = 1 ,1708.00 ,8,8,8
BEGIN DESCRIPTION:
34.008
END DESCRIPTION:
#Sta/Elev= 12
     -10  136.23       0  136.23      .5  134.93     3.7  133.93     4.4  133.93
     6.7  134.83     8.3  135.63     9.9  136.43      13  137.83      16  140.13
      19  142.33      29  142.33
#Mann= 3 , 0 , 0
     -10    .035       0       0    .035       0     9.9    .035       0
#XS Ineff= 2 , 0
               0     145     9.9             145
Permanent Ineff=
       F       F
#Block Obstruct= 2 , 0
                             9.9
Bank Sta=0,9.9
XS Rating Curve= 0
Exp/Cntr=.3,.1

Type RM Length L Ch R = 1 ,1700.00 ,31,31,31
BEGIN DESCRIPTION:
34
END DESCRIPTION:
#Sta/Elev= 14
     -10  135.74       0  135.74      .6  134.14     2.1  134.14     2.7  133.34
       6  133.34     6.4  134.04     7.2  134.04     7.7  136.04     8.2  136.04
     9.4  136.44    11.3  138.24    12.4  139.24    22.4  139.24
#Mann= 3 , 0 , 0
     -10    .035       0       0    .035       0     7.7    .035       0
#XS Ineff= 2 , 0
               0     140     7.7             140
Permanent Ineff=
       F       F
#Block Obstruct= 2 , 0
                             7.7
Bank Sta=0,7.7
XS Rating Curve= 0
Exp/Cntr=.3,.1

Type RM Length L Ch R = 1 ,1669.00 ,19,19,19
BEGIN DESCRIPTION:
33.019
END DESCRIPTION:
#Sta/Elev= 11
     -10  132.96       0  132.96      .5  131.26      .9  131.16      .9  130.66
     1.9  130.66     2.3  131.76     7.1  131.76     7.6  133.36     9.1  134.06
    19.1  134.06
#Mann= 3 , 0 , 0
     -10    .035       0       0    .035       0     2.3    .035       0
#XS Ineff= 2 , 0
               0     140     2.3             140
Permanent Ineff=
       F       F
#Block Obstruct= 2 , 0
                             2.3
Bank Sta=0,2.3
XS Rating Curve= 0
Exp/Cntr=.3,.1

Type RM Length L Ch R = 1 ,1650.00 ,50,50,50
BEGIN DESCRIPTION:
33
END DESCRIPTION:
#Sta/Elev= 11
     -10  131.26       0  131.26      .5  129.56      .9  129.46      .9  128.96
     1.9  128.96     2.3  130.06     7.1  130.06     7.6  131.66     9.1  132.36
    19.1  132.36
#Mann= 3 , 0 , 0
     -10    .035       0       0    .035       0     7.1    .035       0
#XS Ineff= 2 , 0
               0     135     7.1             135
Permanent Ineff=
       F       F
#Block Obstruct= 2 , 0
                             7.1
Bank Sta=0,7.1
XS Rating Curve= 0
Exp/Cntr=.3,.1

Type RM Length L Ch R = 1 ,1600.00 ,19,19,19
BEGIN DESCRIPTION:
32
END DESCRIPTION:
#Sta/Elev= 18
   -14.8  126.01    -4.8  126.01    -3.3  127.11    -1.6  127.11     -.6  126.81
       0  126.81      .4  124.71     4.2  124.71     5.8  125.61     8.2  125.61
     9.5  126.71    12.7  128.91    14.1  129.71    16.6  131.11    18.7  133.21
    21.7  133.21    22.2  133.81    32.2  133.81
#Mann= 3 , 0 , 0
   -14.8    .035       0       0    .035       0    18.7    .035       0
#XS Ineff= 2 , 0
               0     130    18.7             130
Permanent Ineff=
       F       F
#Block Obstruct= 2 , 0
                            18.7
Bank Sta=0,18.7
XS Rating Curve= 0
Exp/Cntr=.3,.1

Type RM Length L Ch R = 1 ,1581.00 ,31,31,31
BEGIN DESCRIPTION:
31.031
END DESCRIPTION:
#Sta/Elev= 16
    -5.1  125.91    -3.6  126.21     -.6  125.71       0  125.71      .4  124.21
     4.4  124.21     6.9  123.31     8.4  124.01    12.4  124.01    12.9  124.71
    15.9  126.01    18.9  127.91    22.7  130.11    24.1  131.01    27.1  131.01
    27.1  132.01
#Mann= 3 , 0 , 0
    -5.1    .035       0       0    .035       0    24.1    .035       0
#XS Ineff= 2 , 0
               0     130    24.1             130
Permanent Ineff=
       F       F
#Block Obstruct= 2 , 0
                            24.1
Bank Sta=0,24.1
XS Rating Curve= 0
Exp/Cntr=.3,.1

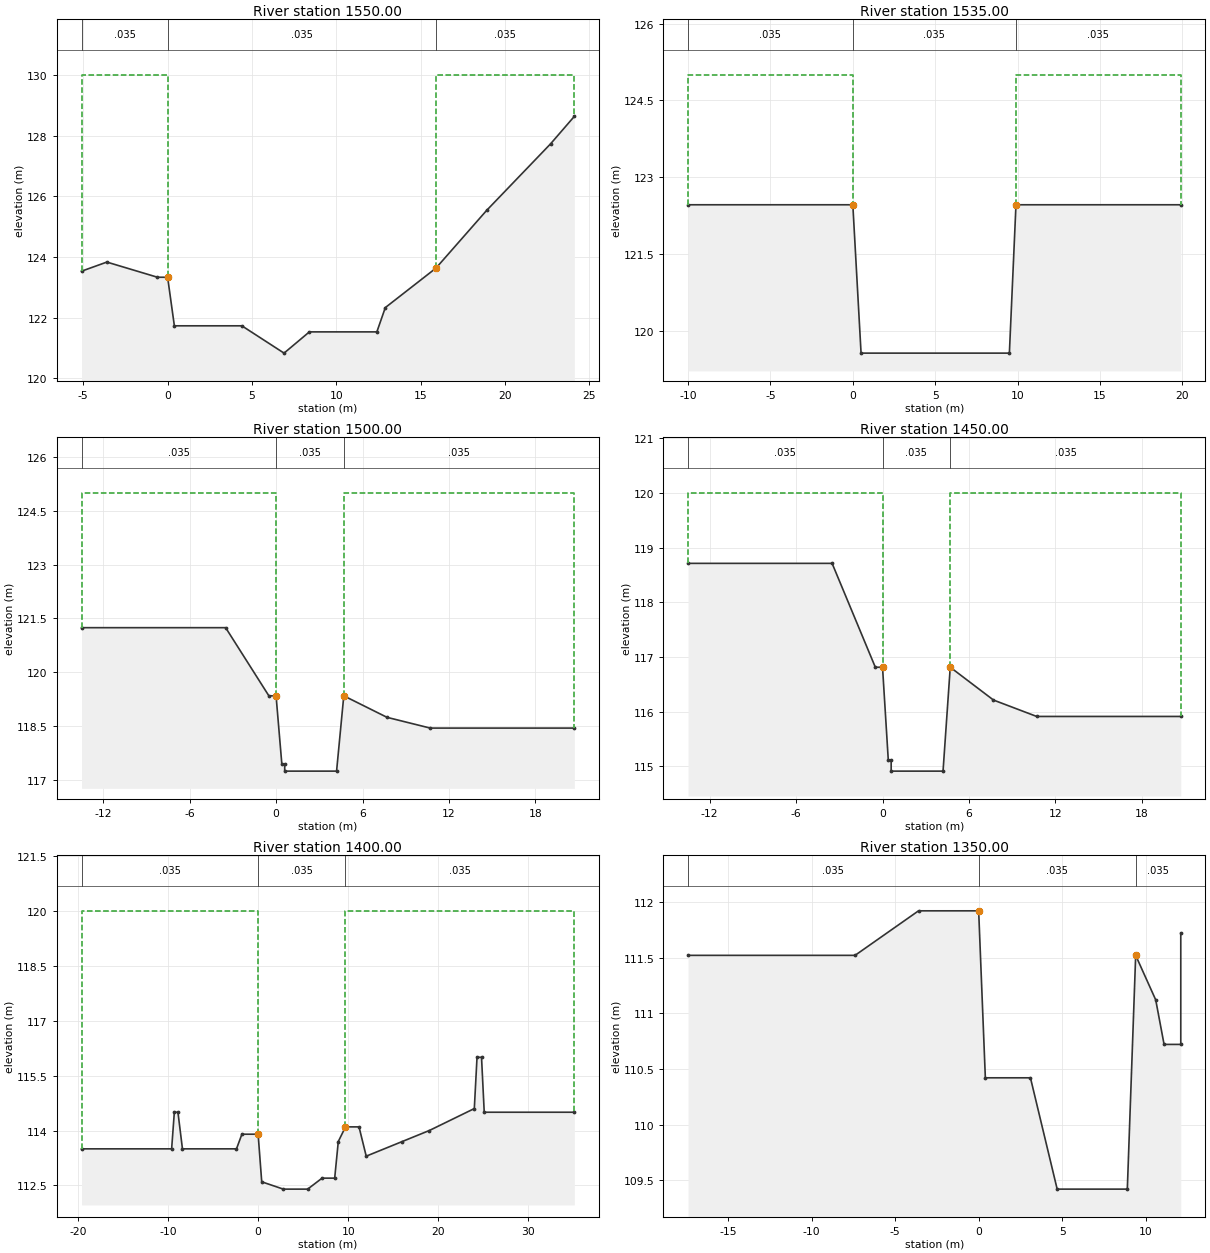
Type RM Length L Ch R = 1 ,1550.00 ,15,15,15
BEGIN DESCRIPTION:
31
END DESCRIPTION:
#Sta/Elev= 14
    -5.1  123.53    -3.6  123.83     -.6  123.33       0  123.33      .4  121.73
     4.4  121.73     6.9  120.83     8.4  121.53    12.4  121.53    12.9  122.33
    15.9  123.63    18.9  125.53    22.7  127.73    24.1  128.63
#Mann= 3 , 0 , 0
    -5.1    .035       0       0    .035       0    15.9    .035       0
#XS Ineff= 2 , 0
               0     130    15.9             130
Permanent Ineff=
       F       F
#Block Obstruct= 2 , 0
                            15.9
Bank Sta=0,15.9
XS Rating Curve= 0
Exp/Cntr=.3,.1

Type RM Length L Ch R = 1 ,1535.00 ,35,35,35
BEGIN DESCRIPTION:
30.035
END DESCRIPTION:
#Sta/Elev= 6
     -10  122.46       0  122.46      .5  119.56     9.5  119.56     9.9  122.46
    19.9  122.46
#Mann= 3 , 0 , 0
     -10    .035       0       0    .035       0     9.9    .035       0
#XS Ineff= 2 , 0
               0     125     9.9             125
Permanent Ineff=
       F       F
#Block Obstruct= 2 , 0
                             9.9
Bank Sta=0,9.9
XS Rating Curve= 0
Exp/Cntr=.3,.1

Type RM Length L Ch R = 1 ,1500.00 ,50,50,50
BEGIN DESCRIPTION:
30
END DESCRIPTION:
#Sta/Elev= 12
   -13.5  121.24    -3.5  121.24     -.5  119.34       0  119.34      .4  117.44
      .6  117.44      .6  117.24     4.2  117.24     4.7  119.34     7.7  118.74
    10.7  118.44    20.7  118.44
#Mann= 3 , 0 , 0
   -13.5    .035       0       0    .035       0     4.7    .035       0
#XS Ineff= 2 , 0
               0     125     4.7             125
Permanent Ineff=
       F       F
#Block Obstruct= 2 , 0
                             4.7
Bank Sta=0,4.7
XS Rating Curve= 0
Exp/Cntr=.3,.1

Type RM Length L Ch R = 1 ,1450.00 ,50,50,50
BEGIN DESCRIPTION:
29
END DESCRIPTION:
#Sta/Elev= 12
   -13.5  118.71    -3.5  118.71     -.5  116.81       0  116.81      .4  115.11
      .6  115.11      .6  114.91     4.2  114.91     4.7  116.81     7.7  116.21
    10.7  115.91    20.7  115.91
#Mann= 3 , 0 , 0
   -13.5    .035       0       0    .035       0     4.7    .035       0
#XS Ineff= 2 , 0
               0     120     4.7             120
Permanent Ineff=
       F       F
#Block Obstruct= 2 , 0
                             4.7
Bank Sta=0,4.7
XS Rating Curve= 0
Exp/Cntr=.3,.1

Type RM Length L Ch R = 1 ,1400.00 ,50,50,50
BEGIN DESCRIPTION:
28
END DESCRIPTION:
#Sta/Elev= 24
   -19.6   113.5    -9.6   113.5    -9.3   114.5    -8.9   114.5    -8.4   113.5
    -2.4   113.5    -1.8   113.9       0   113.9      .4   112.6     2.8   112.4
     5.5   112.4     7.1   112.7     8.5   112.7     8.9   113.7     9.7   114.1
    11.2   114.1      12   113.3      16   113.7      19     114      24   114.6
    24.3     116    24.8     116    25.1   114.5    35.1   114.5
#Mann= 3 , 0 , 0
   -19.6    .035       0       0    .035       0     9.7    .035       0
#XS Ineff= 2 , 0
               0     120     9.7             120
Permanent Ineff=
       F       F
#Block Obstruct= 2 , 0
                             9.7
Bank Sta=0,9.7
XS Rating Curve= 0
Exp/Cntr=.3,.1

Type RM Length L Ch R = 1 ,1350.00 ,50,50,50
BEGIN DESCRIPTION:
27
END DESCRIPTION:
#Sta/Elev= 13
   -17.4  111.52    -7.4  111.52    -3.6  111.92       0  111.92      .4  110.42
     3.1  110.42     4.7  109.42     8.9  109.42     9.4  111.52    10.6  111.12
    11.1  110.72    12.1  110.72    12.1  111.72
#Mann= 3 , 0 , 0
   -17.4    .035       0       0    .035       0     9.4    .035       0
#XS Ineff= 2 , 0
               0     120     9.4             120
Permanent Ineff=
       F       F
#Block Obstruct= 2 , 0
                             9.4
Bank Sta=0,9.4
XS Rating Curve= 0
Exp/Cntr=.3,.1

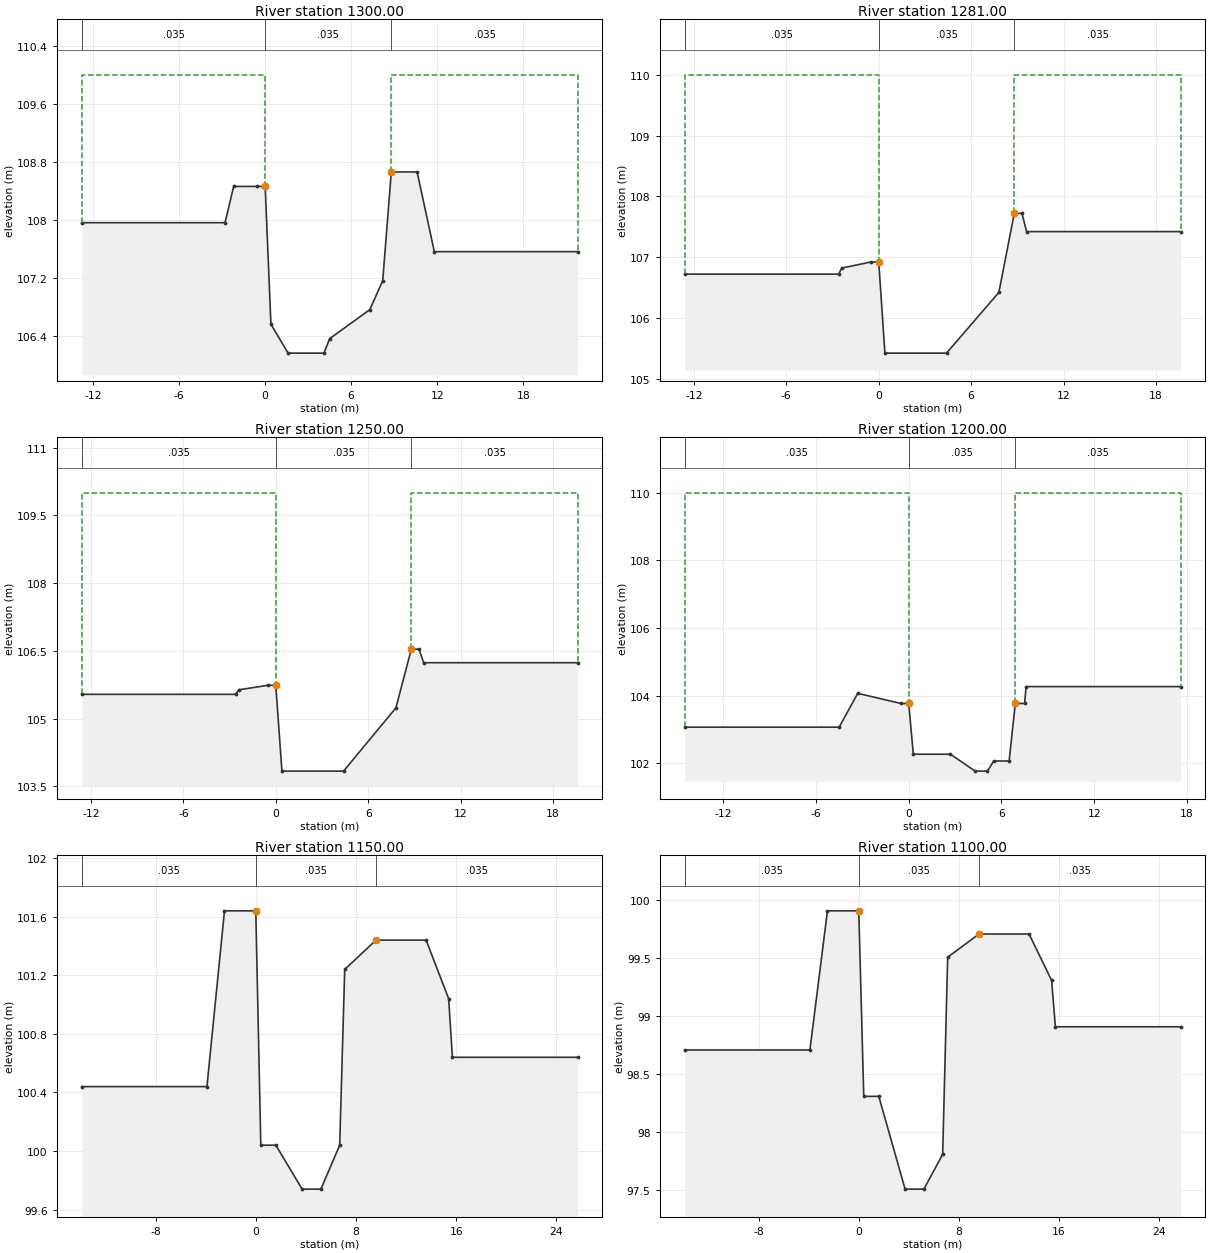
Type RM Length L Ch R = 1 ,1300.00 ,19,19,19
BEGIN DESCRIPTION:
26
END DESCRIPTION:
#Sta/Elev= 15
   -12.8  107.96    -2.8  107.96    -2.2  108.46     -.6  108.46       0  108.46
      .4  106.56     1.6  106.16     4.1  106.16     4.5  106.36     7.3  106.76
     8.2  107.16     8.8  108.66    10.6  108.66    11.8  107.56    21.8  107.56
#Mann= 3 , 0 , 0
   -12.8    .035       0       0    .035       0     8.8    .035       0
#XS Ineff= 2 , 0
               0     110     8.8             110
Permanent Ineff=
       F       F
#Block Obstruct= 2 , 0
                             8.8
Bank Sta=0,8.8
XS Rating Curve= 0
Exp/Cntr=.3,.1

Type RM Length L Ch R = 1 ,1281.00 ,31,31,31
BEGIN DESCRIPTION:
25.031
END DESCRIPTION:
#Sta/Elev= 12
   -12.6  106.72    -2.6  106.72    -2.4  106.82     -.5  106.92       0  106.92
      .4  105.42     4.4  105.42     7.8  106.42     8.8  107.72     9.3  107.72
     9.6  107.42    19.6  107.42
#Mann= 3 , 0 , 0
   -12.6    .035       0       0    .035       0     8.8    .035       0
#XS Ineff= 2 , 0
               0     110     8.8             110
Permanent Ineff=
       F       F
#Block Obstruct= 2 , 0
                             8.8
Bank Sta=0,8.8
XS Rating Curve= 0
Exp/Cntr=.3,.1

Type RM Length L Ch R = 1 ,1250.00 ,50,50,50
BEGIN DESCRIPTION:
25
END DESCRIPTION:
#Sta/Elev= 12
   -12.6  105.54    -2.6  105.54    -2.4  105.64     -.5  105.74       0  105.74
      .4  103.84     4.4  103.84     7.8  105.24     8.8  106.54     9.3  106.54
     9.6  106.24    19.6  106.24
#Mann= 3 , 0 , 0
   -12.6    .035       0       0    .035       0     8.8    .035       0
#XS Ineff= 2 , 0
               0     110     8.8             110
Permanent Ineff=
       F       F
#Block Obstruct= 2 , 0
                             8.8
Bank Sta=0,8.8
XS Rating Curve= 0
Exp/Cntr=.3,.1

Type RM Length L Ch R = 1 ,1200.00 ,50,50,50
BEGIN DESCRIPTION:
24
END DESCRIPTION:
#Sta/Elev= 15
   -14.5  103.07    -4.5  103.07    -3.3  104.07     -.5  103.77       0  103.77
      .3  102.27     2.7  102.27     4.3  101.77     5.1  101.77     5.5  102.07
     6.5  102.07     6.9  103.77     7.5  103.77     7.6  104.27    17.6  104.27
#Mann= 3 , 0 , 0
   -14.5    .035       0       0    .035       0     6.9    .035       0
#XS Ineff= 2 , 0
               0     110     6.9             110
Permanent Ineff=
       F       F
#Block Obstruct= 2 , 0
                             6.9
Bank Sta=0,6.9
XS Rating Curve= 0
Exp/Cntr=.3,.1

Type RM Length L Ch R = 1 ,1150.00 ,50,50,50
BEGIN DESCRIPTION:
23
END DESCRIPTION:
#Sta/Elev= 15
   -13.9  100.44    -3.9  100.44    -2.5  101.64       0  101.64      .4  100.04
     1.6  100.04     3.7   99.74     5.2   99.74     6.7  100.04     7.1  101.24
     9.6  101.44    13.6  101.44    15.4  101.04    15.7  100.64    25.7  100.64
#Mann= 3 , 0 , 0
   -13.9    .035       0       0    .035       0     9.6    .035       0
#XS Ineff= 2 , 0
               0     110     9.6             110
Permanent Ineff=
       F       F
#Block Obstruct= 2 , 0
                             9.6
Bank Sta=0,9.6
XS Rating Curve= 0
Exp/Cntr=.3,.1

Type RM Length L Ch R = 1 ,1100.00 ,50,50,50
BEGIN DESCRIPTION:
22
END DESCRIPTION:
#Sta/Elev= 15
   -13.9   98.71    -3.9   98.71    -2.5   99.91       0   99.91      .4   98.31
     1.6   98.31     3.7   97.51     5.2   97.51     6.7   97.81     7.1   99.51
     9.6   99.71    13.6   99.71    15.4   99.31    15.7   98.91    25.7   98.91
#Mann= 3 , 0 , 0
   -13.9    .035       0       0    .035       0     9.6    .035       0
#XS Ineff= 2 , 0
               0     110     9.6             110
Permanent Ineff=
       F       F
#Block Obstruct= 2 , 0
                             9.6
Bank Sta=0,9.6
XS Rating Curve= 0
Exp/Cntr=.3,.1

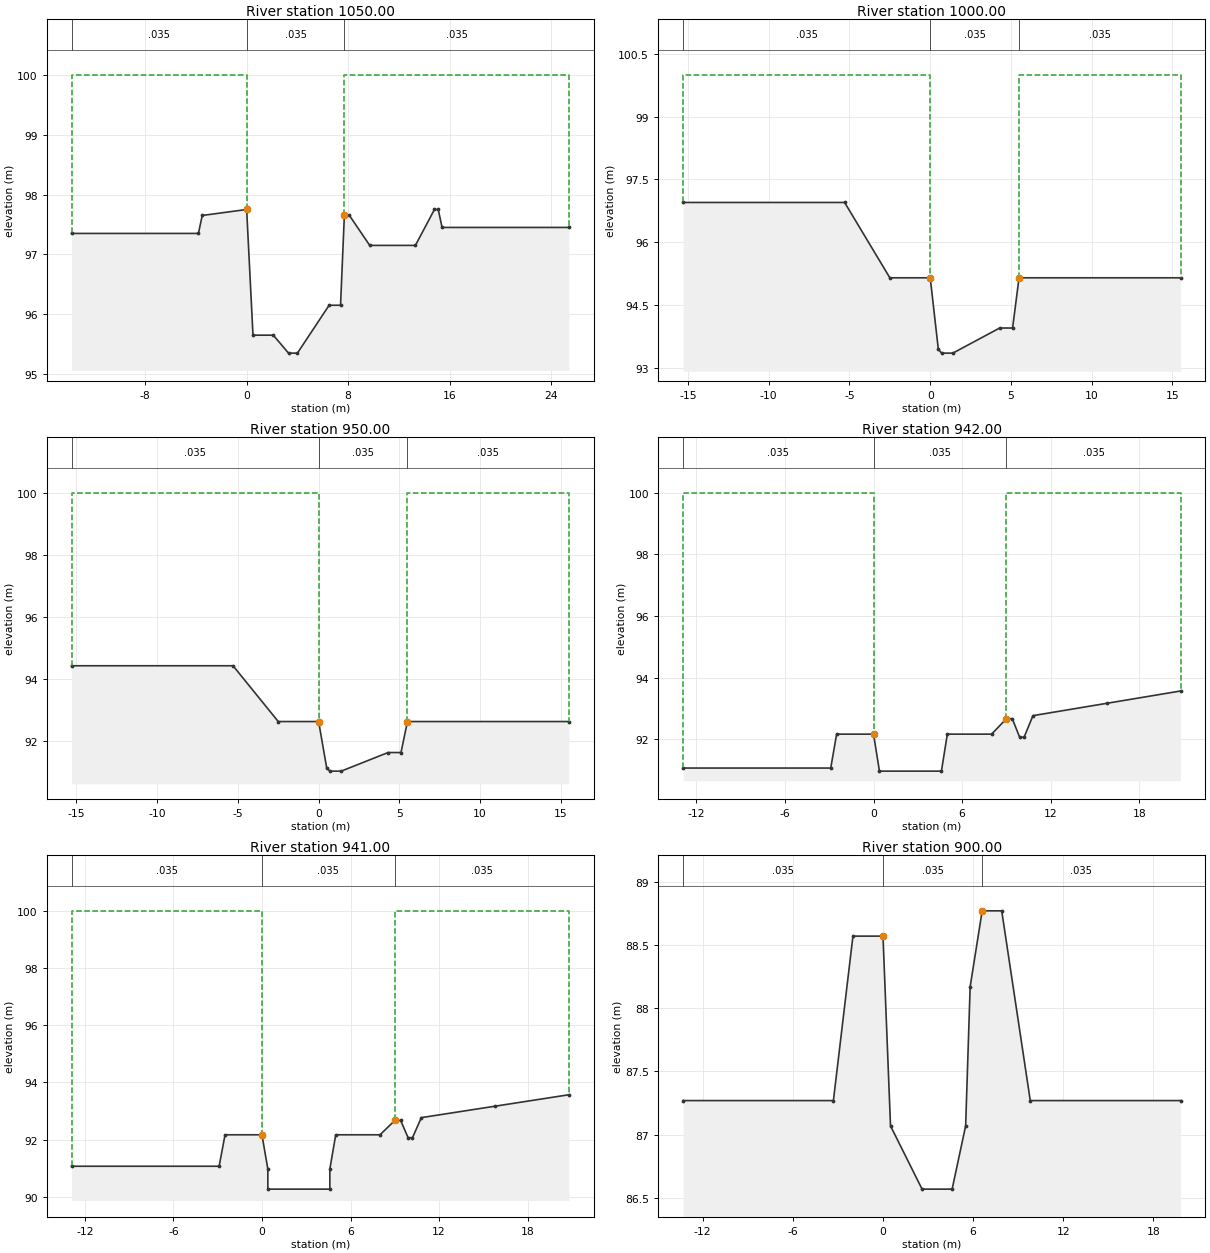
Type RM Length L Ch R = 1 ,1050.00 ,50,50,50
BEGIN DESCRIPTION:
21
END DESCRIPTION:
#Sta/Elev= 18
   -13.8   97.35    -3.8   97.35    -3.5   97.65       0   97.75      .5   95.65
     2.1   95.65     3.3   95.35       4   95.35     6.5   96.15     7.4   96.15
     7.7   97.65     8.1   97.65     9.7   97.15    13.3   97.15    14.8   97.75
    15.1   97.75    15.4   97.45    25.4   97.45
#Mann= 3 , 0 , 0
   -13.8    .035       0       0    .035       0     7.7    .035       0
#XS Ineff= 2 , 0
               0     100     7.7             100
Permanent Ineff=
       F       F
#Block Obstruct= 2 , 0
                             7.7
Bank Sta=0,7.7
XS Rating Curve= 0
Exp/Cntr=.3,.1

Type RM Length L Ch R = 1 ,1000.00 ,50,50,50
BEGIN DESCRIPTION:
20
END DESCRIPTION:
#Sta/Elev= 11
   -15.3   96.95    -5.3   96.95    -2.5   95.15       0   95.15      .5   93.45
      .7   93.35     1.4   93.35     4.3   93.95     5.1   93.95     5.5   95.15
    15.5   95.15
#Mann= 3 , 0 , 0
   -15.3    .035       0       0    .035       0     5.5    .035       0
#XS Ineff= 2 , 0
               0     100     5.5             100
Permanent Ineff=
       F       F
#Block Obstruct= 2 , 0
                             5.5
Bank Sta=0,5.5
XS Rating Curve= 0
Exp/Cntr=.3,.1

Type RM Length L Ch R = 1 ,950.00  ,8,8,8
BEGIN DESCRIPTION:
19
END DESCRIPTION:
#Sta/Elev= 11
   -15.3   94.42    -5.3   94.42    -2.5   92.62       0   92.62      .5   91.12
      .7   91.02     1.4   91.02     4.3   91.62     5.1   91.62     5.5   92.62
    15.5   92.62
#Mann= 3 , 0 , 0
   -15.3    .035       0       0    .035       0     5.5    .035       0
#XS Ineff= 2 , 0
               0     100     5.5             100
Permanent Ineff=
       F       F
#Block Obstruct= 2 , 0
                             5.5
Bank Sta=0,5.5
XS Rating Curve= 0
Exp/Cntr=.3,.1

Type RM Length L Ch R = 1 ,942.00  ,1,1,1
BEGIN DESCRIPTION:
18.042
END DESCRIPTION:
#Sta/Elev= 15
   -12.9   91.07    -2.9   91.07    -2.5   92.17       0   92.17      .4   90.97
     4.6   90.97       5   92.17       8   92.17       9   92.67     9.4   92.67
     9.9   92.07    10.2   92.07    10.8   92.77    15.8   93.17    20.8   93.57
#Mann= 3 , 0 , 0
   -12.9    .035       0       0    .035       0       9    .035       0
#XS Ineff= 2 , 0
               0     100       9             100
Permanent Ineff=
       F       F
#Block Obstruct= 2 , 0
                               9
Bank Sta=0,9
XS Rating Curve= 0
Exp/Cntr=.3,.1

Type RM Length L Ch R = 1 ,941.00  ,41,41,41
BEGIN DESCRIPTION:
18.041
END DESCRIPTION:
#Sta/Elev= 17
   -12.9   91.07    -2.9   91.07    -2.5   92.17       0   92.17      .4   90.97
      .4   90.27     4.6   90.27     4.6   90.97       5   92.17       8   92.17
       9   92.67     9.4   92.67     9.9   92.07    10.2   92.07    10.8   92.77
    15.8   93.17    20.8   93.57
#Mann= 3 , 0 , 0
   -12.9    .035       0       0    .035       0       9    .035       0
#XS Ineff= 2 , 0
               0     100       9             100
Permanent Ineff=
       F       F
#Block Obstruct= 2 , 0
                               9
Bank Sta=0,9
XS Rating Curve= 0
Exp/Cntr=.3,.1

Type RM Length L Ch R = 1 ,900.00  ,50,50,50
BEGIN DESCRIPTION:
18
END DESCRIPTION:
#Sta/Elev= 13
   -13.3   87.27    -3.3   87.27      -2   88.57       0   88.57      .5   87.07
     2.6   86.57     4.6   86.57     5.5   87.07     5.8   88.17     6.6   88.77
     7.9   88.77     9.8   87.27    19.8   87.27
#Mann= 3 , 0 , 0
   -13.3    .035       0       0    .035       0     6.6    .035       0
#XS Ineff= 2 , 0
               0     100     6.6             100
Permanent Ineff=
       F       F
#Block Obstruct= 2 , 0
                             6.6
Bank Sta=0,6.6
XS Rating Curve= 0
Exp/Cntr=.3,.1

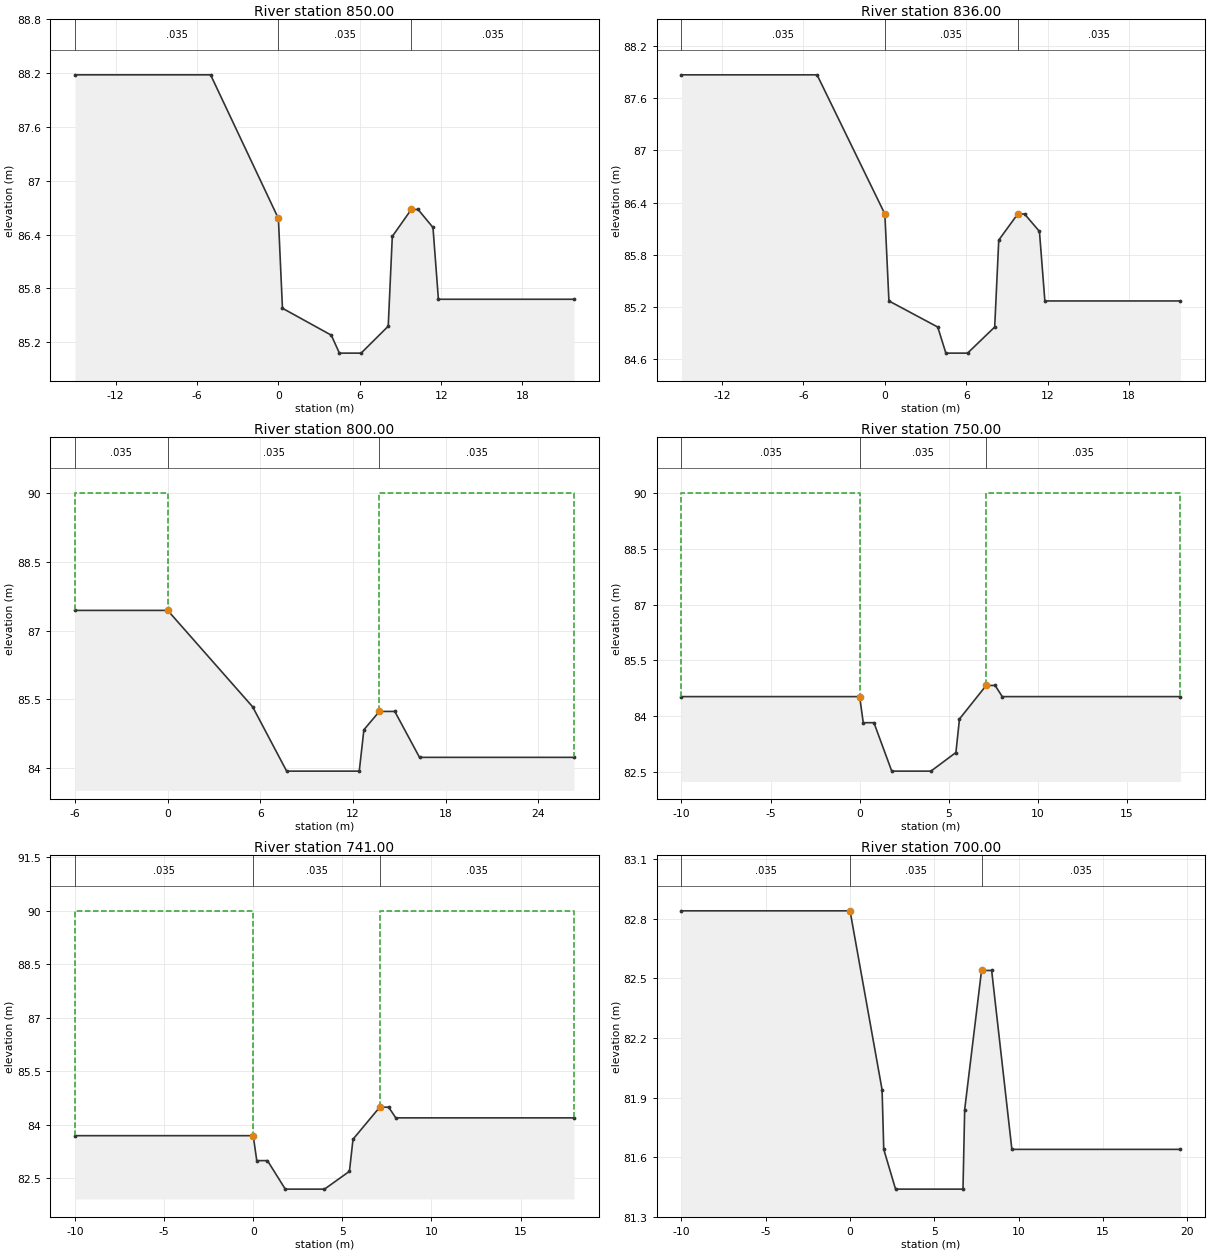
Type RM Length L Ch R = 1 ,850.00  ,14,14,14
BEGIN DESCRIPTION:
17
END DESCRIPTION:
#Sta/Elev= 14
     -15   88.18      -5   88.18       0   86.58      .3   85.58     3.9   85.28
     4.5   85.08     6.1   85.08     8.1   85.38     8.4   86.38     9.8   86.68
    10.3   86.68    11.4   86.48    11.8   85.68    21.8   85.68
#Mann= 3 , 0 , 0
     -15    .035       0       0    .035       0     9.8    .035       0
#XS Ineff= 2 , 0
               0     100     9.8             100
Permanent Ineff=
       F       F
#Block Obstruct= 2 , 0
                             9.8
Bank Sta=0,9.8
XS Rating Curve= 0
Exp/Cntr=.3,.1

Type RM Length L Ch R = 1 ,836.00  ,36,36,36
BEGIN DESCRIPTION:
16.036
END DESCRIPTION:
#Sta/Elev= 14
     -15   87.87      -5   87.87       0   86.27      .3   85.27     3.9   84.97
     4.5   84.67     6.1   84.67     8.1   84.97     8.4   85.97     9.8   86.27
    10.3   86.27    11.4   86.07    11.8   85.27    21.8   85.27
#Mann= 3 , 0 , 0
     -15    .035       0       0    .035       0     9.8    .035       0
#XS Ineff= 2 , 0
               0     100     9.8             100
Permanent Ineff=
       F       F
#Block Obstruct= 2 , 0
                             9.8
Bank Sta=0,9.8
XS Rating Curve= 0
Exp/Cntr=.3,.1

Type RM Length L Ch R = 1 ,800.00  ,50,50,50
BEGIN DESCRIPTION:
16
END DESCRIPTION:
#Sta/Elev= 10
      -6   87.44       0   87.44     5.5   85.34     7.7   83.94    12.4   83.94
    12.7   84.84    13.7   85.24    14.7   85.24    16.3   84.24    26.3   84.24
#Mann= 3 , 0 , 0
      -6    .035       0       0    .035       0    13.7    .035       0
#XS Ineff= 2 , 0
               0      90    13.7              90
Permanent Ineff=
       F       F
#Block Obstruct= 2 , 0
                            13.7
Bank Sta=0,13.7
XS Rating Curve= 0
Exp/Cntr=.3,.1

Type RM Length L Ch R = 1 ,750.00  ,9,9,9
BEGIN DESCRIPTION:
15
END DESCRIPTION:
#Sta/Elev= 12
     -10   84.53       0   84.53      .2   83.83      .8   83.83     1.8   82.53
       4   82.53     5.4   83.03     5.6   83.93     7.1   84.83     7.6   84.83
       8   84.53      18   84.53
#Mann= 3 , 0 , 0
     -10    .035       0       0    .035       0     7.1    .035       0
#XS Ineff= 2 , 0
               0      90     7.1              90
Permanent Ineff=
       F       F
#Block Obstruct= 2 , 0
                             7.1
Bank Sta=0,7.1
XS Rating Curve= 0
Exp/Cntr=.3,.1

Type RM Length L Ch R = 1 ,741.00  ,41,41,41
BEGIN DESCRIPTION:
14.041
END DESCRIPTION:
#Sta/Elev= 12
     -10   83.69       0   83.69      .2   82.99      .8   82.99     1.8   82.19
       4   82.19     5.4   82.69     5.6   83.59     7.1   84.49     7.6   84.49
       8   84.19      18   84.19
#Mann= 3 , 0 , 0
     -10    .035       0       0    .035       0     7.1    .035       0
#XS Ineff= 2 , 0
               0      90     7.1              90
Permanent Ineff=
       F       F
#Block Obstruct= 2 , 0
                             7.1
Bank Sta=0,7.1
XS Rating Curve= 0
Exp/Cntr=.3,.1

Type RM Length L Ch R = 1 ,700.00  ,50,50,50
BEGIN DESCRIPTION:
14
END DESCRIPTION:
#Sta/Elev= 11
     -10   82.84       0   82.84     1.9   81.94       2   81.64     2.7   81.44
     6.7   81.44     6.8   81.84     7.8   82.54     8.4   82.54     9.6   81.64
    19.6   81.64
#Mann= 3 , 0 , 0
     -10    .035       0       0    .035       0     7.8    .035       0
#XS Ineff= 2 , 0
               0      90     7.8              90
Permanent Ineff=
       F       F
#Block Obstruct= 2 , 0
                             7.8
Bank Sta=0,7.8
XS Rating Curve= 0
Exp/Cntr=.3,.1

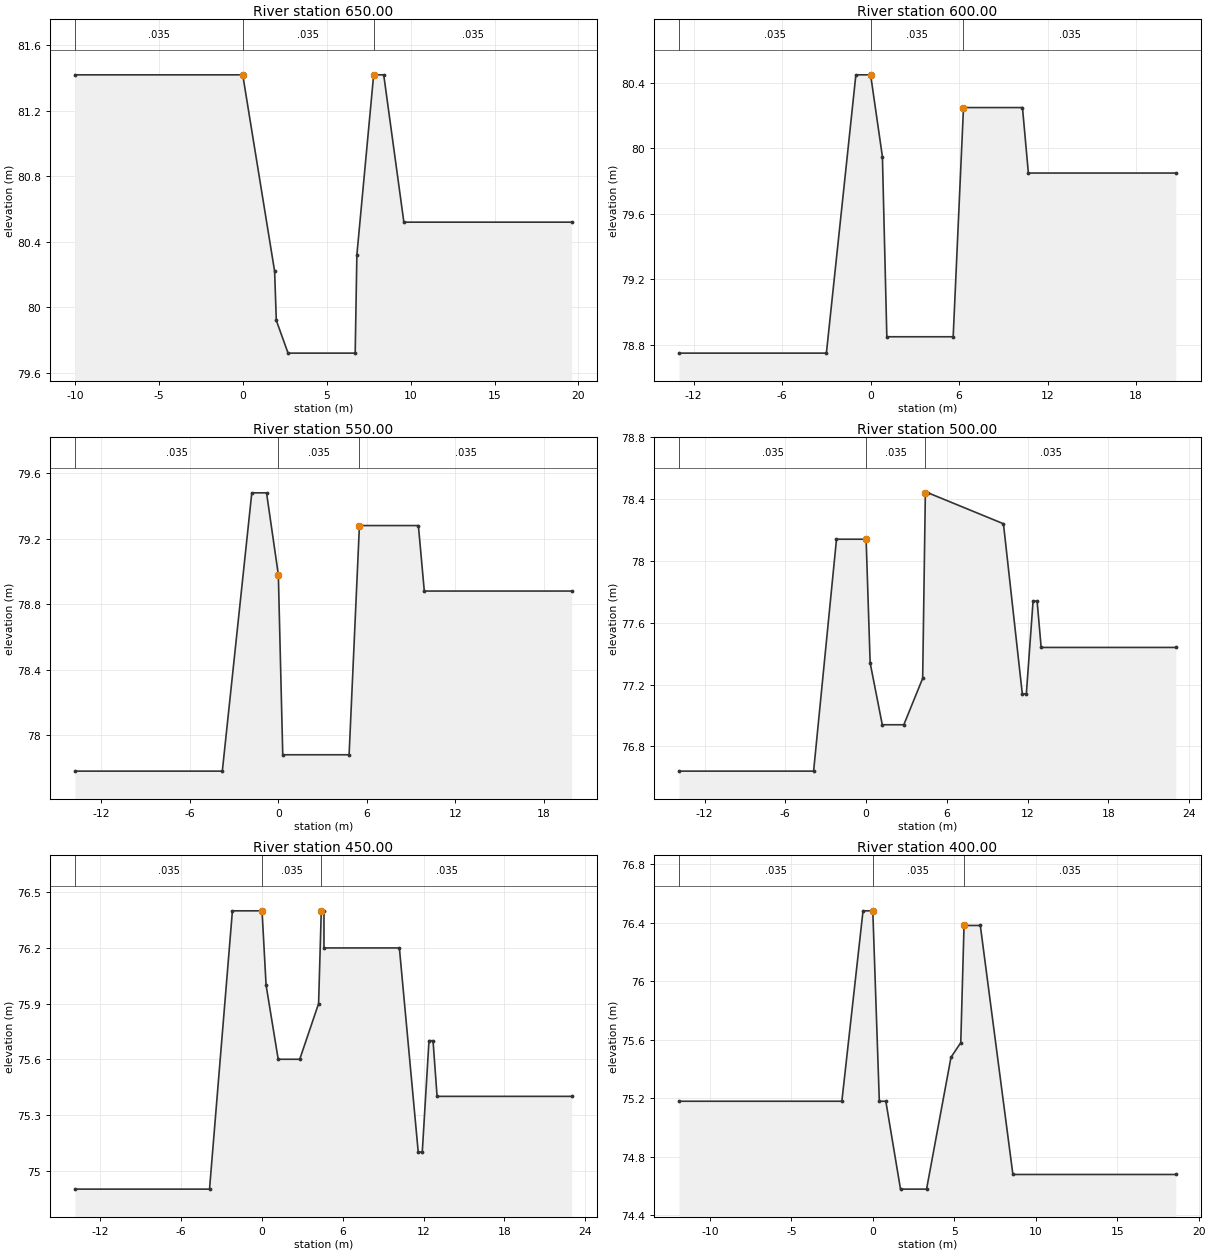
Type RM Length L Ch R = 1 ,650.00  ,50,50,50
BEGIN DESCRIPTION:
13
END DESCRIPTION:
#Sta/Elev= 11
     -10   81.42       0   81.42     1.9   80.22       2   79.92     2.7   79.72
     6.7   79.72     6.8   80.32     7.8   81.42     8.4   81.42     9.6   80.52
    19.6   80.52
#Mann= 3 , 0 , 0
     -10    .035       0       0    .035       0     7.8    .035       0
#XS Ineff= 2 , 0
               0      90     7.8              90
Permanent Ineff=
       F       F
#Block Obstruct= 2 , 0
                             7.8
Bank Sta=0,7.8
XS Rating Curve= 0
Exp/Cntr=.3,.1

Type RM Length L Ch R = 1 ,600.00  ,50,50,50
BEGIN DESCRIPTION:
12
END DESCRIPTION:
#Sta/Elev= 11
     -13   78.75      -3   78.75      -1   80.45       0   80.45      .8   79.95
     1.1   78.85     5.6   78.85     6.3   80.25    10.3   80.25    10.7   79.85
    20.7   79.85
#Mann= 3 , 0 , 0
     -13    .035       0       0    .035       0     6.3    .035       0
#XS Ineff= 2 , 0
               0      90     6.3              90
Permanent Ineff=
       F       F
#Block Obstruct= 2 , 0
                             6.3
Bank Sta=0,6.3
XS Rating Curve= 0
Exp/Cntr=.3,.1

Type RM Length L Ch R = 1 ,550.00  ,50,50,50
BEGIN DESCRIPTION:
11
END DESCRIPTION:
#Sta/Elev= 11
   -13.8   77.78    -3.8   77.78    -1.8   79.48     -.8   79.48       0   78.98
      .3   77.88     4.8   77.88     5.5   79.28     9.5   79.28     9.9   78.88
    19.9   78.88
#Mann= 3 , 0 , 0
   -13.8    .035       0       0    .035       0     5.5    .035       0
#XS Ineff= 2 , 0
               0      90     5.5              90
Permanent Ineff=
       F       F
#Block Obstruct= 2 , 0
                             5.5
Bank Sta=0,5.5
XS Rating Curve= 0
Exp/Cntr=.3,.1

Type RM Length L Ch R = 1 ,500.00  ,50,50,50
BEGIN DESCRIPTION:
10
END DESCRIPTION:
#Sta/Elev= 17
   -13.9   76.64    -3.9   76.64    -2.2   78.14       0   78.14      .3   77.34
     1.2   76.94     2.8   76.94     4.2   77.24     4.4   78.44     4.6   78.44
    10.2   78.24    11.6   77.14    11.9   77.14    12.4   77.74    12.7   77.74
      13   77.44      23   77.44
#Mann= 3 , 0 , 0
   -13.9    .035       0       0    .035       0     4.4    .035       0
#XS Ineff= 2 , 0
               0      90     4.4              90
Permanent Ineff=
       F       F
#Block Obstruct= 2 , 0
                             4.4
Bank Sta=0,4.4
XS Rating Curve= 0
Exp/Cntr=.3,.1

Type RM Length L Ch R = 1 ,450.00  ,50,50,50
BEGIN DESCRIPTION:
9
END DESCRIPTION:
#Sta/Elev= 18
   -13.9    74.9    -3.9    74.9    -2.2    76.4       0    76.4      .3      76
     1.2    75.6     2.8    75.6     4.2    75.9     4.4    76.4     4.6    76.4
     4.6    76.2    10.2    76.2    11.6    75.1    11.9    75.1    12.4    75.7
    12.7    75.7      13    75.4      23    75.4
#Mann= 3 , 0 , 0
   -13.9    .035       0       0    .035       0     4.4    .035       0
#XS Ineff= 2 , 0
               0      90     4.4              90
Permanent Ineff=
       F       F
#Block Obstruct= 2 , 0
                             4.4
Bank Sta=0,4.4
XS Rating Curve= 0
Exp/Cntr=.3,.1

Type RM Length L Ch R = 1 ,400.00  ,50,50,50
BEGIN DESCRIPTION:
8
END DESCRIPTION:
#Sta/Elev= 14
   -11.9   75.18    -1.9   75.18     -.6   76.48       0   76.48      .4   75.18
      .8   75.18     1.7   74.58     3.3   74.58     4.8   75.48     5.4   75.58
     5.6   76.38     6.6   76.38     8.6   74.68    18.6   74.68
#Mann= 3 , 0 , 0
   -11.9    .035       0       0    .035       0     5.6    .035       0
#XS Ineff= 2 , 0
               0      90     5.6              90
Permanent Ineff=
       F       F
#Block Obstruct= 2 , 0
                             5.6
Bank Sta=0,5.6
XS Rating Curve= 0
Exp/Cntr=.3,.1

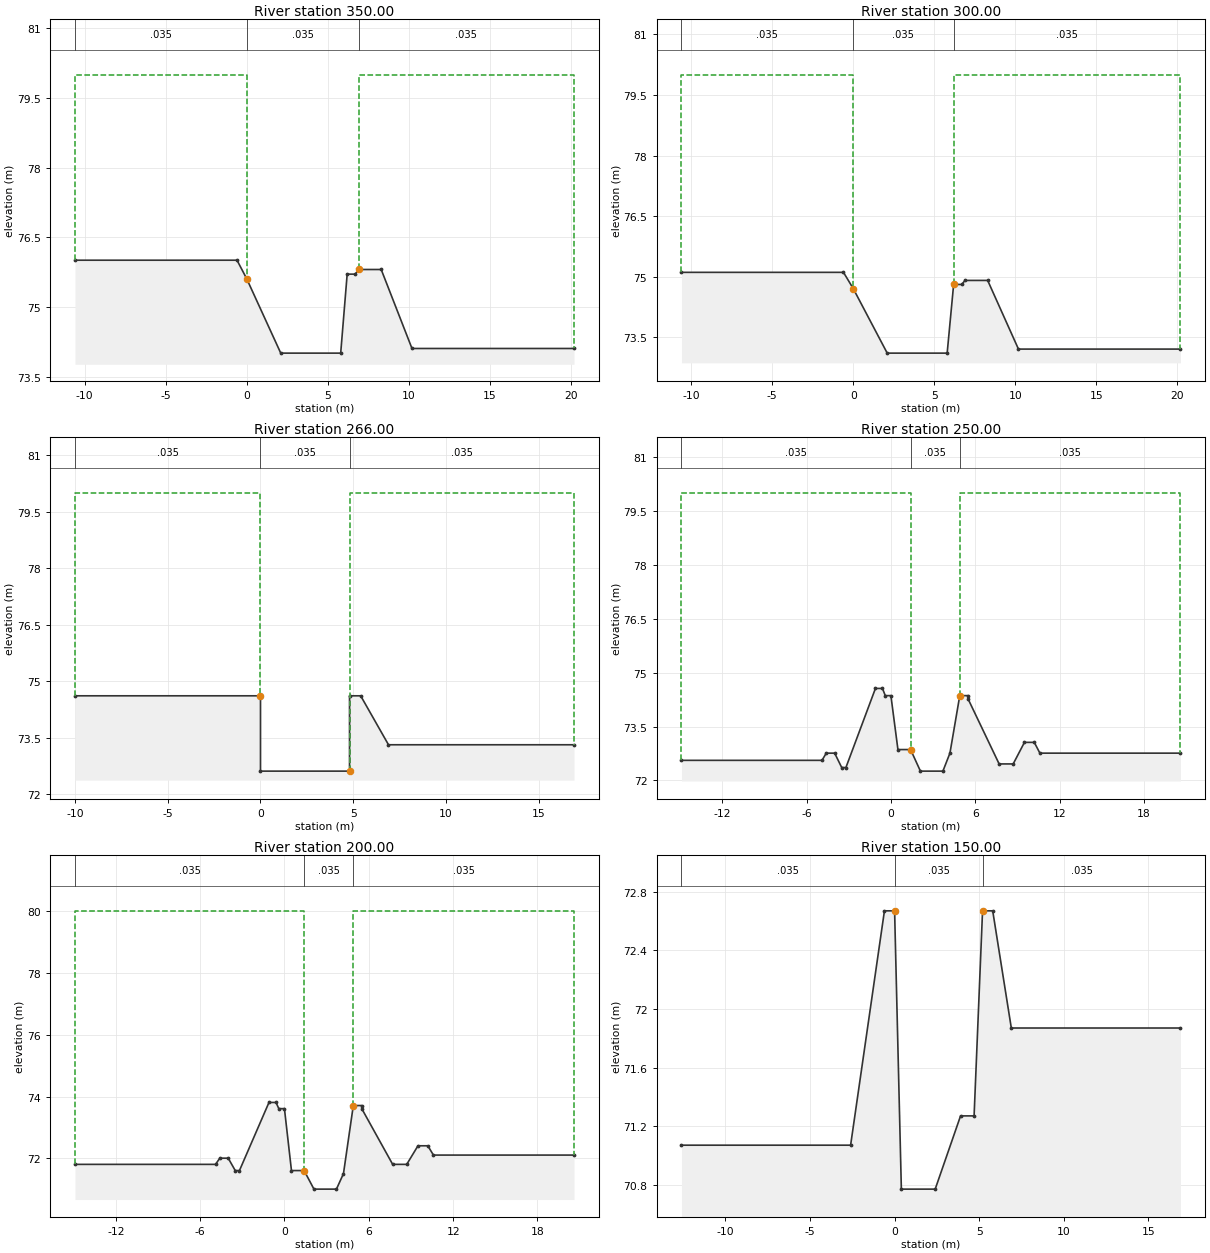
Type RM Length L Ch R = 1 ,350.00  ,50,50,50
BEGIN DESCRIPTION:
7
END DESCRIPTION:
#Sta/Elev= 11
   -10.6   76.01     -.6   76.01       0   75.61     2.1   74.01     5.8   74.01
     6.2   75.71     6.7   75.71     6.9   75.81     8.3   75.81    10.2   74.11
    20.2   74.11
#Mann= 3 , 0 , 0
   -10.6    .035       0       0    .035       0     6.9    .035       0
#XS Ineff= 2 , 0
               0      80     6.9              80
Permanent Ineff=
       F       F
#Block Obstruct= 2 , 0
                             6.9
Bank Sta=0,6.9
XS Rating Curve= 0
Exp/Cntr=.3,.1

Type RM Length L Ch R = 1 ,300.00  ,34,34,34
BEGIN DESCRIPTION:
6
END DESCRIPTION:
#Sta/Elev= 11
   -10.6   75.11     -.6   75.11       0   74.71     2.1   73.11     5.8   73.11
     6.2   74.81     6.7   74.81     6.9   74.91     8.3   74.91    10.2   73.21
    20.2   73.21
#Mann= 3 , 0 , 0
   -10.6    .035       0       0    .035       0     6.2    .035       0
#XS Ineff= 2 , 0
               0      80     6.2              80
Permanent Ineff=
       F       F
#Block Obstruct= 2 , 0
                             6.2
Bank Sta=0,6.2
XS Rating Curve= 0
Exp/Cntr=.3,.1

Type RM Length L Ch R = 1 ,266.00  ,16,16,16
BEGIN DESCRIPTION:
5.016
END DESCRIPTION:
#Sta/Elev= 8
     -10   74.61       0   74.61       0   72.61     4.8   72.61     4.8   74.61
     5.4   74.61     6.9   73.31    16.9   73.31
#Mann= 3 , 0 , 0
     -10    .035       0       0    .035       0     4.8    .035       0
#XS Ineff= 2 , 0
               0      80     4.8              80
Permanent Ineff=
       F       F
#Block Obstruct= 2 , 0
                             4.8
Bank Sta=0,4.8
XS Rating Curve= 0
Exp/Cntr=.3,.1

Type RM Length L Ch R = 1 ,250.00  ,50,50,50
BEGIN DESCRIPTION:
5
END DESCRIPTION:
#Sta/Elev= 24
   -14.9   72.56    -4.9   72.56    -4.6   72.76      -4   72.76    -3.5   72.36
    -3.2   72.36    -1.1   74.56     -.6   74.56     -.4   74.36       0   74.36
      .5   72.86     1.4   72.86     2.1   72.26     3.7   72.26     4.2   72.76
     4.9   74.36     5.5   74.36     5.5   74.26     7.7   72.46     8.7   72.46
     9.5   73.06    10.2   73.06    10.6   72.76    20.6   72.76
#Mann= 3 , 0 , 0
   -14.9    .035       0     1.4    .035       0     4.9    .035       0
#XS Ineff= 2 , 0
             1.4      80     4.9              80
Permanent Ineff=
       F       F
#Block Obstruct= 2 , 0
                             4.9
Bank Sta=1.4,4.9
XS Rating Curve= 0
Exp/Cntr=.3,.1

Type RM Length L Ch R = 1 ,200.00  ,50,50,50
BEGIN DESCRIPTION:
4
END DESCRIPTION:
#Sta/Elev= 24
   -14.9   71.81    -4.9   71.81    -4.6   72.01      -4   72.01    -3.5   71.61
    -3.2   71.61    -1.1   73.81     -.6   73.81     -.4   73.61       0   73.61
      .5   71.61     1.4   71.61     2.1   71.01     3.7   71.01     4.2   71.51
     4.9   73.71     5.5   73.71     5.5   73.61     7.7   71.81     8.7   71.81
     9.5   72.41    10.2   72.41    10.6   72.11    20.6   72.11
#Mann= 3 , 0 , 0
   -14.9    .035       0     1.4    .035       0     4.9    .035       0
#XS Ineff= 2 , 0
             1.4      80     4.9              80
Permanent Ineff=
       F       F
#Block Obstruct= 2 , 0
                             4.9
Bank Sta=1.4,4.9
XS Rating Curve= 0
Exp/Cntr=.3,.1

Type RM Length L Ch R = 1 ,150.00  ,50,50,50
BEGIN DESCRIPTION:
3
END DESCRIPTION:
#Sta/Elev= 12
   -12.6   71.07    -2.6   71.07     -.6   72.67       0   72.67      .4   70.77
     2.4   70.77     3.9   71.27     4.7   71.27     5.2   72.67     5.8   72.67
     6.9   71.87    16.9   71.87
#Mann= 3 , 0 , 0
   -12.6    .035       0       0    .035       0     5.2    .035       0
#XS Ineff= 2 , 0
               0      80     5.2              80
Permanent Ineff=
       F       F
#Block Obstruct= 2 , 0
                             5.2
Bank Sta=0,5.2
XS Rating Curve= 0
Exp/Cntr=.3,.1