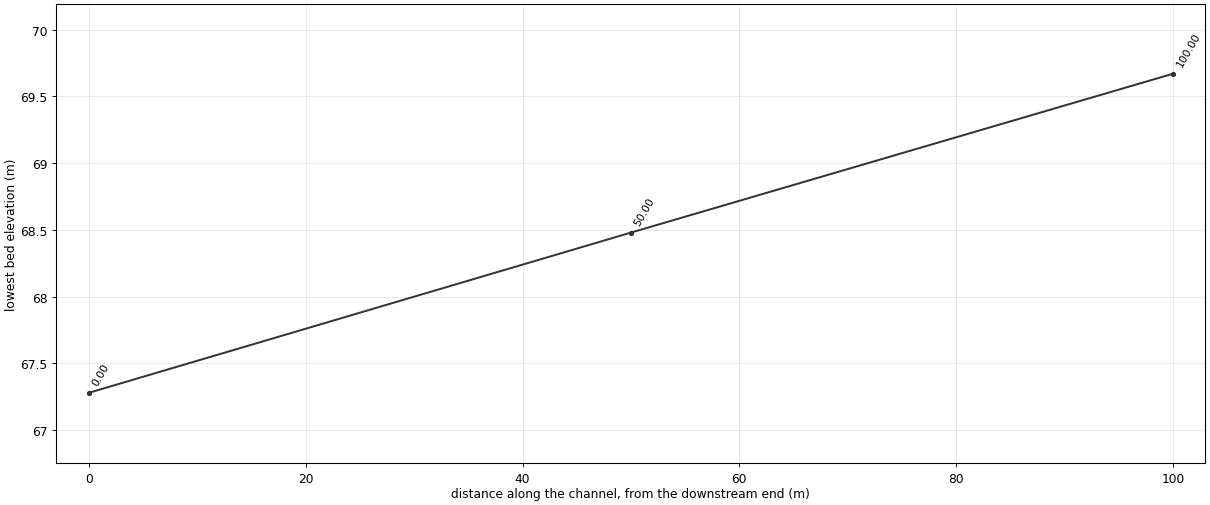
HEC-RAS study EUN.prj: EUN

--- EUN.g01 (geometry) --- (continued)

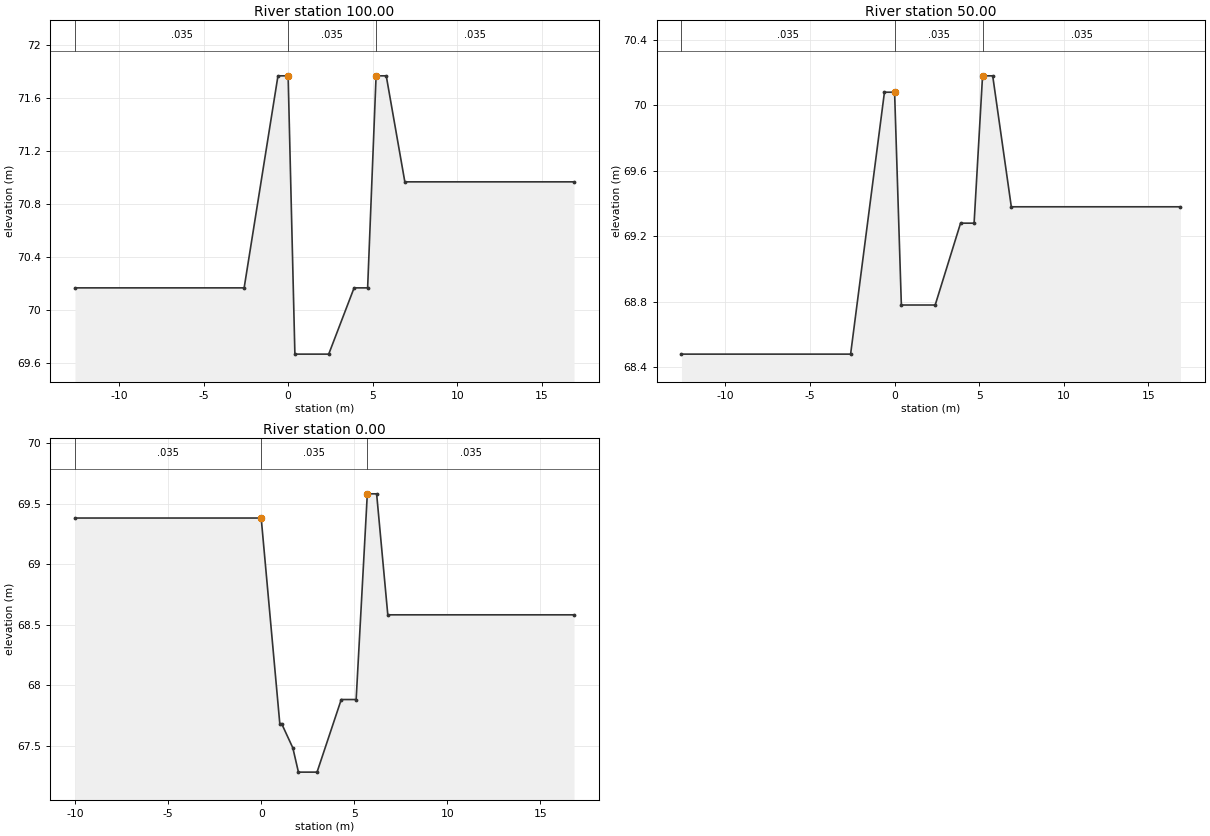
Type RM Length L Ch R = 1 ,100.00  ,50,50,50
BEGIN DESCRIPTION:
2
END DESCRIPTION:
#Sta/Elev= 12
   -12.6   70.17    -2.6   70.17     -.6   71.77       0   71.77      .4   69.67
     2.4   69.67     3.9   70.17     4.7   70.17     5.2   71.77     5.8   71.77
     6.9   70.97    16.9   70.97
#Mann= 3 , 0 , 0
   -12.6    .035       0       0    .035       0     5.2    .035       0
#XS Ineff= 2 , 0
               0      80     5.2              80
Permanent Ineff=
       F       F
#Block Obstruct= 2 , 0
                             5.2
Bank Sta=0,5.2
XS Rating Curve= 0
Exp/Cntr=.3,.1

Type RM Length L Ch R = 1 ,50.00   ,50,50,50
BEGIN DESCRIPTION:
1
END DESCRIPTION:
#Sta/Elev= 12
   -12.6   68.48    -2.6   68.48     -.6   70.08       0   70.08      .4   68.78
     2.4   68.78     3.9   69.28     4.7   69.28     5.2   70.18     5.8   70.18
     6.9   69.38    16.9   69.38
#Mann= 3 , 0 , 0
   -12.6    .035       0       0    .035       0     5.2    .035       0
#XS Ineff= 2 , 0
               0      80     5.2              80
Permanent Ineff=
       F       F
#Block Obstruct= 2 , 0
                             5.2
Bank Sta=0,5.2
XS Rating Curve= 0
Exp/Cntr=.3,.1

Type RM Length L Ch R = 1 ,0.00    ,0,0,0
BEGIN DESCRIPTION:
0
END DESCRIPTION:
#Sta/Elev= 13
     -10   69.38       0   69.38       1   67.68     1.1   67.68     1.7   67.48
       2   67.28       3   67.28     4.3   67.88     5.1   67.88     5.7   69.58
     6.2   69.58     6.8   68.58    16.8   68.58
#Mann= 3 , 0 , 0
     -10    .035       0       0    .035       0     5.7    .035       0
#XS Ineff= 2 , 0
               0      80     5.7              80
Permanent Ineff=
       F       F
#Block Obstruct= 2 , 0
                             5.7
Bank Sta=0,5.7
XS Rating Curve= 0
Exp/Cntr=.3,.1

Chan Stop Cuts=-1