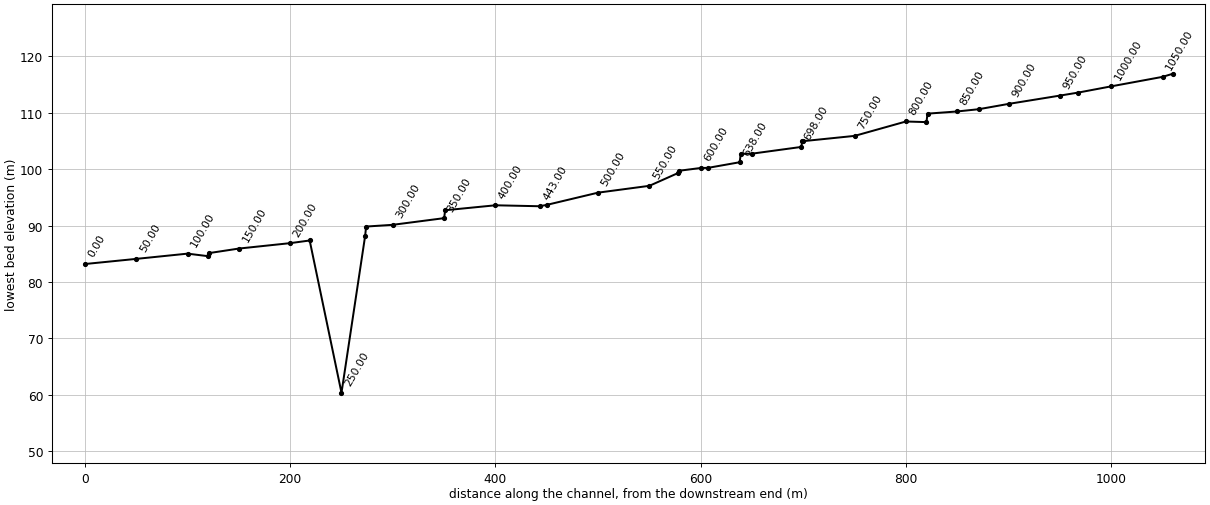
--- SAM.prj (project) ---

Proj Title=SAM
Current Plan=p01
Default Exp/Contr=.3,.1
SI Units
Geom File=g01
Flow File=f01
Plan File=p01
Y Axis Title=Elevation
X Axis Title(PF)=Main Channel Distance
X Axis Title(XS)=Station
BEGIN DESCRIPTION:
           BACK WATER COMPUTATION
      APPLICATION OF HEC-2 BY Samju Construction Engineering
      samgery-ch: 10,20,30,50,80 yr
END DESCRIPTION:
DSS Export Rating Curves= 0
DSS Export Rating Curve Sorted= 0
DSS Export Volume Flow Curves= 0
DXF OffsetX= 0
DXF OffsetY= 0
DXF ScaleX= 1
DXF ScaleY= 10

--- SAM.p01 (plan) ---

Plan Title=Imported Plan 01
Version=Version 3.0.1  Mar 2001
Short Identifier=Imported Pla
Geom File=g01
Flow File=f01
Subcritical Flow
K Sum by GR= 0
Std Step Tol= 0.003
Critical Tol= 0.003
Num of Std Step Trials= 20
Max Error Tol= 0.1
Flow Tol Ratio= 0.001
Split Flow NTrial= 30
Split Flow Tol= 0.02
Split Flow Ratio= 0.02
Log Output Level= 0
Friction Slope Method= 1
Unsteady Friction Slope Method= 2
Parabolic Critical Depth
Global Vel Dist= 0 , 0 , 0
Global Log Level= 0
CheckData=True
Encroach Param=-1 ,0,0, 0
Computation Interval=1HOUR
Output Interval=1HOUR
Run HTab= 0
Run UNet= 0
Run PostProcess= 0
UNET Theta= 1
UNET ZTol= 0.02
UNET ZSATol= 0.1
UNET MxIter= 20
UNET MaxInSteps= 20
UNET DtIC= 0
UNET DtMin= 0
UNET MaxCRTS= 20
UNET WFStab= 2
UNET SFStab= 1
UNET WFX= 1
UNET SFX= 1
UNET Convert EG Bridges=-1
UNET Use Existing IB Tables=-1
Instantaneous Interval=1HOUR
Write IC File= 0
Write Velocity= 0
Write Detailed= 0

--- SAM.f01 (steady flow) ---

Flow Title=Imported Flow 01
Version=Version 3.0.1  Mar 2001
Number of Profiles= 5
Profile Names=10YR,20YR,30YR,50YR,80YR
River Rch & RM=RIVER-1,Reach-1         ,1060.00
   10.97    12.1   12.75   13.58   14.35
Boundary for River Rch & Prof#=RIVER-1,Reach-1         , 1
Up Type= 0
Dn Type= 3
Dn Slope=.034
Boundary for River Rch & Prof#=RIVER-1,Reach-1         , 2
Up Type= 0
Dn Type= 3
Dn Slope=.034
Boundary for River Rch & Prof#=RIVER-1,Reach-1         , 3
Up Type= 0
Dn Type= 3
Dn Slope=.034
Boundary for River Rch & Prof#=RIVER-1,Reach-1         , 4
Up Type= 0
Dn Type= 3
Dn Slope=.034
Boundary for River Rch & Prof#=RIVER-1,Reach-1         , 5
Up Type= 0
Dn Type= 3
Dn Slope=.034
DSS Import GetInterval= 0
DSS Import GetPeak= 0
DSS Import FillOption= 0

--- SAM.g01 (geometry) ---

Geom Title=Imported Geom 01
Version=Version 3.0.1  Mar 2001

River Reach=RIVER-1         ,Reach-1
Reach XY= 2
              .5             .95              .5             .05

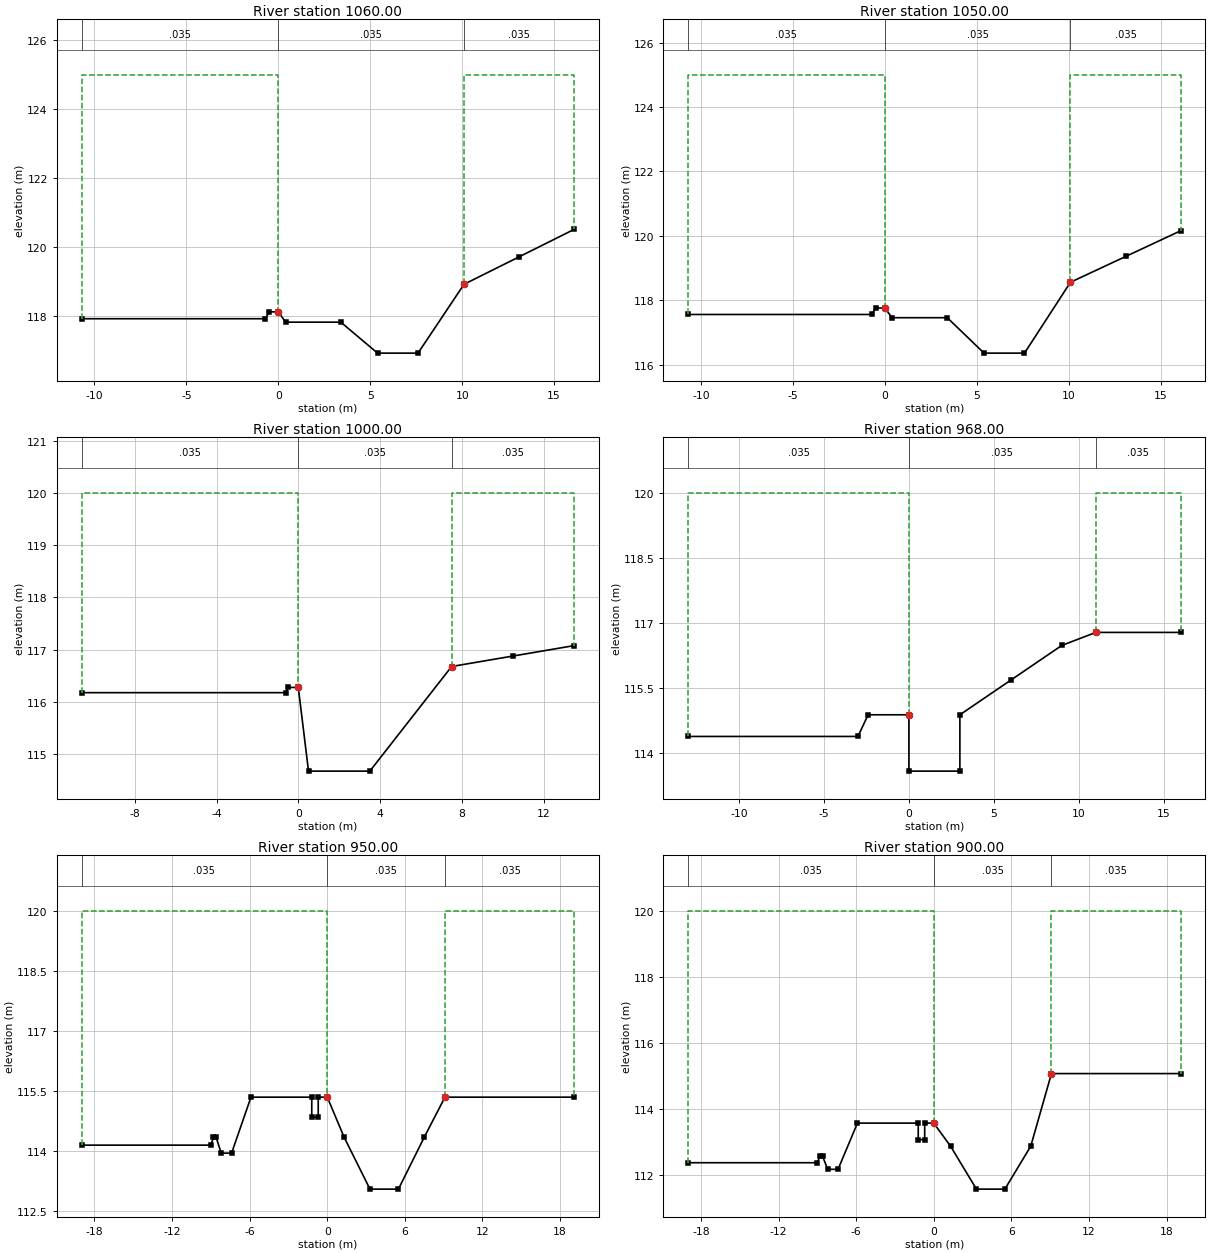
Type RM Length L Ch R = 1 ,1060.00 ,10,10,10
BEGIN DESCRIPTION:
21.01
END DESCRIPTION:
#Sta/Elev= 11
   -10.7  117.91     -.7  117.91     -.5  118.11       0  118.11      .4  117.81
     3.4  117.81     5.4  116.91     7.6  116.91    10.1  118.91    13.1  119.71
    16.1  120.51
#Mann= 3 , 0 , 0
   -10.7    .035       0       0    .035       0    10.1    .035       0
#XS Ineff= 2 , 0
               0     125    10.1             125
Permanent Ineff=
       F       F
#Block Obstruct= 2 , 0
                            10.1
Bank Sta=0,10.1
XS Rating Curve= 0
Exp/Cntr=.3,.1

Type RM Length L Ch R = 1 ,1050.00 ,50,50,50
BEGIN DESCRIPTION:
21
END DESCRIPTION:
#Sta/Elev= 11
   -10.7  117.56     -.7  117.56     -.5  117.76       0  117.76      .4  117.46
     3.4  117.46     5.4  116.36     7.6  116.36    10.1  118.56    13.1  119.36
    16.1  120.16
#Mann= 3 , 0 , 0
   -10.7    .035       0       0    .035       0    10.1    .035       0
#XS Ineff= 2 , 0
               0     125    10.1             125
Permanent Ineff=
       F       F
#Block Obstruct= 2 , 0
                            10.1
Bank Sta=0,10.1
XS Rating Curve= 0
Exp/Cntr=.3,.1

Type RM Length L Ch R = 1 ,1000.00 ,32,32,32
BEGIN DESCRIPTION:
20
END DESCRIPTION:
#Sta/Elev= 9
   -10.6  116.18     -.6  116.18     -.5  116.28       0  116.28      .5  114.68
     3.5  114.68     7.5  116.68    10.5  116.88    13.5  117.08
#Mann= 3 , 0 , 0
   -10.6    .035       0       0    .035       0     7.5    .035       0
#XS Ineff= 2 , 0
               0     120     7.5             120
Permanent Ineff=
       F       F
#Block Obstruct= 2 , 0
                             7.5
Bank Sta=0,7.5
XS Rating Curve= 0
Exp/Cntr=.3,.1

Type RM Length L Ch R = 1 ,968.00  ,18,18,18
BEGIN DESCRIPTION:
19.018
END DESCRIPTION:
#Sta/Elev= 11
     -13  114.38      -3  114.38    -2.4  114.88       0  114.88       0  113.58
       3  113.58       3  114.88       6  115.68       9  116.48      11  116.78
      16  116.78
#Mann= 3 , 0 , 0
     -13    .035       0       0    .035       0      11    .035       0
#XS Ineff= 2 , 0
               0     120      11             120
Permanent Ineff=
       F       F
#Block Obstruct= 2 , 0
                              11
Bank Sta=0,11
XS Rating Curve= 0
Exp/Cntr=.3,.1

Type RM Length L Ch R = 1 ,950.00  ,50,50,50
BEGIN DESCRIPTION:
19
END DESCRIPTION:
#Sta/Elev= 18
     -19  114.14      -9  114.14    -8.8  114.34    -8.6  114.34    -8.2  113.94
    -7.4  113.94    -5.9  115.34    -1.2  115.34    -1.2  114.84     -.7  114.84
     -.7  115.34       0  115.34     1.3  114.34     3.3  113.04     5.5  113.04
     7.5  114.34     9.1  115.34    19.1  115.34
#Mann= 3 , 0 , 0
     -19    .035       0       0    .035       0     9.1    .035       0
#XS Ineff= 2 , 0
               0     120     9.1             120
Permanent Ineff=
       F       F
#Block Obstruct= 2 , 0
                             9.1
Bank Sta=0,9.1
XS Rating Curve= 0
Exp/Cntr=.3,.1

Type RM Length L Ch R = 1 ,900.00  ,29,29,29
BEGIN DESCRIPTION:
18
END DESCRIPTION:
#Sta/Elev= 18
     -19  112.37      -9  112.37    -8.8  112.57    -8.6  112.57    -8.2  112.17
    -7.4  112.17    -5.9  113.57    -1.2  113.57    -1.2  113.07     -.7  113.07
     -.7  113.57       0  113.57     1.3  112.87     3.3  111.57     5.5  111.57
     7.5  112.87     9.1  115.07    19.1  115.07
#Mann= 3 , 0 , 0
     -19    .035       0       0    .035       0     9.1    .035       0
#XS Ineff= 2 , 0
               0     120     9.1             120
Permanent Ineff=
       F       F
#Block Obstruct= 2 , 0
                             9.1
Bank Sta=0,9.1
XS Rating Curve= 0
Exp/Cntr=.3,.1

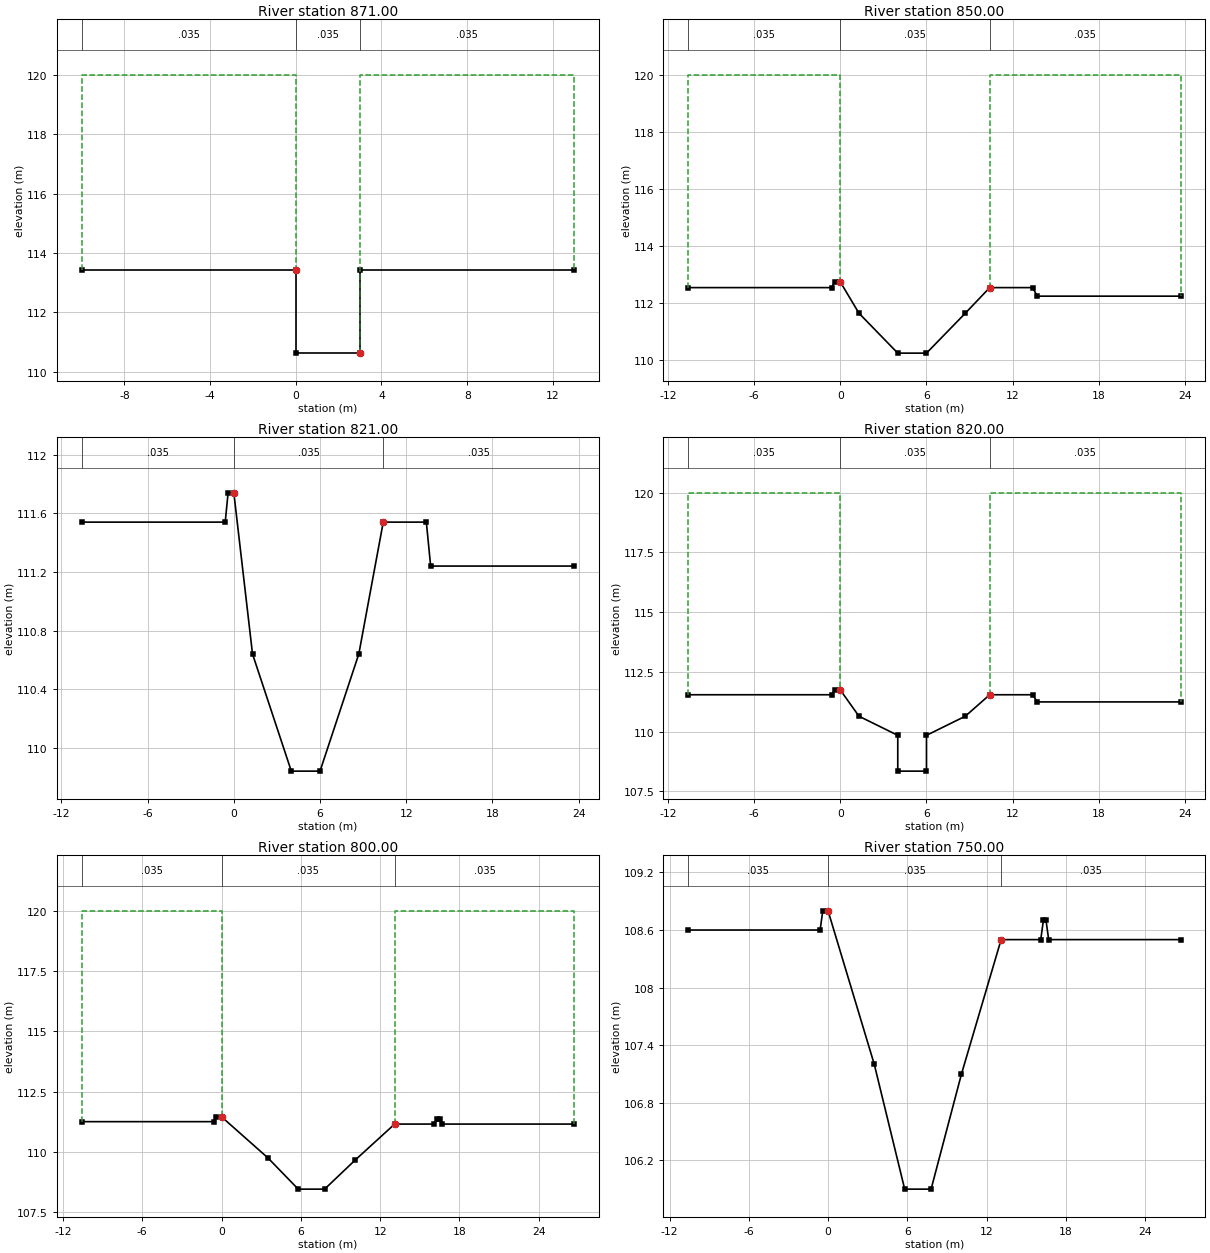
Type RM Length L Ch R = 1 ,871.00  ,21,21,21
BEGIN DESCRIPTION:
17.021
END DESCRIPTION:
#Sta/Elev= 6
     -10  113.43       0  113.43       0  110.63       3  110.63       3  113.43
      13  113.43
#Mann= 3 , 0 , 0
     -10    .035       0       0    .035       0       3    .035       0
#XS Ineff= 2 , 0
               0     120       3             120
Permanent Ineff=
       F       F
#Block Obstruct= 2 , 0
                               3
Bank Sta=0,3
XS Rating Curve= 0
Exp/Cntr=.3,.1

Type RM Length L Ch R = 1 ,850.00  ,29,29,29
BEGIN DESCRIPTION:
17
END DESCRIPTION:
#Sta/Elev= 12
   -10.6  112.53     -.6  112.53     -.4  112.73       0  112.73     1.3  111.63
       4  110.23       6  110.23     8.7  111.63    10.4  112.53    13.4  112.53
    13.7  112.23    23.7  112.23
#Mann= 3 , 0 , 0
   -10.6    .035       0       0    .035       0    10.4    .035       0
#XS Ineff= 2 , 0
               0     120    10.4             120
Permanent Ineff=
       F       F
#Block Obstruct= 2 , 0
                            10.4
Bank Sta=0,10.4
XS Rating Curve= 0
Exp/Cntr=.3,.1

Type RM Length L Ch R = 1 ,821.00  ,1,1,1
BEGIN DESCRIPTION:
16.021
END DESCRIPTION:
#Sta/Elev= 12
   -10.6  111.54     -.6  111.54     -.4  111.74       0  111.74     1.3  110.64
       4  109.84       6  109.84     8.7  110.64    10.4  111.54    13.4  111.54
    13.7  111.24    23.7  111.24
#Mann= 3 , 0 , 0
   -10.6    .035       0       0    .035       0    10.4    .035       0
#XS Ineff= 2 , 0
               0     120    10.4             120
Permanent Ineff=
       F       F
#Block Obstruct= 2 , 0
                            10.4
Bank Sta=0,10.4
XS Rating Curve= 0
Exp/Cntr=.3,.1

Type RM Length L Ch R = 1 ,820.00  ,20,20,20
BEGIN DESCRIPTION:
16.02
END DESCRIPTION:
#Sta/Elev= 14
   -10.6  111.54     -.6  111.54     -.4  111.74       0  111.74     1.3  110.64
       4  109.84       4  108.34       6  108.34       6  109.84     8.7  110.64
    10.4  111.54    13.4  111.54    13.7  111.24    23.7  111.24
#Mann= 3 , 0 , 0
   -10.6    .035       0       0    .035       0    10.4    .035       0
#XS Ineff= 2 , 0
               0     120    10.4             120
Permanent Ineff=
       F       F
#Block Obstruct= 2 , 0
                            10.4
Bank Sta=0,10.4
XS Rating Curve= 0
Exp/Cntr=.3,.1

Type RM Length L Ch R = 1 ,800.00  ,50,50,50
BEGIN DESCRIPTION:
16
END DESCRIPTION:
#Sta/Elev= 14
   -10.6  111.25     -.6  111.25     -.4  111.45       0  111.45     3.5  109.75
     5.8  108.45     7.8  108.45    10.1  109.65    13.1  111.15    16.1  111.15
    16.3  111.35    16.5  111.35    16.7  111.15    26.7  111.15
#Mann= 3 , 0 , 0
   -10.6    .035       0       0    .035       0    13.1    .035       0
#XS Ineff= 2 , 0
               0     120    13.1             120
Permanent Ineff=
       F       F
#Block Obstruct= 2 , 0
                            13.1
Bank Sta=0,13.1
XS Rating Curve= 0
Exp/Cntr=.3,.1

Type RM Length L Ch R = 1 ,750.00  ,50,50,50
BEGIN DESCRIPTION:
15
END DESCRIPTION:
#Sta/Elev= 14
   -10.6   108.6     -.6   108.6     -.4   108.8       0   108.8     3.5   107.2
     5.8   105.9     7.8   105.9    10.1   107.1    13.1   108.5    16.1   108.5
    16.3   108.7    16.5   108.7    16.7   108.5    26.7   108.5
#Mann= 3 , 0 , 0
   -10.6    .035       0       0    .035       0    13.1    .035       0
#XS Ineff= 2 , 0
               0     120    13.1             120
Permanent Ineff=
       F       F
#Block Obstruct= 2 , 0
                            13.1
Bank Sta=0,13.1
XS Rating Curve= 0
Exp/Cntr=.3,.1

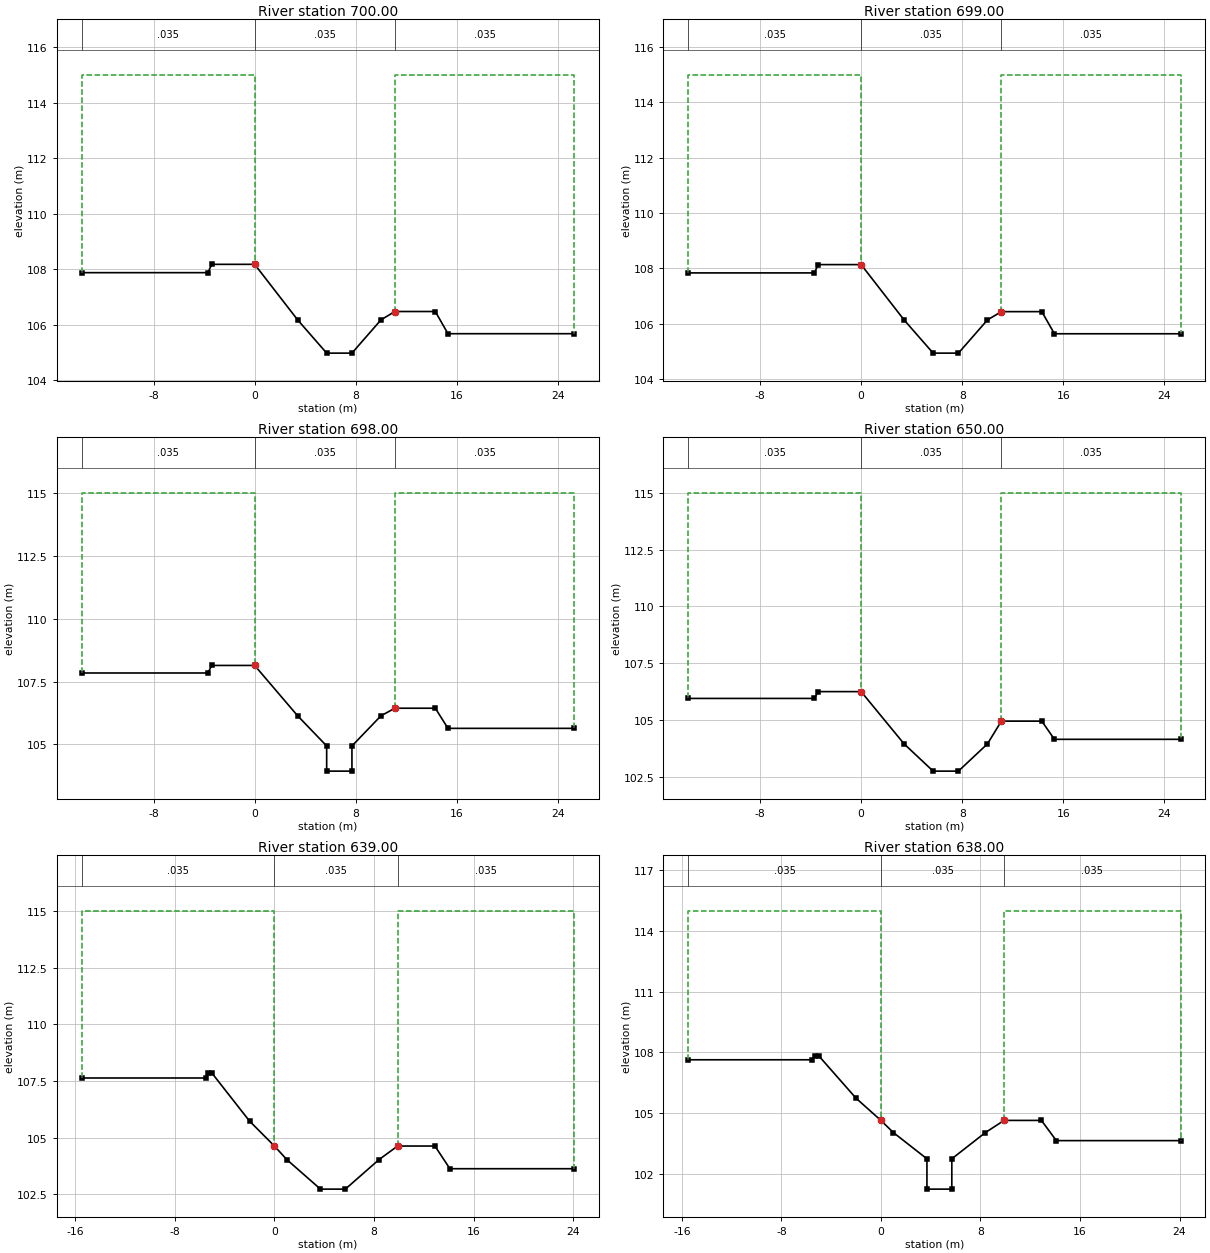
Type RM Length L Ch R = 1 ,700.00  ,1,1,1
BEGIN DESCRIPTION:
14
END DESCRIPTION:
#Sta/Elev= 12
   -13.7  107.87    -3.7  107.87    -3.4  108.17       0  108.17     3.4  106.17
     5.7  104.97     7.7  104.97      10  106.17    11.1  106.47    14.3  106.47
    15.3  105.67    25.3  105.67
#Mann= 3 , 0 , 0
   -13.7    .035       0       0    .035       0    11.1    .035       0
#XS Ineff= 2 , 0
               0     115    11.1             115
Permanent Ineff=
       F       F
#Block Obstruct= 2 , 0
                            11.1
Bank Sta=0,11.1
XS Rating Curve= 0
Exp/Cntr=.3,.1

Type RM Length L Ch R = 1 ,699.00  ,1,1,1
BEGIN DESCRIPTION:
13.049
END DESCRIPTION:
#Sta/Elev= 12
   -13.7  107.84    -3.7  107.84    -3.4  108.14       0  108.14     3.4  106.14
     5.7  104.94     7.7  104.94      10  106.14    11.1  106.44    14.3  106.44
    15.3  105.64    25.3  105.64
#Mann= 3 , 0 , 0
   -13.7    .035       0       0    .035       0    11.1    .035       0
#XS Ineff= 2 , 0
               0     115    11.1             115
Permanent Ineff=
       F       F
#Block Obstruct= 2 , 0
                            11.1
Bank Sta=0,11.1
XS Rating Curve= 0
Exp/Cntr=.3,.1

Type RM Length L Ch R = 1 ,698.00  ,48,48,48
BEGIN DESCRIPTION:
13.048
END DESCRIPTION:
#Sta/Elev= 14
   -13.7  107.84    -3.7  107.84    -3.4  108.14       0  108.14     3.4  106.14
     5.7  104.94     5.7  103.94     7.7  103.94     7.7  104.94      10  106.14
    11.1  106.44    14.3  106.44    15.3  105.64    25.3  105.64
#Mann= 3 , 0 , 0
   -13.7    .035       0       0    .035       0    11.1    .035       0
#XS Ineff= 2 , 0
               0     115    11.1             115
Permanent Ineff=
       F       F
#Block Obstruct= 2 , 0
                            11.1
Bank Sta=0,11.1
XS Rating Curve= 0
Exp/Cntr=.3,.1

Type RM Length L Ch R = 1 ,650.00  ,11,11,11
BEGIN DESCRIPTION:
13
END DESCRIPTION:
#Sta/Elev= 12
   -13.7  105.95    -3.7  105.95    -3.4  106.25       0  106.25     3.4  103.95
     5.7  102.75     7.7  102.75      10  103.95    11.1  104.95    14.3  104.95
    15.3  104.15    25.3  104.15
#Mann= 3 , 0 , 0
   -13.7    .035       0       0    .035       0    11.1    .035       0
#XS Ineff= 2 , 0
               0     115    11.1             115
Permanent Ineff=
       F       F
#Block Obstruct= 2 , 0
                            11.1
Bank Sta=0,11.1
XS Rating Curve= 0
Exp/Cntr=.3,.1

Type RM Length L Ch R = 1 ,639.00  ,1,1,1
BEGIN DESCRIPTION:
12.039
END DESCRIPTION:
#Sta/Elev= 14
   -15.5  107.63    -5.5  107.63    -5.3  107.83      -5  107.83      -2  105.73
       0  104.63       1  104.03     3.7  102.73     5.7  102.73     8.4  104.03
     9.9  104.63    12.9  104.63    14.1  103.63    24.1  103.63
#Mann= 3 , 0 , 0
   -15.5    .035       0       0    .035       0     9.9    .035       0
#XS Ineff= 2 , 0
               0     115     9.9             115
Permanent Ineff=
       F       F
#Block Obstruct= 2 , 0
                             9.9
Bank Sta=0,9.9
XS Rating Curve= 0
Exp/Cntr=.3,.1

Type RM Length L Ch R = 1 ,638.00  ,31,31,31
BEGIN DESCRIPTION:
12.038
END DESCRIPTION:
#Sta/Elev= 16
   -15.5  107.63    -5.5  107.63    -5.3  107.83      -5  107.83      -2  105.73
       0  104.63       1  104.03     3.7  102.73     3.7  101.23     5.7  101.23
     5.7  102.73     8.4  104.03     9.9  104.63    12.9  104.63    14.1  103.63
    24.1  103.63
#Mann= 3 , 0 , 0
   -15.5    .035       0       0    .035       0     9.9    .035       0
#XS Ineff= 2 , 0
               0     115     9.9             115
Permanent Ineff=
       F       F
#Block Obstruct= 2 , 0
                             9.9
Bank Sta=0,9.9
XS Rating Curve= 0
Exp/Cntr=.3,.1

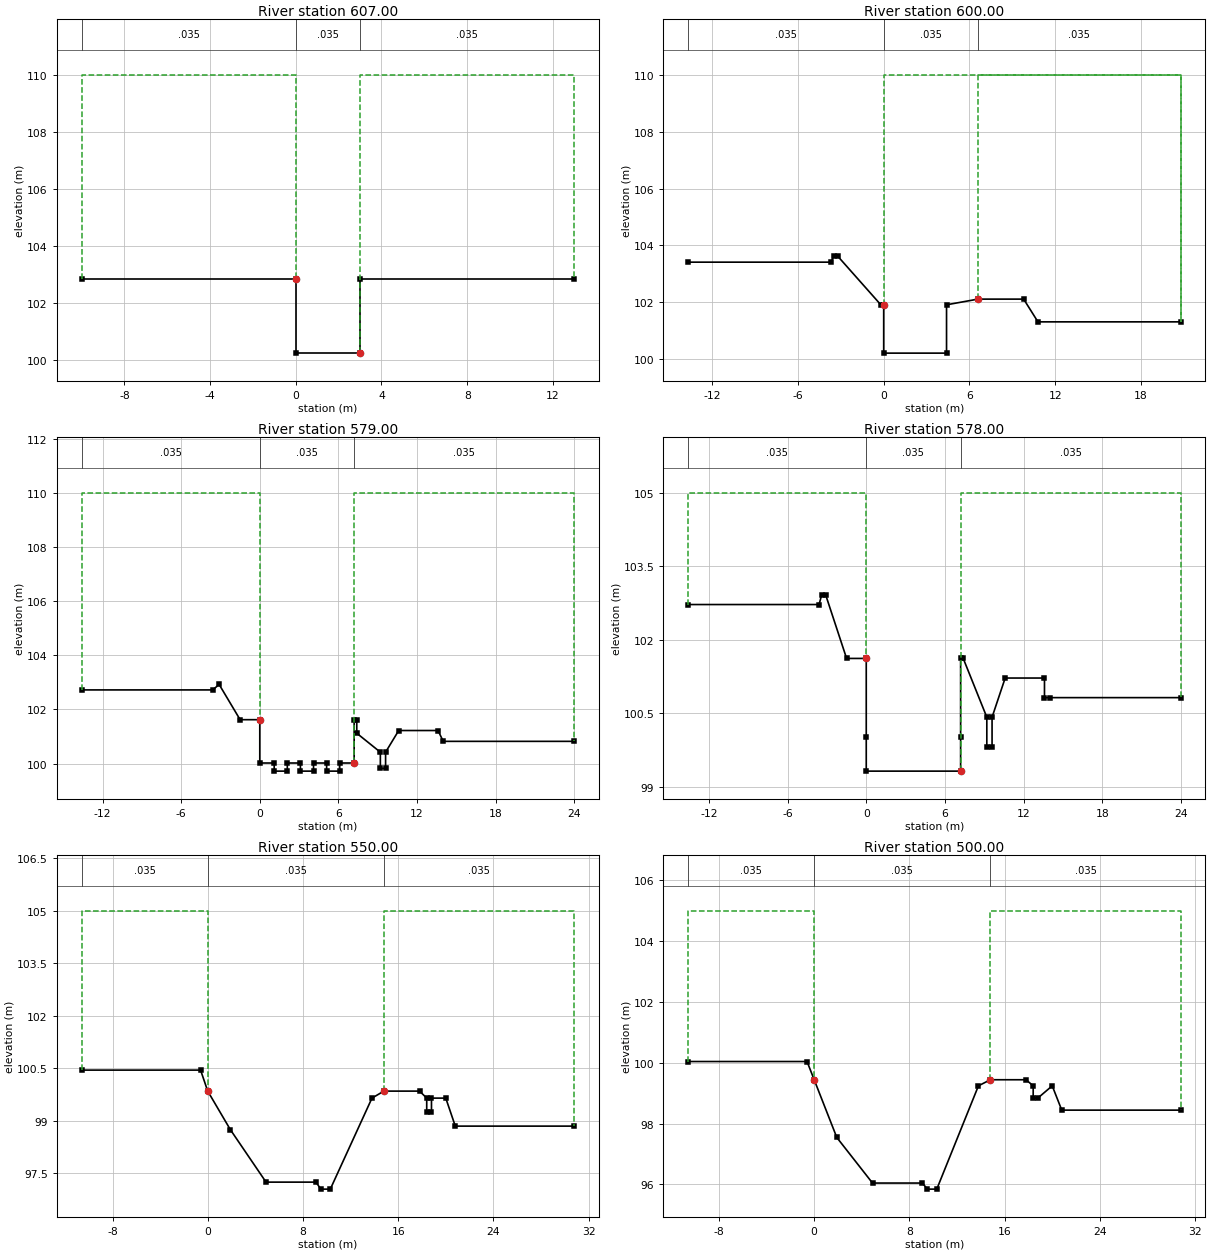
Type RM Length L Ch R = 1 ,607.00  ,7,7,7
BEGIN DESCRIPTION:
12.007
END DESCRIPTION:
#Sta/Elev= 6
     -10  102.83       0  102.83       0  100.23       3  100.23       3  102.83
      13  102.83
#Mann= 3 , 0 , 0
     -10    .035       0       0    .035       0       3    .035       0
#XS Ineff= 2 , 0
               0     110       3             110
Permanent Ineff=
       F       F
#Block Obstruct= 2 , 0
                               3
Bank Sta=0,3
XS Rating Curve= 0
Exp/Cntr=.3,.1

Type RM Length L Ch R = 1 ,600.00  ,21,21,21
BEGIN DESCRIPTION:
12
END DESCRIPTION:
#Sta/Elev= 13
   -13.7  103.41    -3.7  103.41    -3.5  103.61    -3.2  103.61     -.2  101.91
       0  101.91       0  100.21     4.4  100.21     4.4  101.91     6.6  102.11
     9.8  102.11    10.8  101.31    20.8  101.31
#Mann= 3 , 0 , 0
   -13.7    .035       0       0    .035       0     6.6    .035       0
#XS Ineff= 2 , 0
       0       0     110     6.6       0     110
Permanent Ineff=
       F       F
#Block Obstruct= 2 , 0
                             6.6
Bank Sta=0,6.6
XS Rating Curve= 0
Exp/Cntr=.3,.1

Type RM Length L Ch R = 1 ,579.00  ,1,1,1
BEGIN DESCRIPTION:
11.029
END DESCRIPTION:
#Sta/Elev= 30
   -13.6  102.72    -3.6  102.72    -3.1  102.92    -1.5  101.62       0  101.62
       0  100.02     1.1  100.02     1.1   99.72     2.1   99.72     2.1  100.02
     3.1  100.02     3.1   99.72     4.1   99.72     4.1  100.02     5.1  100.02
     5.1   99.72     6.1   99.72     6.1  100.02     7.2  100.02     7.2  101.62
     7.4  101.62     7.4  101.12     9.2  100.42     9.2   99.82     9.6   99.82
     9.6  100.42    10.6  101.22    13.6  101.22      14  100.82      24  100.82
#Mann= 3 , 0 , 0
   -13.6    .035       0       0    .035       0     7.2    .035       0
#XS Ineff= 2 , 0
               0     110     7.2             110
Permanent Ineff=
       F       F
#Block Obstruct= 2 , 0
                             7.2
Bank Sta=0,7.2
XS Rating Curve= 0
Exp/Cntr=.3,.1

Type RM Length L Ch R = 1 ,578.00  ,28,28,28
BEGIN DESCRIPTION:
11.028
END DESCRIPTION:
#Sta/Elev= 21
   -13.6  102.72    -3.6  102.72    -3.4  102.92    -3.1  102.92    -1.5  101.62
       0  101.62       0  100.02       0   99.32     7.2   99.32     7.2  100.02
     7.2  101.62     7.4  101.62     9.2  100.42     9.2   99.82     9.6   99.82
     9.6  100.42    10.6  101.22    13.6  101.22    13.6  100.82      14  100.82
      24  100.82
#Mann= 3 , 0 , 0
   -13.6    .035       0       0    .035       0     7.2    .035       0
#XS Ineff= 2 , 0
               0     105     7.2             105
Permanent Ineff=
       F       F
#Block Obstruct= 2 , 0
                             7.2
Bank Sta=0,7.2
XS Rating Curve= 0
Exp/Cntr=.3,.1

Type RM Length L Ch R = 1 ,550.00  ,50,50,50
BEGIN DESCRIPTION:
11
END DESCRIPTION:
#Sta/Elev= 18
   -10.6  100.45     -.6  100.45       0   99.85     1.9   98.75     4.9   97.25
     9.1   97.25     9.5   97.05    10.3   97.05    13.8   99.65    14.8   99.85
    17.8   99.85    18.4   99.65    18.4   99.25    18.8   99.25    18.8   99.65
      20   99.65    20.8   98.85    30.8   98.85
#Mann= 3 , 0 , 0
   -10.6    .035       0       0    .035       0    14.8    .035       0
#XS Ineff= 2 , 0
               0     105    14.8             105
Permanent Ineff=
       F       F
#Block Obstruct= 2 , 0
                            14.8
Bank Sta=0,14.8
XS Rating Curve= 0
Exp/Cntr=.3,.1

Type RM Length L Ch R = 1 ,500.00  ,50,50,50
BEGIN DESCRIPTION:
10
END DESCRIPTION:
#Sta/Elev= 17
   -10.6  100.04     -.6  100.04       0   99.44     1.9   97.54     4.9   96.04
     9.1   96.04     9.5   95.84    10.3   95.84    13.8   99.24    14.8   99.44
    17.8   99.44    18.4   99.24    18.4   98.84    18.8   98.84      20   99.24
    20.8   98.44    30.8   98.44
#Mann= 3 , 0 , 0
   -10.6    .035       0       0    .035       0    14.8    .035       0
#XS Ineff= 2 , 0
               0     105    14.8             105
Permanent Ineff=
       F       F
#Block Obstruct= 2 , 0
                            14.8
Bank Sta=0,14.8
XS Rating Curve= 0
Exp/Cntr=.3,.1

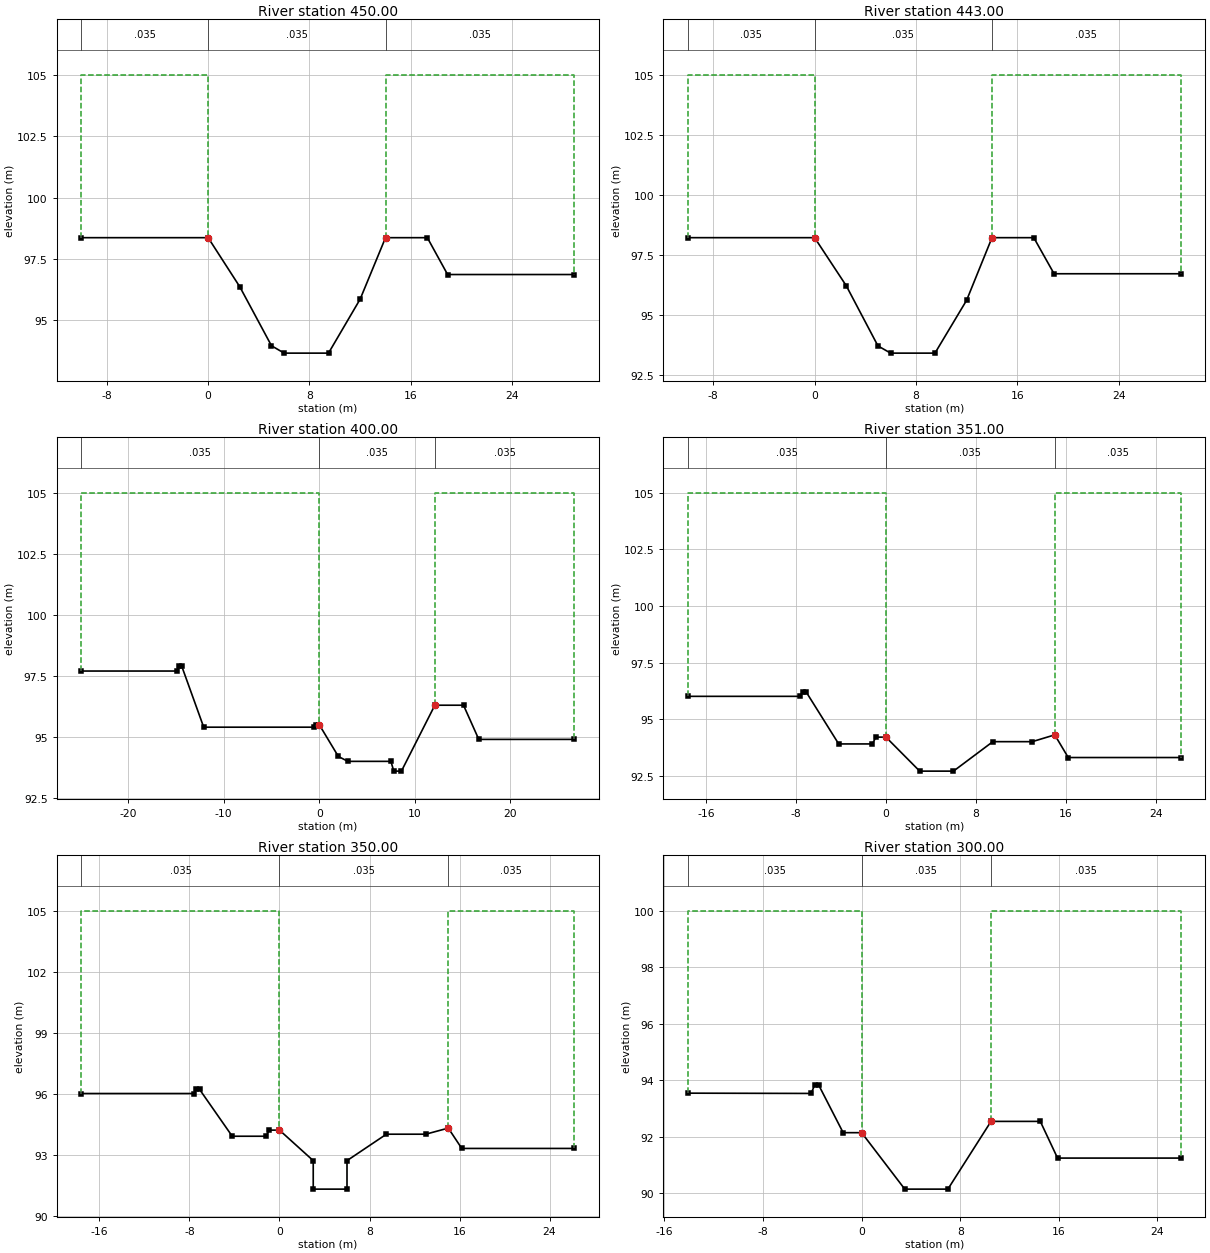
Type RM Length L Ch R = 1 ,450.00  ,7,7,7
BEGIN DESCRIPTION:
9
END DESCRIPTION:
#Sta/Elev= 11
     -10   98.37       0   98.37     2.5   96.37       5   93.97       6   93.67
     9.5   93.67      12   95.87      14   98.37    17.3   98.37    18.9   96.87
    28.9   96.87
#Mann= 3 , 0 , 0
     -10    .035       0       0    .035       0      14    .035       0
#XS Ineff= 2 , 0
               0     105      14             105
Permanent Ineff=
       F       F
#Block Obstruct= 2 , 0
                              14
Bank Sta=0,14
XS Rating Curve= 0
Exp/Cntr=.3,.1

Type RM Length L Ch R = 1 ,443.00  ,43,43,43
BEGIN DESCRIPTION:
8.043
END DESCRIPTION:
#Sta/Elev= 11
     -10   98.23       0   98.23     2.5   96.23       5   93.73       6   93.43
     9.5   93.43      12   95.63      14   98.23    17.3   98.23    18.9   96.73
    28.9   96.73
#Mann= 3 , 0 , 0
     -10    .035       0       0    .035       0      14    .035       0
#XS Ineff= 2 , 0
               0     105      14             105
Permanent Ineff=
       F       F
#Block Obstruct= 2 , 0
                              14
Bank Sta=0,14
XS Rating Curve= 0
Exp/Cntr=.3,.1

Type RM Length L Ch R = 1 ,400.00  ,49,49,49
BEGIN DESCRIPTION:
8
END DESCRIPTION:
#Sta/Elev= 17
   -24.9    97.7   -14.9    97.7   -14.7    97.9   -14.4    97.9   -12.1    95.4
     -.6    95.4     -.3    95.5       0    95.5       2    94.2       3      94
     7.5      94     7.8    93.6     8.6    93.6    12.1    96.3    15.1    96.3
    16.7    94.9    26.7    94.9
#Mann= 3 , 0 , 0
   -24.9    .035       0       0    .035       0    12.1    .035       0
#XS Ineff= 2 , 0
               0     105    12.1             105
Permanent Ineff=
       F       F
#Block Obstruct= 2 , 0
                            12.1
Bank Sta=0,12.1
XS Rating Curve= 0
Exp/Cntr=.3,.1

Type RM Length L Ch R = 1 ,351.00  ,1,1,1
BEGIN DESCRIPTION:
7.001
END DESCRIPTION:
#Sta/Elev= 15
   -17.6   96.02    -7.6   96.02    -7.4   96.22    -7.1   96.22    -4.2   93.92
    -1.2   93.92     -.9   94.22       0   94.22       3   92.72       6   92.72
     9.5   94.02      13   94.02      15   94.32    16.2   93.32    26.2   93.32
#Mann= 3 , 0 , 0
   -17.6    .035       0       0    .035       0      15    .035       0
#XS Ineff= 2 , 0
               0     105      15             105
Permanent Ineff=
       F       F
#Block Obstruct= 2 , 0
                              15
Bank Sta=0,15
XS Rating Curve= 0
Exp/Cntr=.3,.1

Type RM Length L Ch R = 1 ,350.00  ,50,50,50
BEGIN DESCRIPTION:
7
END DESCRIPTION:
#Sta/Elev= 17
   -17.6   96.02    -7.6   96.02    -7.4   96.22    -7.1   96.22    -4.2   93.92
    -1.2   93.92     -.9   94.22       0   94.22       3   92.72       3   91.32
       6   91.32       6   92.72     9.5   94.02      13   94.02      15   94.32
    16.2   93.32    26.2   93.32
#Mann= 3 , 0 , 0
   -17.6    .035       0       0    .035       0      15    .035       0
#XS Ineff= 2 , 0
               0     105      15             105
Permanent Ineff=
       F       F
#Block Obstruct= 2 , 0
                              15
Bank Sta=0,15
XS Rating Curve= 0
Exp/Cntr=.3,.1

Type RM Length L Ch R = 1 ,300.00  ,26,26,26
BEGIN DESCRIPTION:
6
END DESCRIPTION:
#Sta/Elev= 12
   -14.1   93.54    -4.1   93.53    -3.8   93.84    -3.5   93.84    -1.5   92.14
       0   92.14     3.5   90.14       7   90.14    10.5   92.54    14.5   92.54
    15.9   91.24    25.9   91.24
#Mann= 3 , 0 , 0
   -14.1    .035       0       0    .035       0    10.5    .035       0
#XS Ineff= 2 , 0
               0     100    10.5             100
Permanent Ineff=
       F       F
#Block Obstruct= 2 , 0
                            10.5
Bank Sta=0,10.5
XS Rating Curve= 0
Exp/Cntr=.3,.1

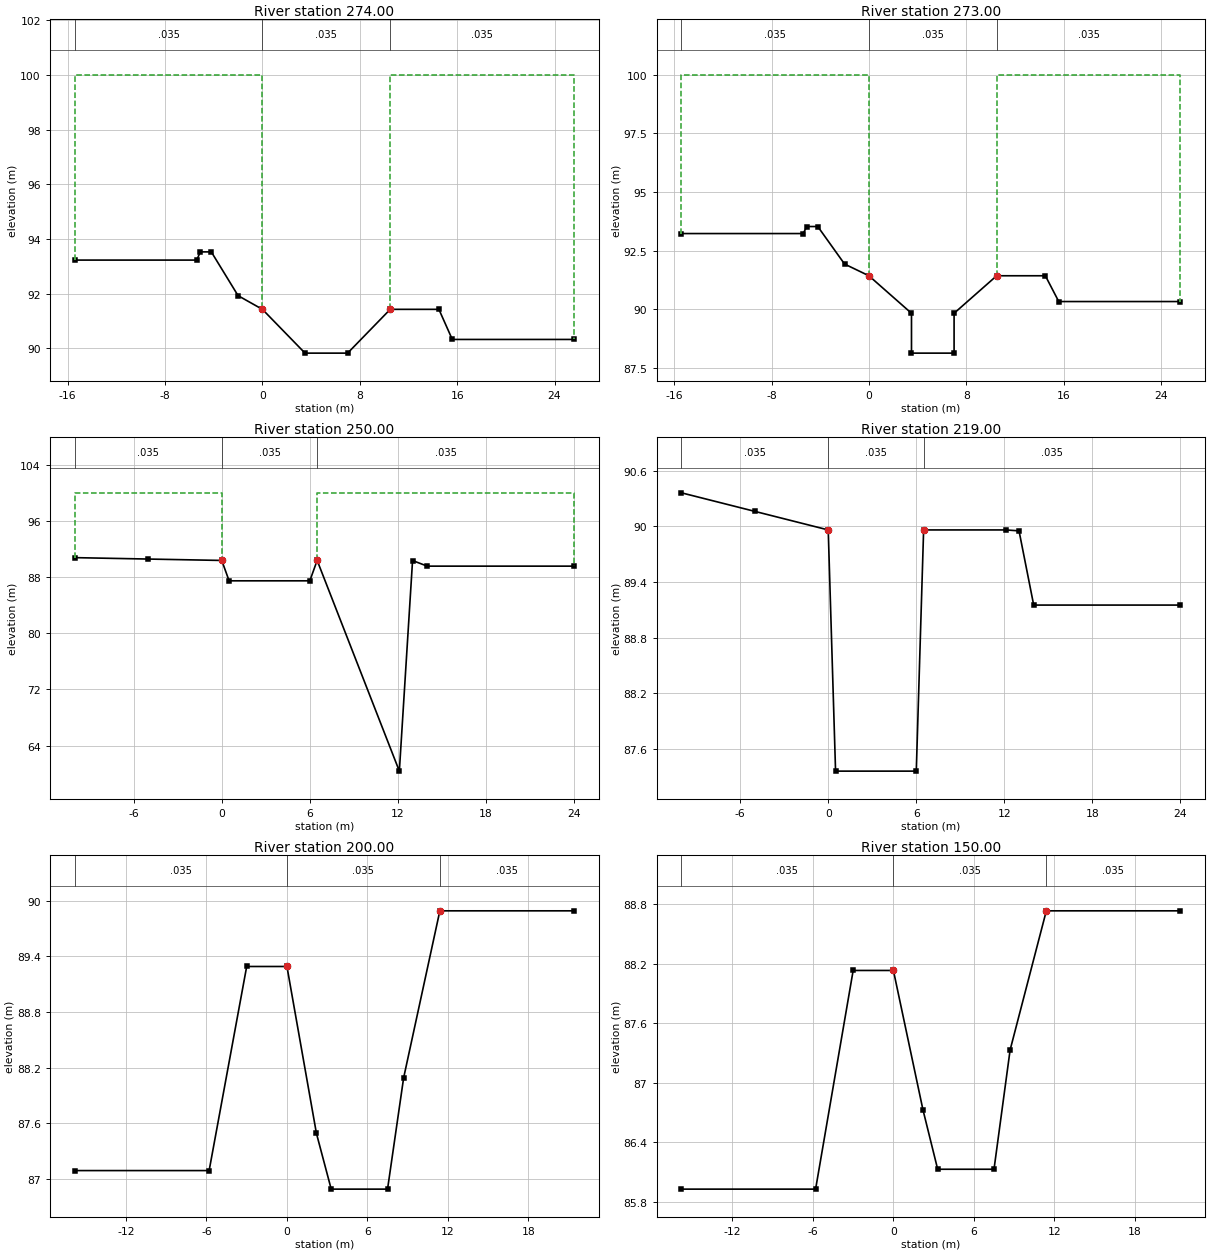
Type RM Length L Ch R = 1 ,274.00  ,1,1,1
BEGIN DESCRIPTION:
5.024
END DESCRIPTION:
#Sta/Elev= 12
   -15.4   93.23    -5.4   93.23    -5.1   93.53    -4.2   93.53      -2   91.93
       0   91.43     3.5   89.83       7   89.83    10.5   91.43    14.5   91.43
    15.6   90.33    25.6   90.33
#Mann= 3 , 0 , 0
   -15.4    .035       0       0    .035       0    10.5    .035       0
#XS Ineff= 2 , 0
               0     100    10.5             100
Permanent Ineff=
       F       F
#Block Obstruct= 2 , 0
                            10.5
Bank Sta=0,10.5
XS Rating Curve= 0
Exp/Cntr=.3,.1

Type RM Length L Ch R = 1 ,273.00  ,23,23,23
BEGIN DESCRIPTION:
5.023
END DESCRIPTION:
#Sta/Elev= 14
   -15.4   93.23    -5.4   93.23    -5.1   93.53    -4.2   93.53      -2   91.93
       0   91.43     3.5   89.83     3.5   88.13       7   88.13       7   89.83
    10.5   91.43    14.5   91.43    15.6   90.33    25.6   90.33
#Mann= 3 , 0 , 0
   -15.4    .035       0       0    .035       0    10.5    .035       0
#XS Ineff= 2 , 0
               0     100    10.5             100
Permanent Ineff=
       F       F
#Block Obstruct= 2 , 0
                            10.5
Bank Sta=0,10.5
XS Rating Curve= 0
Exp/Cntr=.3,.1

Type RM Length L Ch R = 1 ,250.00  ,31,31,31
BEGIN DESCRIPTION:
5
END DESCRIPTION:
#Sta/Elev= 10
     -10   90.77      -5   90.57       0   90.37      .5   87.47       6   87.47
     6.5   90.37    12.1   60.37      13   90.36      14   89.56      24   89.56
#Mann= 3 , 0 , 0
     -10    .035       0       0    .035       0     6.5    .035       0
#XS Ineff= 2 , 0
               0     100     6.5             100
Permanent Ineff=
       F       F
#Block Obstruct= 2 , 0
                             6.5
Bank Sta=0,6.5
XS Rating Curve= 0
Exp/Cntr=.3,.1

Type RM Length L Ch R = 1 ,219.00  ,19,19,19
BEGIN DESCRIPTION:
4.019
END DESCRIPTION:
#Sta/Elev= 10
     -10   90.36      -5   90.16       0   89.96      .5   87.36       6   87.36
     6.5   89.96    12.1   89.96      13   89.95      14   89.15      24   89.15
#Mann= 3 , 0 , 0
     -10    .035       0       0    .035       0     6.5    .035       0
#XS Ineff= 2 , 0
               0     100     6.5             100
Permanent Ineff=
       F       F
#Block Obstruct= 2 , 0
                             6.5
Bank Sta=0,6.5
XS Rating Curve= 0
Exp/Cntr=.3,.1

Type RM Length L Ch R = 1 ,200.00  ,50,50,50
BEGIN DESCRIPTION:
4
END DESCRIPTION:
#Sta/Elev= 10
   -15.8   87.09    -5.8   87.09      -3   89.29       0   89.29     2.2   87.49
     3.3   86.89     7.5   86.89     8.7   88.09    11.4   89.89    21.4   89.89
#Mann= 3 , 0 , 0
   -15.8    .035       0       0    .035       0    11.4    .035       0
#XS Ineff= 2 , 0
               0     100    11.4             100
Permanent Ineff=
       F       F
#Block Obstruct= 2 , 0
                            11.4
Bank Sta=0,11.4
XS Rating Curve= 0
Exp/Cntr=.3,.1

Type RM Length L Ch R = 1 ,150.00  ,29,29,29
BEGIN DESCRIPTION:
3
END DESCRIPTION:
#Sta/Elev= 10
   -15.8   85.93    -5.8   85.93      -3   88.13       0   88.13     2.2   86.73
     3.3   86.13     7.5   86.13     8.7   87.33    11.4   88.73    21.4   88.73
#Mann= 3 , 0 , 0
   -15.8    .035       0       0    .035       0    11.4    .035       0
#XS Ineff= 2 , 0
               0     100    11.4             100
Permanent Ineff=
       F       F
#Block Obstruct= 2 , 0
                            11.4
Bank Sta=0,11.4
XS Rating Curve= 0
Exp/Cntr=.3,.1

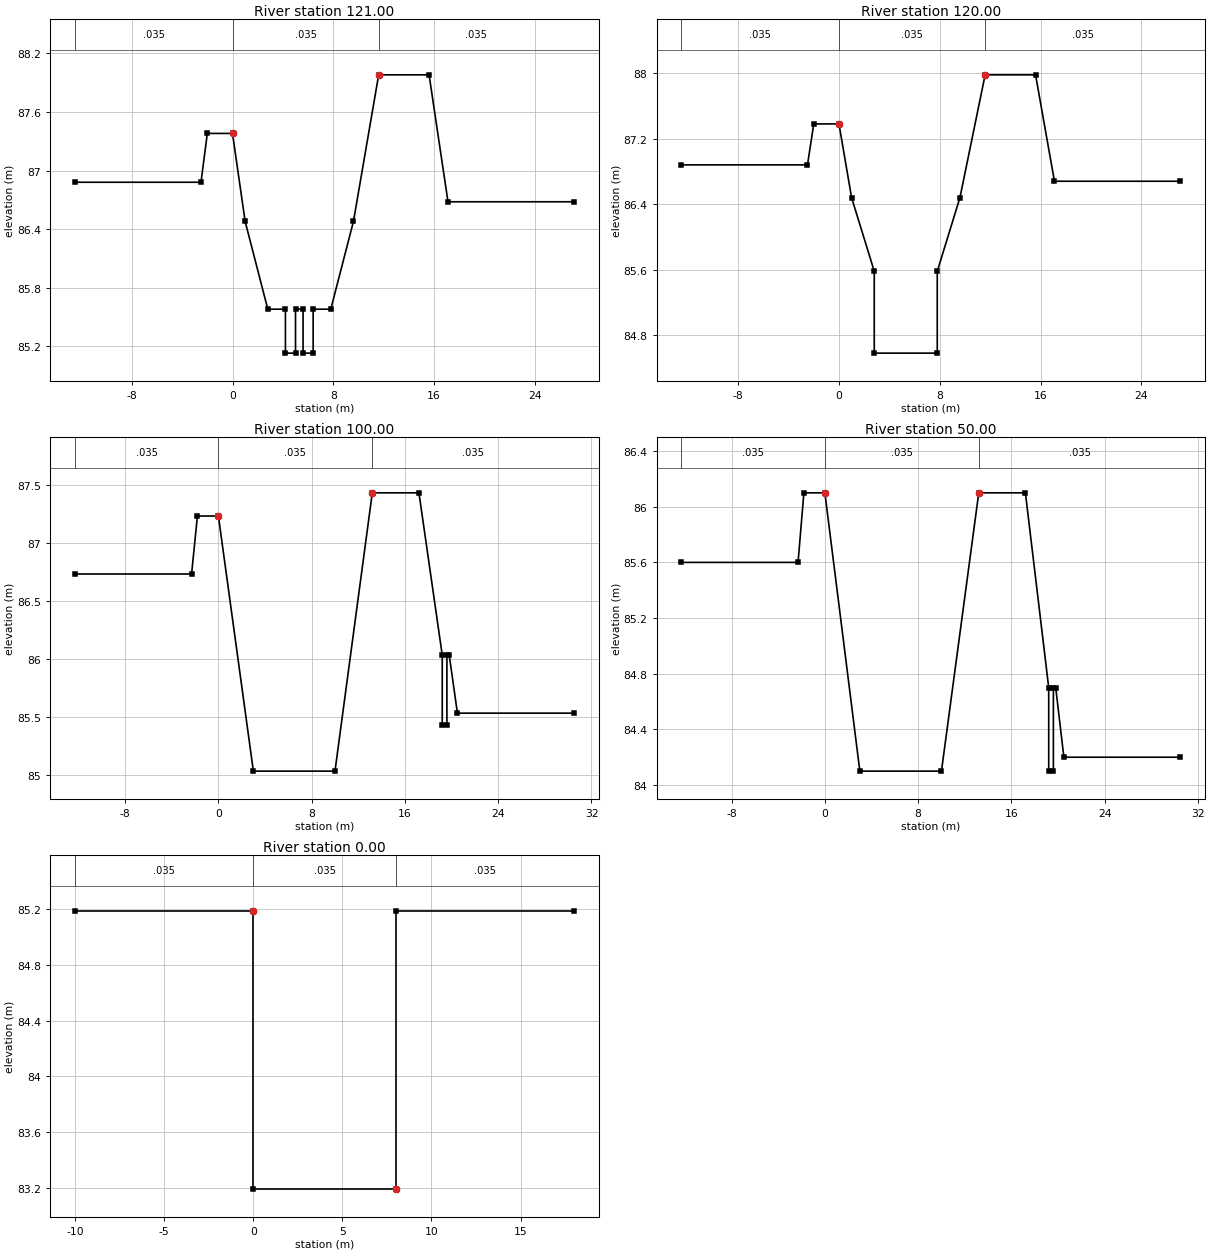
Type RM Length L Ch R = 1 ,121.00  ,1,1,1
BEGIN DESCRIPTION:
2.021
END DESCRIPTION:
#Sta/Elev= 20
   -12.5   86.88    -2.5   86.88      -2   87.38       0   87.38       1   86.48
     2.8   85.58     4.2   85.58     4.2   85.13       5   85.13       5   85.58
     5.6   85.58     5.6   85.13     6.4   85.13     6.4   85.58     7.8   85.58
     9.6   86.48    11.6   87.98    15.6   87.98    17.1   86.68    27.1   86.68
#Mann= 3 , 0 , 0
   -12.5    .035       0       0    .035       0    11.6    .035       0
#XS Ineff= 2 , 0
               0     100    11.6             100
Permanent Ineff=
       F       F
#Block Obstruct= 2 , 0
                            11.6
Bank Sta=0,11.6
XS Rating Curve= 0
Exp/Cntr=.3,.1

Type RM Length L Ch R = 1 ,120.00  ,20,20,20
BEGIN DESCRIPTION:
2.02
END DESCRIPTION:
#Sta/Elev= 14
   -12.5   86.88    -2.5   86.88      -2   87.38       0   87.38       1   86.48
     2.8   85.58     2.8   84.58     7.8   84.58     7.8   85.58     9.6   86.48
    11.6   87.98    15.6   87.98    17.1   86.68    27.1   86.68
#Mann= 3 , 0 , 0
   -12.5    .035       0       0    .035       0    11.6    .035       0
#XS Ineff= 2 , 0
               0     100    11.6             100
Permanent Ineff=
       F       F
#Block Obstruct= 2 , 0
                            11.6
Bank Sta=0,11.6
XS Rating Curve= 0
Exp/Cntr=.3,.1

Type RM Length L Ch R = 1 ,100.00  ,50,50,50
BEGIN DESCRIPTION:
2
END DESCRIPTION:
#Sta/Elev= 15
   -12.3   86.73    -2.3   86.73    -1.8   87.23       0   87.23       3   85.03
      10   85.03    13.2   87.43    17.2   87.43    19.2   86.03    19.2   85.43
    19.6   85.43    19.6   86.03    19.8   86.03    20.5   85.53    30.5   85.53
#Mann= 3 , 0 , 0
   -12.3    .035       0       0    .035       0    13.2    .035       0
#XS Ineff= 2 , 0
               0     100    13.2             100
Permanent Ineff=
       F       F
#Block Obstruct= 2 , 0
                            13.2
Bank Sta=0,13.2
XS Rating Curve= 0
Exp/Cntr=.3,.1

Type RM Length L Ch R = 1 ,50.00   ,50,50,50
BEGIN DESCRIPTION:
1
END DESCRIPTION:
#Sta/Elev= 15
   -12.3    85.6    -2.3    85.6    -1.8    86.1       0    86.1       3    84.1
      10    84.1    13.2    86.1    17.2    86.1    19.2    84.7    19.2    84.1
    19.6    84.1    19.6    84.7    19.8    84.7    20.5    84.2    30.5    84.2
#Mann= 3 , 0 , 0
   -12.3    .035       0       0    .035       0    13.2    .035       0
#XS Ineff= 2 , 0
               0     100    13.2             100
Permanent Ineff=
       F       F
#Block Obstruct= 2 , 0
                            13.2
Bank Sta=0,13.2
XS Rating Curve= 0
Exp/Cntr=.3,.1

Type RM Length L Ch R = 1 ,0.00    ,0,0,0
BEGIN DESCRIPTION:
0
END DESCRIPTION:
#Sta/Elev= 6
     -10   85.19       0   85.19       0   83.19       8   83.19       8   85.19
      18   85.19
#Mann= 3 , 0 , 0
     -10    .035       0       0    .035       0       8    .035       0
#XS Ineff= 2 , 0
               0     100       8             100
Permanent Ineff=
       F       F
#Block Obstruct= 2 , 0
                               8
Bank Sta=0,8
XS Rating Curve= 0
Exp/Cntr=.3,.1

Chan Stop Cuts=-1