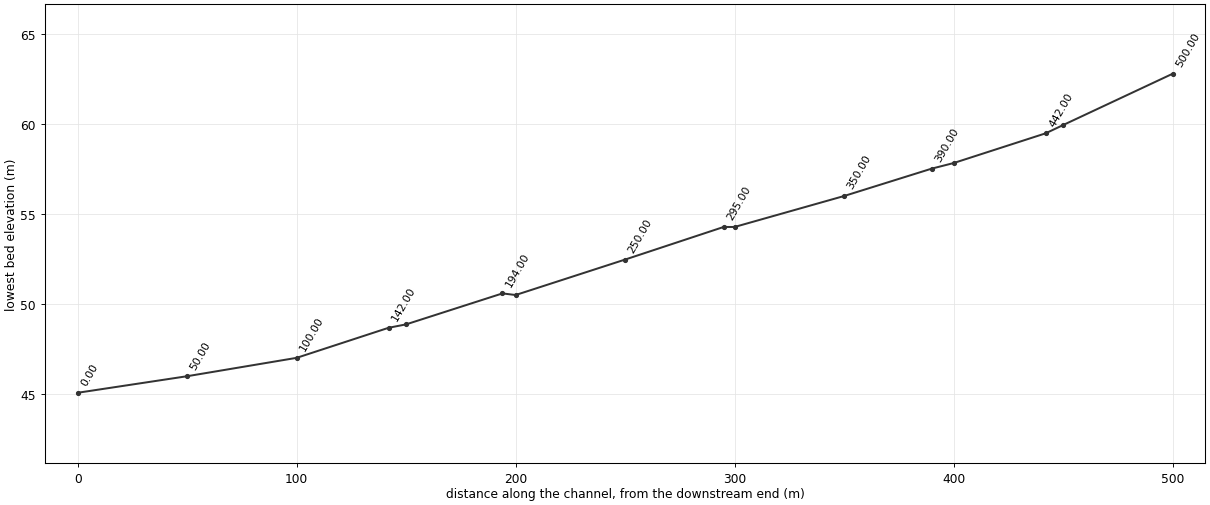
--- JUNG.prj (project) ---

Proj Title=JUNG
Current Plan=p01
Default Exp/Contr=.3,.1
SI Units
Geom File=g01
Flow File=f01
Plan File=p01
Y Axis Title=Elevation
X Axis Title(PF)=Main Channel Distance
X Axis Title(XS)=Station
BEGIN DESCRIPTION:
           BACK WATER COMPUTATION
      APPLICATION OF HEC-2 BY Samju Construction Engineering
      jungdong-ch: 10,20,30,50,80 yr
END DESCRIPTION:
DSS Export Rating Curves= 0
DSS Export Rating Curve Sorted= 0
DSS Export Volume Flow Curves= 0
DXF OffsetX= 0
DXF OffsetY= 0
DXF ScaleX= 1
DXF ScaleY= 10

--- JUNG.p01 (plan) ---

Plan Title=Imported Plan 01
Version=Version 3.0.1  Mar 2001
Short Identifier=Imported Pla
Geom File=g01
Flow File=f01
Subcritical Flow
K Sum by GR= 0
Std Step Tol= 0.003
Critical Tol= 0.003
Num of Std Step Trials= 20
Max Error Tol= 0.1
Flow Tol Ratio= 0.001
Split Flow NTrial= 30
Split Flow Tol= 0.02
Split Flow Ratio= 0.02
Log Output Level= 0
Friction Slope Method= 1
Unsteady Friction Slope Method= 2
Parabolic Critical Depth
Global Vel Dist= 0 , 0 , 0
Global Log Level= 0
CheckData=True
Encroach Param=-1 ,0,0, 0
Computation Interval=1HOUR
Output Interval=1HOUR
Run HTab= 0
Run UNet= 0
Run PostProcess= 0
UNET Theta= 1
UNET ZTol= 0.02
UNET ZSATol= 0.1
UNET MxIter= 20
UNET MaxInSteps= 20
UNET DtIC= 0
UNET DtMin= 0
UNET MaxCRTS= 20
UNET WFStab= 2
UNET SFStab= 1
UNET WFX= 1
UNET SFX= 1
UNET Convert EG Bridges=-1
UNET Use Existing IB Tables=-1
Instantaneous Interval=1HOUR
Write IC File= 0
Write Velocity= 0
Write Detailed= 0

--- JUNG.f01 (steady flow) ---

Flow Title=Imported Flow 01
Version=Version 3.0.1  Mar 2001
Number of Profiles= 5
Profile Names=10YR,20YR,30YR,50YR,80YR
River Rch & RM=RIVER-1,Reach-1         ,500.00
    2.52    2.77    2.92    3.11    3.28
Boundary for River Rch & Prof#=RIVER-1,Reach-1         , 1
Up Type= 0
Dn Type= 3
Dn Slope=.036
Boundary for River Rch & Prof#=RIVER-1,Reach-1         , 2
Up Type= 0
Dn Type= 3
Dn Slope=.036
Boundary for River Rch & Prof#=RIVER-1,Reach-1         , 3
Up Type= 0
Dn Type= 3
Dn Slope=.036
Boundary for River Rch & Prof#=RIVER-1,Reach-1         , 4
Up Type= 0
Dn Type= 3
Dn Slope=.036
Boundary for River Rch & Prof#=RIVER-1,Reach-1         , 5
Up Type= 0
Dn Type= 3
Dn Slope=.036
DSS Import GetInterval= 0
DSS Import GetPeak= 0
DSS Import FillOption= 0

--- JUNG.g01 (geometry) ---

Geom Title=Imported Geom 01
Version=Version 3.0.1  Mar 2001

River Reach=RIVER-1         ,Reach-1
Reach XY= 2
              .5             .95              .5             .05

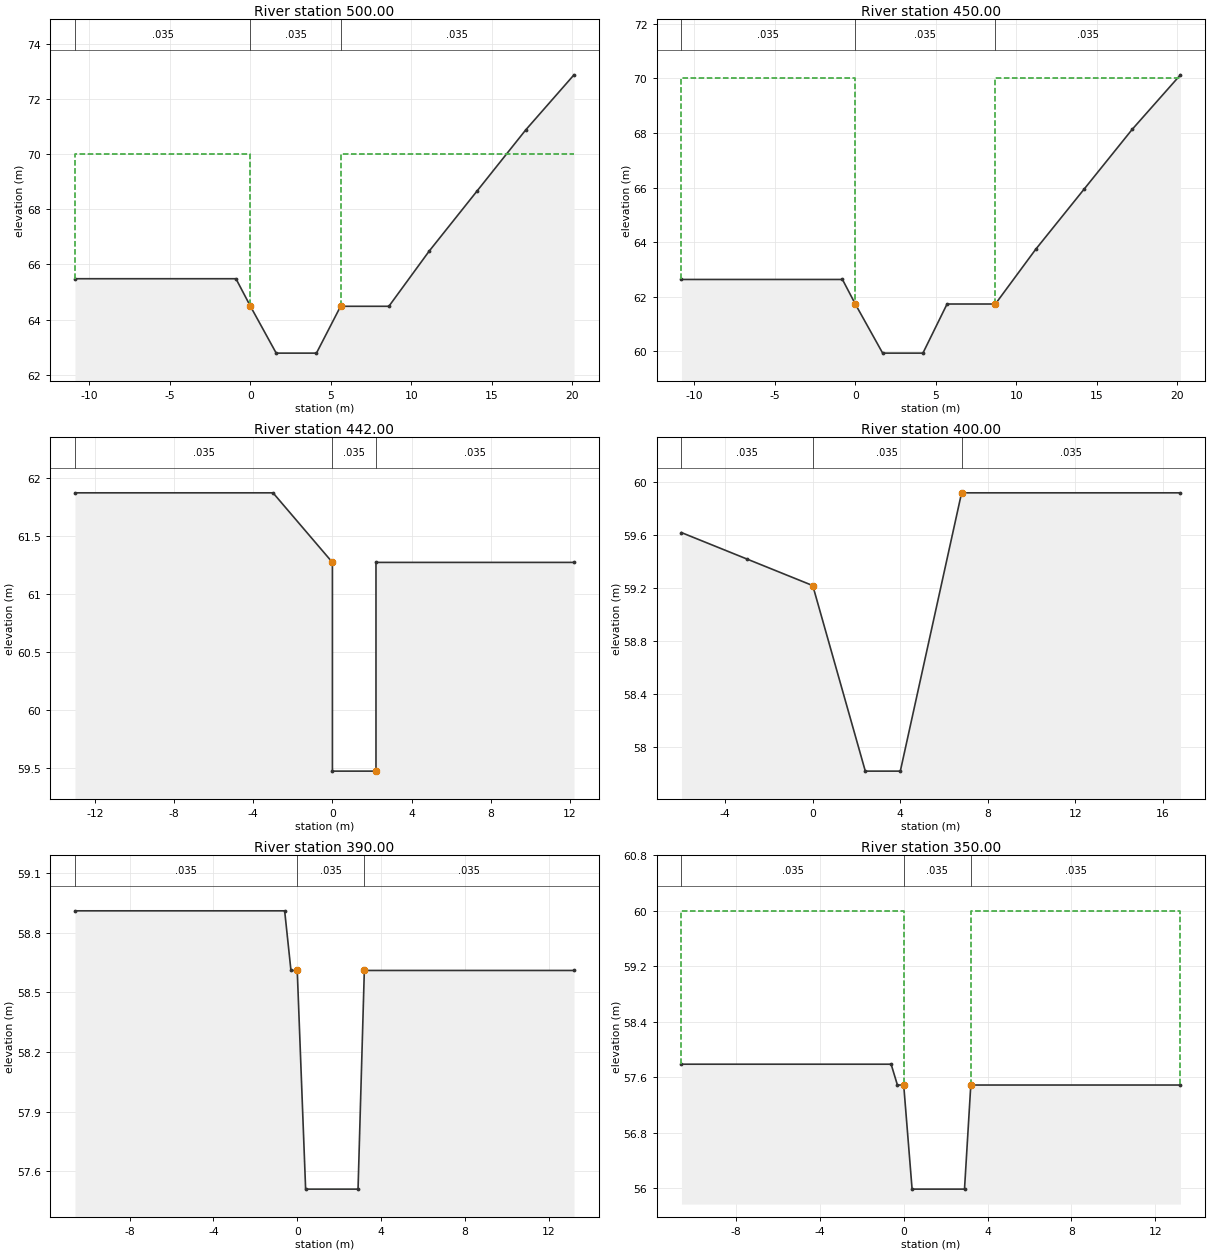
Type RM Length L Ch R = 1 ,500.00  ,50,50,50
BEGIN DESCRIPTION:
10
END DESCRIPTION:
#Sta/Elev= 11
   -10.9   65.48     -.9   65.48       0   64.48     1.6   62.78     4.1   62.78
     5.6   64.48     8.6   64.48    11.1   66.48    14.1   68.68    17.1   70.88
    20.1   72.88
#Mann= 3 , 0 , 0
   -10.9    .035       0       0    .035       0     5.6    .035       0
#XS Ineff= 2 , 0
               0      70     5.6              70
Permanent Ineff=
       F       F
#Block Obstruct= 2 , 0
                             5.6
Bank Sta=0,5.6
XS Rating Curve= 0
Exp/Cntr=.3,.1

Type RM Length L Ch R = 1 ,450.00  ,8,8,8
BEGIN DESCRIPTION:
9
END DESCRIPTION:
#Sta/Elev= 11
   -10.8   62.63     -.8   62.63       0   61.73     1.7   59.93     4.2   59.93
     5.7   61.73     8.7   61.73    11.2   63.73    14.2   65.93    17.2   68.13
    20.2   70.13
#Mann= 3 , 0 , 0
   -10.8    .035       0       0    .035       0     8.7    .035       0
#XS Ineff= 2 , 0
               0      70     8.7              70
Permanent Ineff=
       F       F
#Block Obstruct= 2 , 0
                             8.7
Bank Sta=0,8.7
XS Rating Curve= 0
Exp/Cntr=.3,.1

Type RM Length L Ch R = 1 ,442.00  ,42,42,42
BEGIN DESCRIPTION:
8.042
END DESCRIPTION:
#Sta/Elev= 7
     -13   61.87      -3   61.87       0   61.27       0   59.47     2.2   59.47
     2.2   61.27    12.2   61.27
#Mann= 3 , 0 , 0
     -13    .035       0       0    .035       0     2.2    .035       0
#XS Ineff= 2 , 0
               0      70     2.2              70
Permanent Ineff=
       F       F
#Block Obstruct= 2 , 0
                             2.2
Bank Sta=0,2.2
XS Rating Curve= 0
Exp/Cntr=.3,.1

Type RM Length L Ch R = 1 ,400.00  ,10,10,10
BEGIN DESCRIPTION:
8
END DESCRIPTION:
#Sta/Elev= 7
      -6   59.62      -3   59.42       0   59.22     2.4   57.82       4   57.82
     6.8   59.92    16.8   59.92
#Mann= 3 , 0 , 0
      -6    .035       0       0    .035       0     6.8    .035       0
#XS Ineff= 2 , 0
               0      70     6.8              70
Permanent Ineff=
       F       F
#Block Obstruct= 2 , 0
                             6.8
Bank Sta=0,6.8
XS Rating Curve= 0
Exp/Cntr=.3,.1

Type RM Length L Ch R = 1 ,390.00  ,40,40,40
BEGIN DESCRIPTION:
7.04
END DESCRIPTION:
#Sta/Elev= 8
   -10.6   58.91     -.6   58.91     -.3   58.61       0   58.61      .4   57.51
     2.9   57.51     3.2   58.61    13.2   58.61
#Mann= 3 , 0 , 0
   -10.6    .035       0       0    .035       0     3.2    .035       0
#XS Ineff= 2 , 0
               0      65     3.2              65
Permanent Ineff=
       F       F
#Block Obstruct= 2 , 0
                             3.2
Bank Sta=0,3.2
XS Rating Curve= 0
Exp/Cntr=.3,.1

Type RM Length L Ch R = 1 ,350.00  ,50,50,50
BEGIN DESCRIPTION:
7
END DESCRIPTION:
#Sta/Elev= 8
   -10.6   57.79     -.6   57.79     -.3   57.49       0   57.49      .4   55.99
     2.9   55.99     3.2   57.49    13.2   57.49
#Mann= 3 , 0 , 0
   -10.6    .035       0       0    .035       0     3.2    .035       0
#XS Ineff= 2 , 0
               0      60     3.2              60
Permanent Ineff=
       F       F
#Block Obstruct= 2 , 0
                             3.2
Bank Sta=0,3.2
XS Rating Curve= 0
Exp/Cntr=.3,.1

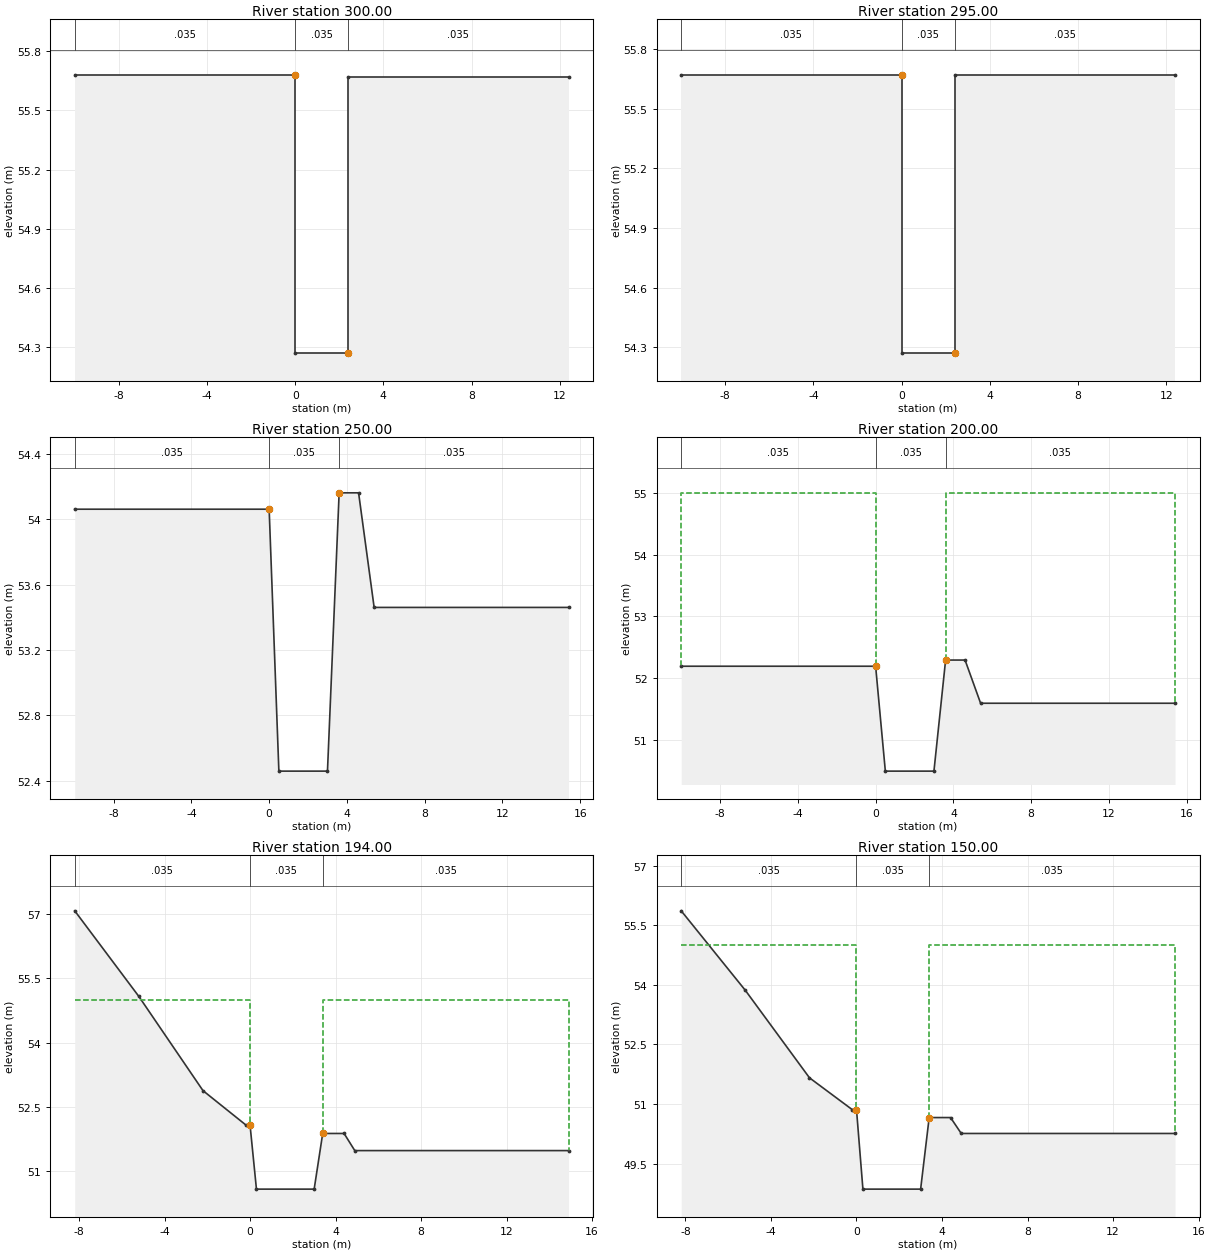
Type RM Length L Ch R = 1 ,300.00  ,5,5,5
BEGIN DESCRIPTION:
6
END DESCRIPTION:
#Sta/Elev= 6
     -10   55.68       0   55.68       0   54.27     2.4   54.27     2.4   55.67
    12.4   55.67
#Mann= 3 , 0 , 0
     -10    .035       0       0    .035       0     2.4    .035       0
#XS Ineff= 2 , 0
               0      60     2.4              60
Permanent Ineff=
       F       F
#Block Obstruct= 2 , 0
                             2.4
Bank Sta=0,2.4
XS Rating Curve= 0
Exp/Cntr=.3,.1

Type RM Length L Ch R = 1 ,295.00  ,45,45,45
BEGIN DESCRIPTION:
5.045
END DESCRIPTION:
#Sta/Elev= 6
     -10   55.67       0   55.67       0   54.27     2.4   54.27     2.4   55.67
    12.4   55.67
#Mann= 3 , 0 , 0
     -10    .035       0       0    .035       0     2.4    .035       0
#XS Ineff= 2 , 0
               0      60     2.4              60
Permanent Ineff=
       F       F
#Block Obstruct= 2 , 0
                             2.4
Bank Sta=0,2.4
XS Rating Curve= 0
Exp/Cntr=.3,.1

Type RM Length L Ch R = 1 ,250.00  ,50,50,50
BEGIN DESCRIPTION:
5
END DESCRIPTION:
#Sta/Elev= 8
     -10   54.06       0   54.06      .5   52.46       3   52.46     3.6   54.16
     4.6   54.16     5.4   53.46    15.4   53.46
#Mann= 3 , 0 , 0
     -10    .035       0       0    .035       0     3.6    .035       0
#XS Ineff= 2 , 0
               0      60     3.6              60
Permanent Ineff=
       F       F
#Block Obstruct= 2 , 0
                             3.6
Bank Sta=0,3.6
XS Rating Curve= 0
Exp/Cntr=.3,.1

Type RM Length L Ch R = 1 ,200.00  ,6,6,6
BEGIN DESCRIPTION:
4
END DESCRIPTION:
#Sta/Elev= 8
     -10   52.19       0   52.19      .5   50.49       3   50.49     3.6   52.29
     4.6   52.29     5.4   51.59    15.4   51.59
#Mann= 3 , 0 , 0
     -10    .035       0       0    .035       0     3.6    .035       0
#XS Ineff= 2 , 0
               0      55     3.6              55
Permanent Ineff=
       F       F
#Block Obstruct= 2 , 0
                             3.6
Bank Sta=0,3.6
XS Rating Curve= 0
Exp/Cntr=.3,.1

Type RM Length L Ch R = 1 ,194.00  ,44,44,44
BEGIN DESCRIPTION:
3.044
END DESCRIPTION:
#Sta/Elev= 11
    -8.2   57.08    -5.2   55.08    -2.2   52.88     -.2   52.08       0   52.08
      .3   50.58       3   50.58     3.4   51.88     4.4   51.88     4.9   51.48
    14.9   51.48
#Mann= 3 , 0 , 0
    -8.2    .035       0       0    .035       0     3.4    .035       0
#XS Ineff= 2 , 0
               0      55     3.4              55
Permanent Ineff=
       F       F
#Block Obstruct= 2 , 0
                             3.4
Bank Sta=0,3.4
XS Rating Curve= 0
Exp/Cntr=.3,.1

Type RM Length L Ch R = 1 ,150.00  ,8,8,8
BEGIN DESCRIPTION:
3
END DESCRIPTION:
#Sta/Elev= 11
    -8.2   55.86    -5.2   53.86    -2.2   51.66     -.2   50.86       0   50.86
      .3   48.86       3   48.86     3.4   50.66     4.4   50.66     4.9   50.26
    14.9   50.26
#Mann= 3 , 0 , 0
    -8.2    .035       0       0    .035       0     3.4    .035       0
#XS Ineff= 2 , 0
               0      55     3.4              55
Permanent Ineff=
       F       F
#Block Obstruct= 2 , 0
                             3.4
Bank Sta=0,3.4
XS Rating Curve= 0
Exp/Cntr=.3,.1

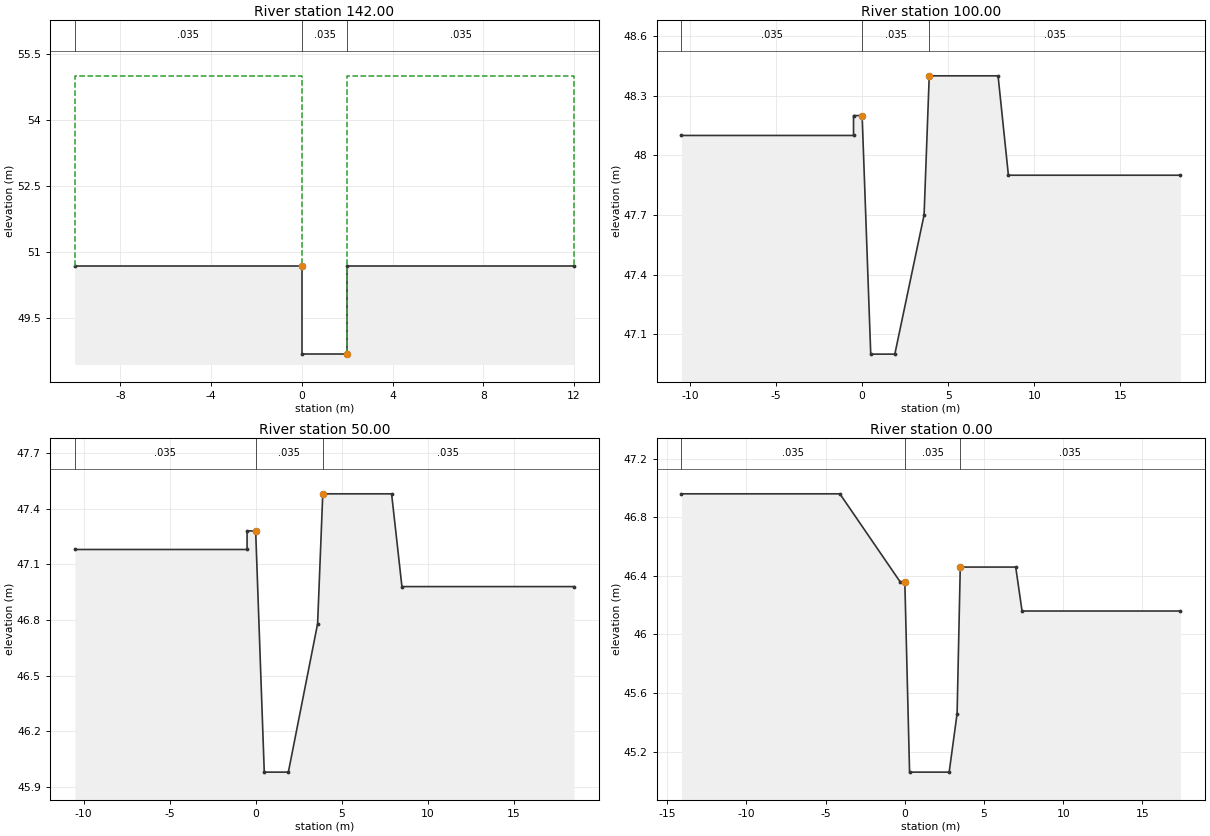
Type RM Length L Ch R = 1 ,142.00  ,42,42,42
BEGIN DESCRIPTION:
2.042
END DESCRIPTION:
#Sta/Elev= 6
     -10   50.67       0   50.67       0   48.67       2   48.67       2   50.67
      12   50.67
#Mann= 3 , 0 , 0
     -10    .035       0       0    .035       0       2    .035       0
#XS Ineff= 2 , 0
               0      55       2              55
Permanent Ineff=
       F       F
#Block Obstruct= 2 , 0
                               2
Bank Sta=0,2
XS Rating Curve= 0
Exp/Cntr=.3,.1

Type RM Length L Ch R = 1 ,100.00  ,50,50,50
BEGIN DESCRIPTION:
2
END DESCRIPTION:
#Sta/Elev= 11
   -10.5    48.1     -.5    48.1     -.5    48.2       0    48.2      .5      47
     1.9      47     3.6    47.7     3.9    48.4     7.9    48.4     8.5    47.9
    18.5    47.9
#Mann= 3 , 0 , 0
   -10.5    .035       0       0    .035       0     3.9    .035       0
#XS Ineff= 2 , 0
               0      55     3.9              55
Permanent Ineff=
       F       F
#Block Obstruct= 2 , 0
                             3.9
Bank Sta=0,3.9
XS Rating Curve= 0
Exp/Cntr=.3,.1

Type RM Length L Ch R = 1 ,50.00   ,50,50,50
BEGIN DESCRIPTION:
1
END DESCRIPTION:
#Sta/Elev= 11
   -10.5   47.18     -.5   47.18     -.5   47.28       0   47.28      .5   45.98
     1.9   45.98     3.6   46.78     3.9   47.48     7.9   47.48     8.5   46.98
    18.5   46.98
#Mann= 3 , 0 , 0
   -10.5    .035       0       0    .035       0     3.9    .035       0
#XS Ineff= 2 , 0
               0      55     3.9              55
Permanent Ineff=
       F       F
#Block Obstruct= 2 , 0
                             3.9
Bank Sta=0,3.9
XS Rating Curve= 0
Exp/Cntr=.3,.1

Type RM Length L Ch R = 1 ,0.00    ,0,0,0
BEGIN DESCRIPTION:
0
END DESCRIPTION:
#Sta/Elev= 11
   -14.1   46.96    -4.1   46.96     -.3   46.36       0   46.36      .3   45.06
     2.8   45.06     3.3   45.46     3.5   46.46       7   46.46     7.4   46.16
    17.4   46.16
#Mann= 3 , 0 , 0
   -14.1    .035       0       0    .035       0     3.5    .035       0
#XS Ineff= 2 , 0
               0      55     3.5              55
Permanent Ineff=
       F       F
#Block Obstruct= 2 , 0
                             3.5
Bank Sta=0,3.5
XS Rating Curve= 0
Exp/Cntr=.3,.1

Chan Stop Cuts=-1