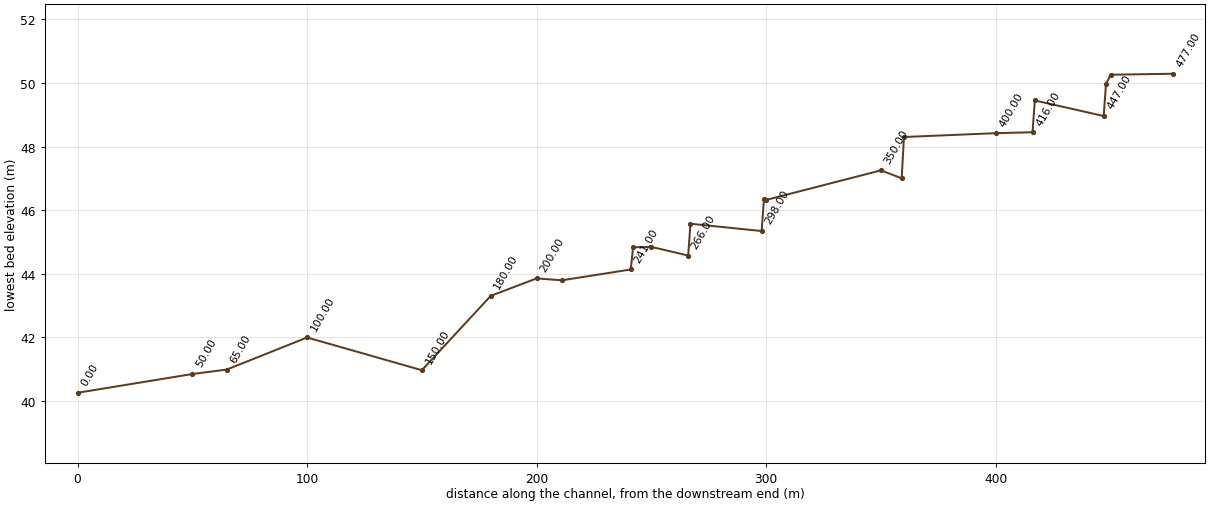
HEC-RAS study OK.prj: OK

--- OK.g01 (geometry) --- (continued)

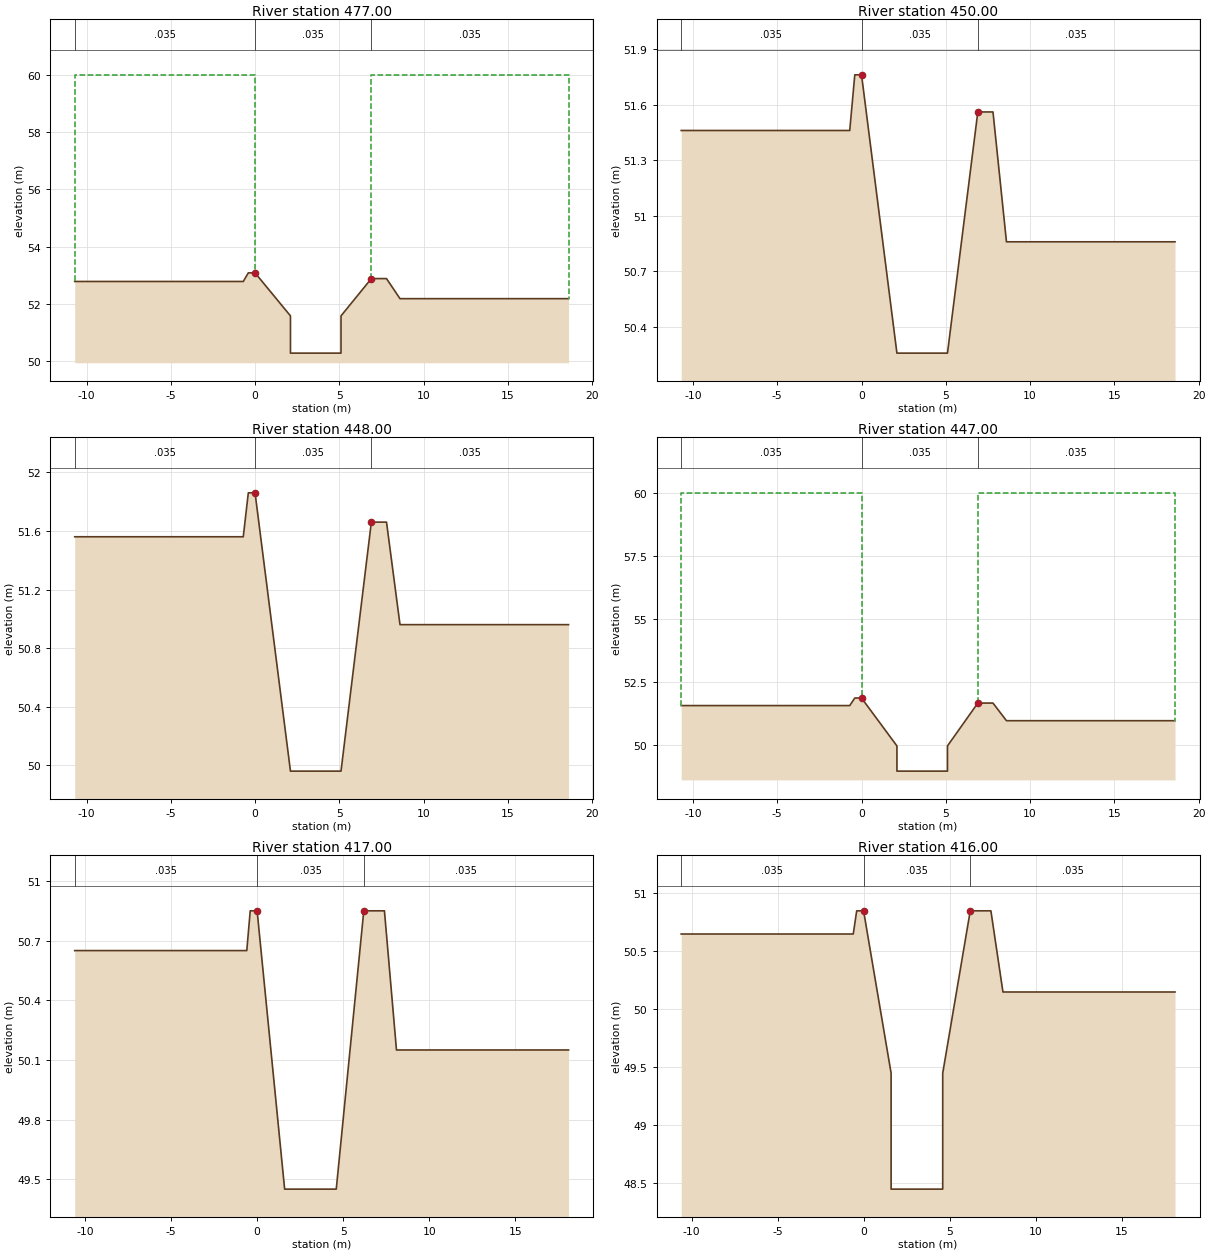
Type RM Length L Ch R = 1 ,477.00  ,27,27,27
BEGIN DESCRIPTION:
9.027
END DESCRIPTION:
#Sta/Elev= 12
   -10.7   52.79     -.7   52.79     -.4   53.09       0   53.09     2.1   51.59
     2.1   50.29     5.1   50.29     5.1   51.59     6.9   52.89     7.8   52.89
     8.6   52.19    18.6   52.19
#Mann= 3 , 0 , 0
   -10.7    .035       0       0    .035       0     6.9    .035       0
#XS Ineff= 2 , 0
               0      60     6.9              60
Permanent Ineff=
       F       F
#Block Obstruct= 2 , 0
                             6.9
Bank Sta=0,6.9
XS Rating Curve= 0
Exp/Cntr=.3,.1

Type RM Length L Ch R = 1 ,450.00  ,2,2,2
BEGIN DESCRIPTION:
9
END DESCRIPTION:
#Sta/Elev= 10
   -10.7   51.46     -.7   51.46     -.4   51.76       0   51.76     2.1   50.26
     5.1   50.26     6.9   51.56     7.8   51.56     8.6   50.86    18.6   50.86
#Mann= 3 , 0 , 0
   -10.7    .035       0       0    .035       0     6.9    .035       0
#XS Ineff= 2 , 0
               0      60     6.9              60
Permanent Ineff=
       F       F
#Block Obstruct= 2 , 0
                             6.9
Bank Sta=0,6.9
XS Rating Curve= 0
Exp/Cntr=.3,.1

Type RM Length L Ch R = 1 ,448.00  ,1,1,1
BEGIN DESCRIPTION:
8.048
END DESCRIPTION:
#Sta/Elev= 10
   -10.7   51.56     -.7   51.56     -.4   51.86       0   51.86     2.1   49.96
     5.1   49.96     6.9   51.66     7.8   51.66     8.6   50.96    18.6   50.96
#Mann= 3 , 0 , 0
   -10.7    .035       0       0    .035       0     6.9    .035       0
#XS Ineff= 2 , 0
               0      60     6.9              60
Permanent Ineff=
       F       F
#Block Obstruct= 2 , 0
                             6.9
Bank Sta=0,6.9
XS Rating Curve= 0
Exp/Cntr=.3,.1

Type RM Length L Ch R = 1 ,447.00  ,30,30,30
BEGIN DESCRIPTION:
8.047
END DESCRIPTION:
#Sta/Elev= 12
   -10.7   51.56     -.7   51.56     -.4   51.86       0   51.86     2.1   49.96
     2.1   48.96     5.1   48.96     5.1   49.96     6.9   51.66     7.8   51.66
     8.6   50.96    18.6   50.96
#Mann= 3 , 0 , 0
   -10.7    .035       0       0    .035       0     6.9    .035       0
#XS Ineff= 2 , 0
               0      60     6.9              60
Permanent Ineff=
       F       F
#Block Obstruct= 2 , 0
                             6.9
Bank Sta=0,6.9
XS Rating Curve= 0
Exp/Cntr=.3,.1

Type RM Length L Ch R = 1 ,417.00  ,1,1,1
BEGIN DESCRIPTION:
8.017
END DESCRIPTION:
#Sta/Elev= 10
   -10.6   50.65     -.6   50.65     -.4   50.85       0   50.85     1.6   49.45
     4.6   49.45     6.2   50.85     7.4   50.85     8.1   50.15    18.1   50.15
#Mann= 3 , 0 , 0
   -10.6    .035       0       0    .035       0     6.2    .035       0
#XS Ineff= 2 , 0
               0      60     6.2              60
Permanent Ineff=
       F       F
#Block Obstruct= 2 , 0
                             6.2
Bank Sta=0,6.2
XS Rating Curve= 0
Exp/Cntr=.3,.1

Type RM Length L Ch R = 1 ,416.00  ,16,16,16
BEGIN DESCRIPTION:
8.016
END DESCRIPTION:
#Sta/Elev= 12
   -10.6   50.65     -.6   50.65     -.4   50.85       0   50.85     1.6   49.45
     1.6   48.45     4.6   48.45     4.6   49.45     6.2   50.85     7.4   50.85
     8.1   50.15    18.1   50.15
#Mann= 3 , 0 , 0
   -10.6    .035       0       0    .035       0     6.2    .035       0
#XS Ineff= 2 , 0
               0      60     6.2              60
Permanent Ineff=
       F       F
#Block Obstruct= 2 , 0
                             6.2
Bank Sta=0,6.2
XS Rating Curve= 0
Exp/Cntr=.3,.1

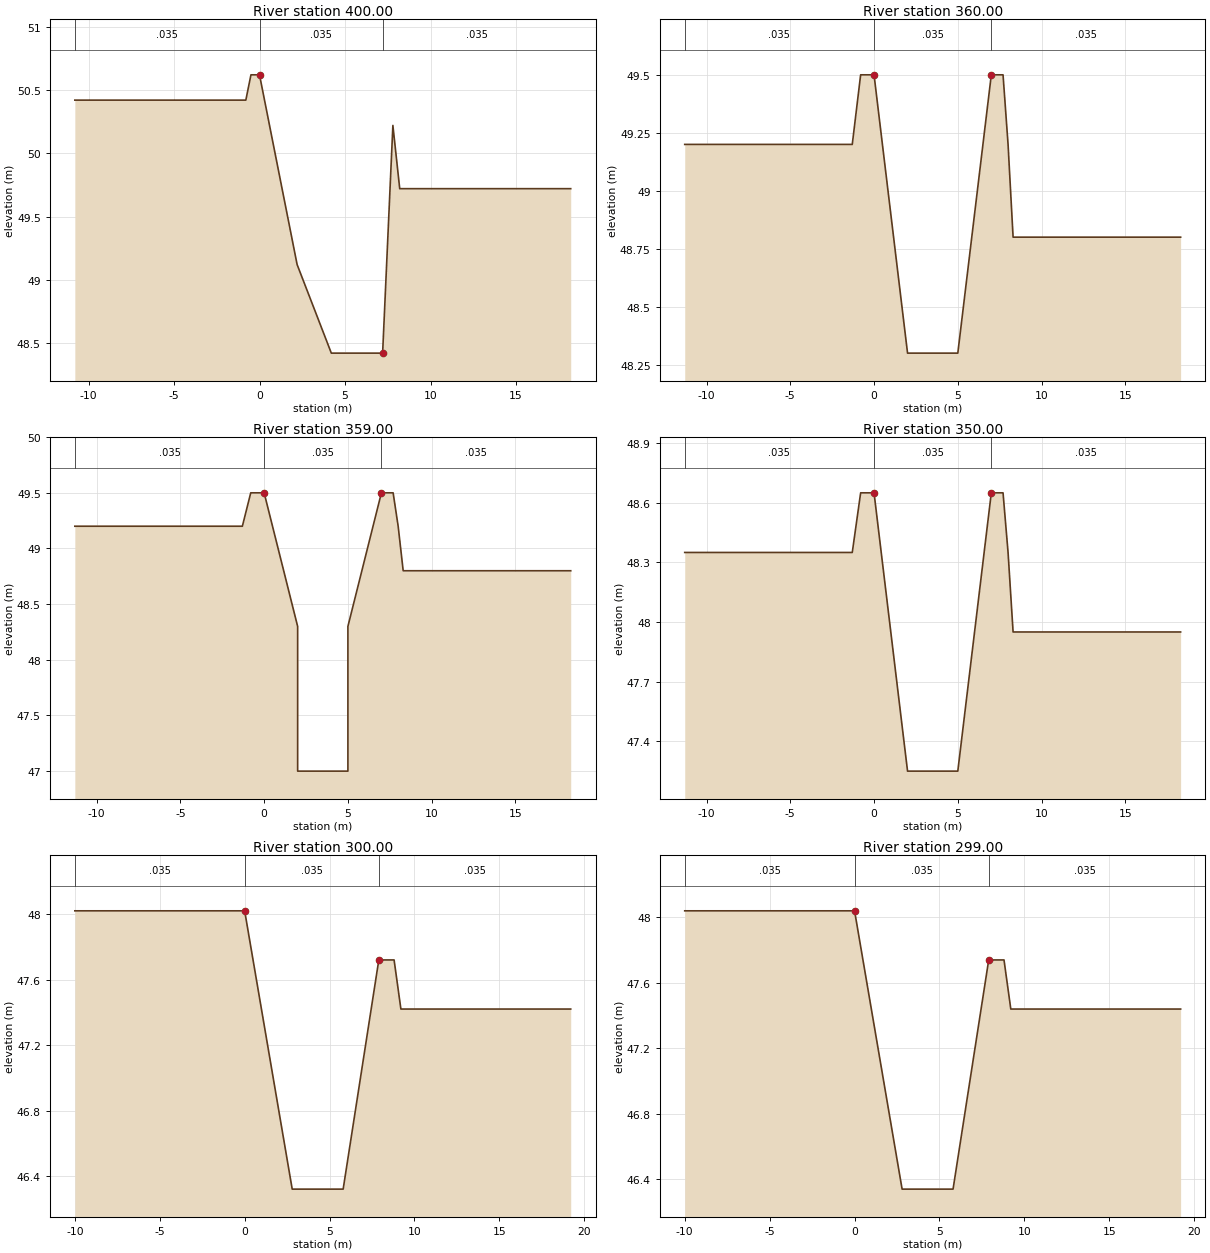
Type RM Length L Ch R = 1 ,400.00  ,40,40,40
BEGIN DESCRIPTION:
8
END DESCRIPTION:
#Sta/Elev= 10
   -10.8   50.42     -.8   50.42     -.5   50.62       0   50.62     2.2   49.12
     4.2   48.42     7.2   48.42     7.8   50.22     8.2   49.72    18.2   49.72
#Mann= 3 , 0 , 0
   -10.8    .035       0       0    .035       0     7.2    .035       0
#XS Ineff= 2 , 0
               0      60     7.2              60
Permanent Ineff=
       F       F
#Block Obstruct= 2 , 0
                             7.2
Bank Sta=0,7.2
XS Rating Curve= 0
Exp/Cntr=.3,.1

Type RM Length L Ch R = 1 ,360.00  ,1,1,1
BEGIN DESCRIPTION:
7.01
END DESCRIPTION:
#Sta/Elev= 11
   -11.3    49.2    -1.3    49.2     -.8    49.5       0    49.5       2    48.3
       5    48.3       7    49.5     7.7    49.5       8    49.2     8.3    48.8
    18.3    48.8
#Mann= 3 , 0 , 0
   -11.3    .035       0       0    .035       0       7    .035       0
#XS Ineff= 2 , 0
               0      60       7              60
Permanent Ineff=
       F       F
#Block Obstruct= 2 , 0
                               7
Bank Sta=0,7
XS Rating Curve= 0
Exp/Cntr=.3,.1

Type RM Length L Ch R = 1 ,359.00  ,9,9,9
BEGIN DESCRIPTION:
7.009
END DESCRIPTION:
#Sta/Elev= 13
   -11.3    49.2    -1.3    49.2     -.8    49.5       0    49.5       2    48.3
       2      47       5      47       5    48.3       7    49.5     7.7    49.5
       8    49.2     8.3    48.8    18.3    48.8
#Mann= 3 , 0 , 0
   -11.3    .035       0       0    .035       0       7    .035       0
#XS Ineff= 2 , 0
               0      60       7              60
Permanent Ineff=
       F       F
#Block Obstruct= 2 , 0
                               7
Bank Sta=0,7
XS Rating Curve= 0
Exp/Cntr=.3,.1

Type RM Length L Ch R = 1 ,350.00  ,50,50,50
BEGIN DESCRIPTION:
7
END DESCRIPTION:
#Sta/Elev= 11
   -11.3   48.35    -1.3   48.35     -.8   48.65       0   48.65       2   47.25
       5   47.25       7   48.65     7.7   48.65       8   48.35     8.3   47.95
    18.3   47.95
#Mann= 3 , 0 , 0
   -11.3    .035       0       0    .035       0       7    .035       0
#XS Ineff= 2 , 0
               0      60       7              60
Permanent Ineff=
       F       F
#Block Obstruct= 2 , 0
                               7
Bank Sta=0,7
XS Rating Curve= 0
Exp/Cntr=.3,.1

Type RM Length L Ch R = 1 ,300.00  ,1,1,1
BEGIN DESCRIPTION:
6
END DESCRIPTION:
#Sta/Elev= 8
     -10   48.02       0   48.02     2.8   46.32     5.8   46.32     7.9   47.72
     8.8   47.72     9.2   47.42    19.2   47.42
#Mann= 3 , 0 , 0
     -10    .035       0       0    .035       0     7.9    .035       0
#XS Ineff= 2 , 0
               0      60     7.9              60
Permanent Ineff=
       F       F
#Block Obstruct= 2 , 0
                             7.9
Bank Sta=0,7.9
XS Rating Curve= 0
Exp/Cntr=.3,.1

Type RM Length L Ch R = 1 ,299.00  ,1,1,1
BEGIN DESCRIPTION:
5.049
END DESCRIPTION:
#Sta/Elev= 8
     -10   48.04       0   48.04     2.8   46.34     5.8   46.34     7.9   47.74
     8.8   47.74     9.2   47.44    19.2   47.44
#Mann= 3 , 0 , 0
     -10    .035       0       0    .035       0     7.9    .035       0
#XS Ineff= 2 , 0
               0      60     7.9              60
Permanent Ineff=
       F       F
#Block Obstruct= 2 , 0
                             7.9
Bank Sta=0,7.9
XS Rating Curve= 0
Exp/Cntr=.3,.1

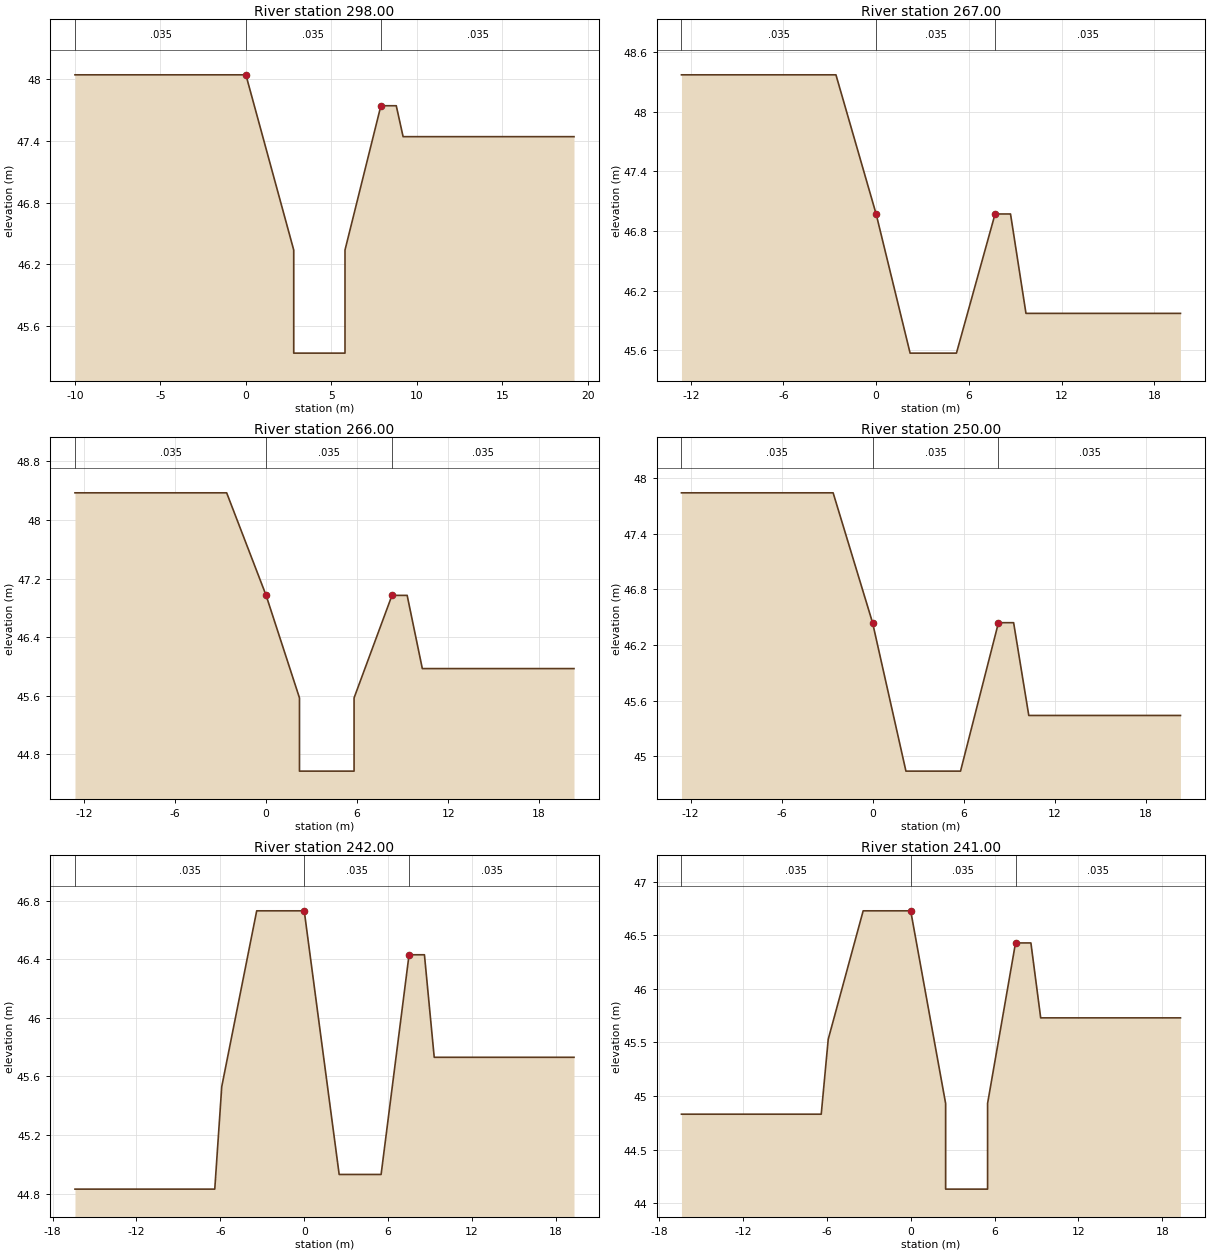
Type RM Length L Ch R = 1 ,298.00  ,31,31,31
BEGIN DESCRIPTION:
5.048
END DESCRIPTION:
#Sta/Elev= 10
     -10   48.04       0   48.04     2.8   46.34     2.8   45.34     5.8   45.34
     5.8   46.34     7.9   47.74     8.8   47.74     9.2   47.44    19.2   47.44
#Mann= 3 , 0 , 0
     -10    .035       0       0    .035       0     7.9    .035       0
#XS Ineff= 2 , 0
               0      60     7.9              60
Permanent Ineff=
       F       F
#Block Obstruct= 2 , 0
                             7.9
Bank Sta=0,7.9
XS Rating Curve= 0
Exp/Cntr=.3,.1

Type RM Length L Ch R = 1 ,267.00  ,1,1,1
BEGIN DESCRIPTION:
5.017
END DESCRIPTION:
#Sta/Elev= 9
   -12.6   48.37    -2.6   48.37       0   46.97     2.2   45.57     5.2   45.57
     7.7   46.97     8.7   46.97     9.7   45.97    19.7   45.97
#Mann= 3 , 0 , 0
   -12.6    .035       0       0    .035       0     7.7    .035       0
#XS Ineff= 2 , 0
               0      60     7.7              60
Permanent Ineff=
       F       F
#Block Obstruct= 2 , 0
                             7.7
Bank Sta=0,7.7
XS Rating Curve= 0
Exp/Cntr=.3,.1

Type RM Length L Ch R = 1 ,266.00  ,16,16,16
BEGIN DESCRIPTION:
5.016
END DESCRIPTION:
#Sta/Elev= 11
   -12.6   48.37    -2.6   48.37       0   46.97     2.2   45.57     2.2   44.57
     5.8   44.57     5.8   45.57     8.3   46.97     9.3   46.97    10.3   45.97
    20.3   45.97
#Mann= 3 , 0 , 0
   -12.6    .035       0       0    .035       0     8.3    .035       0
#XS Ineff= 2 , 0
               0      60     8.3              60
Permanent Ineff=
       F       F
#Block Obstruct= 2 , 0
                             8.3
Bank Sta=0,8.3
XS Rating Curve= 0
Exp/Cntr=.3,.1

Type RM Length L Ch R = 1 ,250.00  ,8,8,8
BEGIN DESCRIPTION:
5
END DESCRIPTION:
#Sta/Elev= 9
   -12.6   47.84    -2.6   47.84       0   46.44     2.2   44.84     5.8   44.84
     8.3   46.44     9.3   46.44    10.3   45.44    20.3   45.44
#Mann= 3 , 0 , 0
   -12.6    .035       0       0    .035       0     8.3    .035       0
#XS Ineff= 2 , 0
               0      60     8.3              60
Permanent Ineff=
       F       F
#Block Obstruct= 2 , 0
                             8.3
Bank Sta=0,8.3
XS Rating Curve= 0
Exp/Cntr=.3,.1

Type RM Length L Ch R = 1 ,242.00  ,1,1,1
BEGIN DESCRIPTION:
4.042
END DESCRIPTION:
#Sta/Elev= 12
   -16.4   44.83    -6.4   44.83    -5.9   45.53    -3.4   46.73     -.4   46.73
       0   46.73     2.5   44.93     5.5   44.93     7.5   46.43     8.6   46.43
     9.3   45.73    19.3   45.73
#Mann= 3 , 0 , 0
   -16.4    .035       0       0    .035       0     7.5    .035       0
#XS Ineff= 2 , 0
               0      60     7.5              60
Permanent Ineff=
       F       F
#Block Obstruct= 2 , 0
                             7.5
Bank Sta=0,7.5
XS Rating Curve= 0
Exp/Cntr=.3,.1

Type RM Length L Ch R = 1 ,241.00  ,30,30,30
BEGIN DESCRIPTION:
4.041
END DESCRIPTION:
#Sta/Elev= 14
   -16.4   44.83    -6.4   44.83    -5.9   45.53    -3.4   46.73     -.4   46.73
       0   46.73     2.5   44.93     2.5   44.13     5.5   44.13     5.5   44.93
     7.5   46.43     8.6   46.43     9.3   45.73    19.3   45.73
#Mann= 3 , 0 , 0
   -16.4    .035       0       0    .035       0     7.5    .035       0
#XS Ineff= 2 , 0
               0      60     7.5              60
Permanent Ineff=
       F       F
#Block Obstruct= 2 , 0
                             7.5
Bank Sta=0,7.5
XS Rating Curve= 0
Exp/Cntr=.3,.1

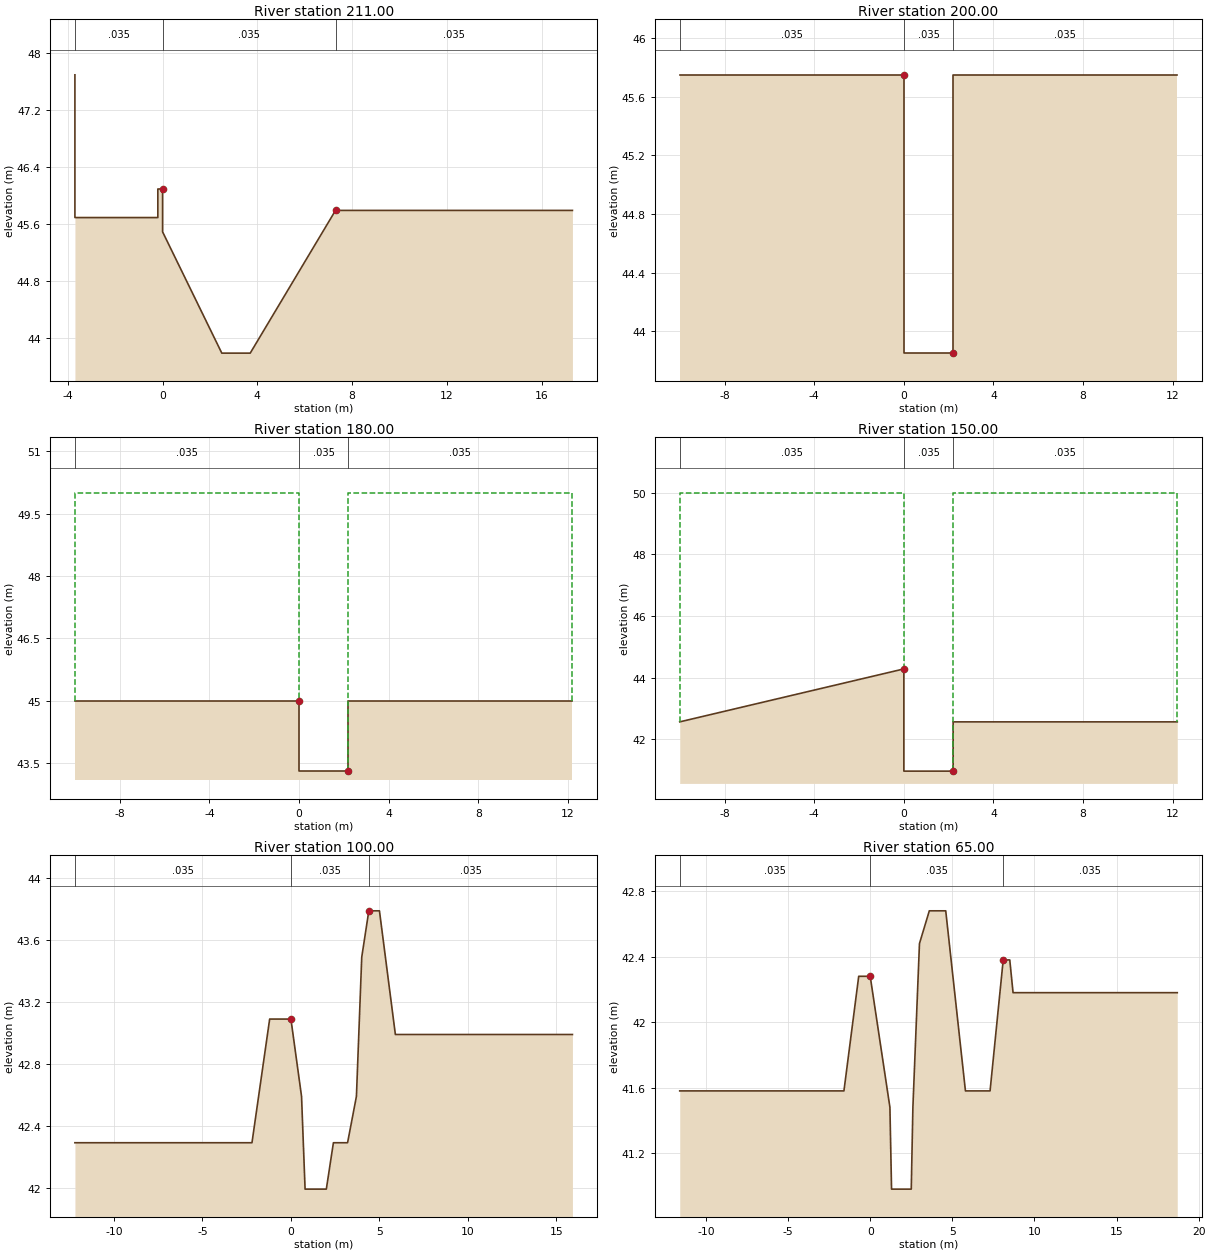
Type RM Length L Ch R = 1 ,211.00  ,11,11,11
BEGIN DESCRIPTION:
4.011
END DESCRIPTION:
#Sta/Elev= 10
    -3.7   47.69    -3.7   45.69     -.2   45.69     -.2   46.09       0   46.09
       0   45.49     2.5   43.79     3.7   43.79     7.3   45.79    17.3   45.79
#Mann= 3 , 0 , 0
    -3.7    .035       0       0    .035       0     7.3    .035       0
#XS Ineff= 2 , 0
               0      60     7.3              60
Permanent Ineff=
       F       F
#Block Obstruct= 2 , 0
                             7.3
Bank Sta=0,7.3
XS Rating Curve= 0
Exp/Cntr=.3,.1

Type RM Length L Ch R = 1 ,200.00  ,20,20,20
BEGIN DESCRIPTION:
4
END DESCRIPTION:
#Sta/Elev= 6
     -10   45.75       0   45.75       0   43.85     2.2   43.85     2.2   45.75
    12.2   45.75
#Mann= 3 , 0 , 0
     -10    .035       0       0    .035       0     2.2    .035       0
#XS Ineff= 2 , 0
               0      60     2.2              60
Permanent Ineff=
       F       F
#Block Obstruct= 2 , 0
                             2.2
Bank Sta=0,2.2
XS Rating Curve= 0
Exp/Cntr=.3,.1

Type RM Length L Ch R = 1 ,180.00  ,30,30,30
BEGIN DESCRIPTION:
3.03
END DESCRIPTION:
#Sta/Elev= 6
     -10      45       0      45       0    43.3     2.2    43.3     2.2      45
    12.2      45
#Mann= 3 , 0 , 0
     -10    .035       0       0    .035       0     2.2    .035       0
#XS Ineff= 2 , 0
               0      50     2.2              50
Permanent Ineff=
       F       F
#Block Obstruct= 2 , 0
                             2.2
Bank Sta=0,2.2
XS Rating Curve= 0
Exp/Cntr=.3,.1

Type RM Length L Ch R = 1 ,150.00  ,50,50,50
BEGIN DESCRIPTION:
3
END DESCRIPTION:
#Sta/Elev= 6
     -10   42.56       0   44.28       0   40.96     2.2   40.96     2.2   42.56
    12.2   42.56
#Mann= 3 , 0 , 0
     -10    .035       0       0    .035       0     2.2    .035       0
#XS Ineff= 2 , 0
               0      50     2.2              50
Permanent Ineff=
       F       F
#Block Obstruct= 2 , 0
                             2.2
Bank Sta=0,2.2
XS Rating Curve= 0
Exp/Cntr=.3,.1

Type RM Length L Ch R = 1 ,100.00  ,35,35,35
BEGIN DESCRIPTION:
2
END DESCRIPTION:
#Sta/Elev= 15
   -12.2   42.29    -2.2   42.29    -1.2   43.09       0   43.09      .6   42.59
      .8   41.99       2   41.99     2.4   42.29     3.2   42.29     3.7   42.59
       4   43.49     4.4   43.79       5   43.79     5.9   42.99    15.9   42.99
#Mann= 3 , 0 , 0
   -12.2    .035       0       0    .035       0     4.4    .035       0
#XS Ineff= 2 , 0
               0      50     4.4              50
Permanent Ineff=
       F       F
#Block Obstruct= 2 , 0
                             4.4
Bank Sta=0,4.4
XS Rating Curve= 0
Exp/Cntr=.3,.1

Type RM Length L Ch R = 1 ,65.00   ,15,15,15
BEGIN DESCRIPTION:
1.015
END DESCRIPTION:
#Sta/Elev= 17
   -11.6   41.58    -1.6   41.58     -.7   42.28       0   42.28     1.2   41.48
     1.3   40.98     2.5   40.98     2.6   41.48       3   42.48     3.6   42.68
     4.6   42.68     5.8   41.58     7.3   41.58     8.1   42.38     8.5   42.38
     8.7   42.18    18.7   42.18
#Mann= 3 , 0 , 0
   -11.6    .035       0       0    .035       0     8.1    .035       0
#XS Ineff= 2 , 0
               0      50     8.1              50
Permanent Ineff=
       F       F
#Block Obstruct= 2 , 0
                             8.1
Bank Sta=0,8.1
XS Rating Curve= 0
Exp/Cntr=.3,.1

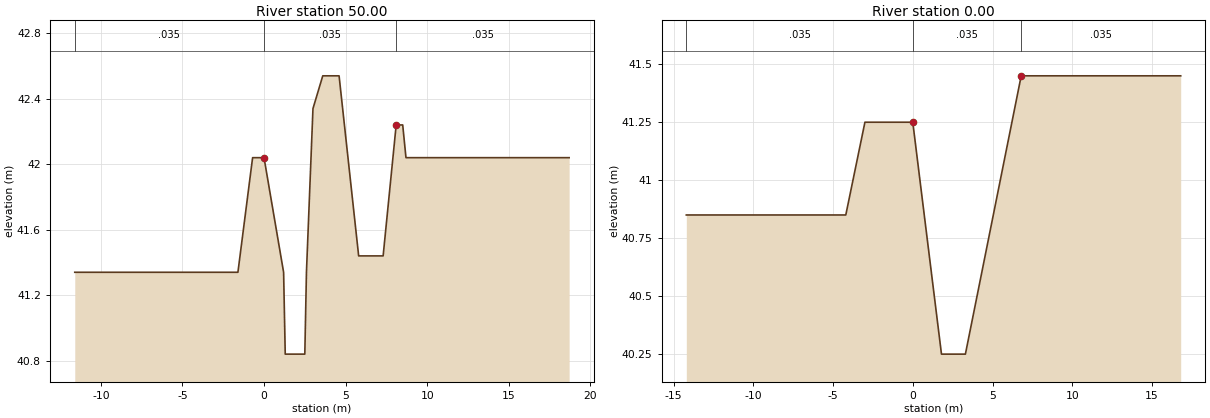
Type RM Length L Ch R = 1 ,50.00   ,50,50,50
BEGIN DESCRIPTION:
1
END DESCRIPTION:
#Sta/Elev= 17
   -11.6   41.34    -1.6   41.34     -.7   42.04       0   42.04     1.2   41.34
     1.3   40.84     2.5   40.84     2.6   41.34       3   42.34     3.6   42.54
     4.6   42.54     5.8   41.44     7.3   41.44     8.1   42.24     8.5   42.24
     8.7   42.04    18.7   42.04
#Mann= 3 , 0 , 0
   -11.6    .035       0       0    .035       0     8.1    .035       0
#XS Ineff= 2 , 0
               0      50     8.1              50
Permanent Ineff=
       F       F
#Block Obstruct= 2 , 0
                             8.1
Bank Sta=0,8.1
XS Rating Curve= 0
Exp/Cntr=.3,.1

Type RM Length L Ch R = 1 ,0.00    ,0,0,0
BEGIN DESCRIPTION:
0
END DESCRIPTION:
#Sta/Elev= 8
   -14.2   40.85    -4.2   40.85      -3   41.25       0   41.25     1.8   40.25
     3.3   40.25     6.8   41.45    16.8   41.45
#Mann= 3 , 0 , 0
   -14.2    .035       0       0    .035       0     6.8    .035       0
#XS Ineff= 2 , 0
               0      50     6.8              50
Permanent Ineff=
       F       F
#Block Obstruct= 2 , 0
                             6.8
Bank Sta=0,6.8
XS Rating Curve= 0
Exp/Cntr=.3,.1

Chan Stop Cuts=-1