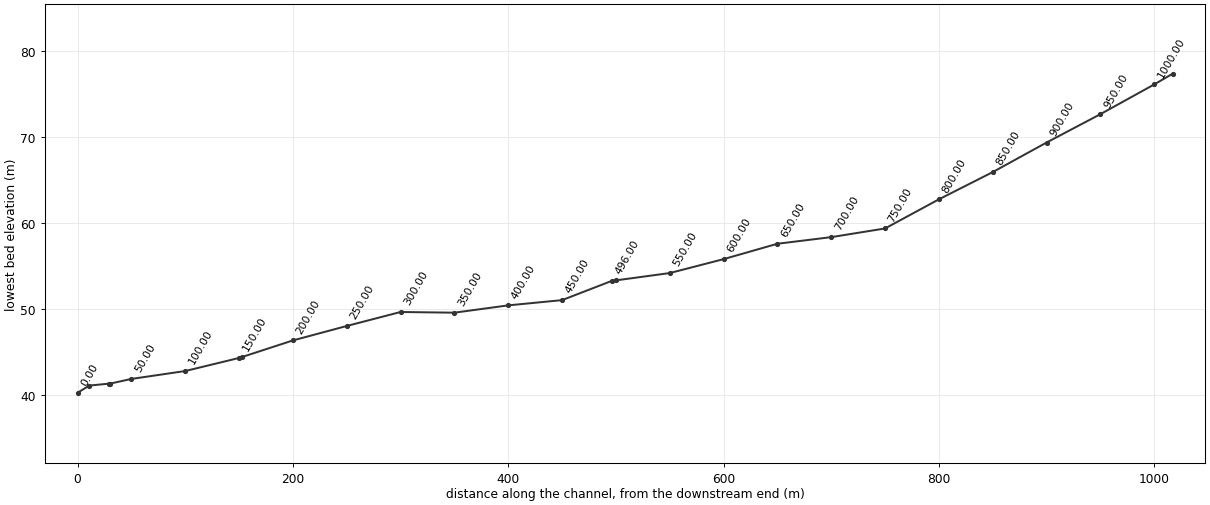
--- BUR.prj (project) ---

Proj Title=BUR
Current Plan=p01
Default Exp/Contr=.3,.1
SI Units
Geom File=g01
Flow File=f01
Plan File=p01
Y Axis Title=Elevation
X Axis Title(PF)=Main Channel Distance
X Axis Title(XS)=Station
BEGIN DESCRIPTION:
           BACK WATER COMPUTATION
      APPLICATION OF HEC-2 BY Samju Construction Engineering
    beadulgol-ch: 10,20,30,50,80 yr
END DESCRIPTION:
DSS Export Rating Curves= 0
DSS Export Rating Curve Sorted= 0
DSS Export Volume Flow Curves= 0
DXF OffsetX= 0
DXF OffsetY= 0
DXF ScaleX= 1
DXF ScaleY= 10

--- BUR.p01 (plan) ---

Plan Title=Imported Plan 01
Version=Version 3.0.1  Mar 2001
Short Identifier=Imported Pla
Geom File=g01
Flow File=f01
Subcritical Flow
K Sum by GR= 0
Std Step Tol= 0.003
Critical Tol= 0.003
Num of Std Step Trials= 20
Max Error Tol= 0.1
Flow Tol Ratio= 0.001
Split Flow NTrial= 30
Split Flow Tol= 0.02
Split Flow Ratio= 0.02
Log Output Level= 0
Friction Slope Method= 1
Unsteady Friction Slope Method= 2
Parabolic Critical Depth
Global Vel Dist= 0 , 0 , 0
Global Log Level= 0
CheckData=True
Encroach Param=-1 ,0,0, 0
Computation Interval=1HOUR
Output Interval=1HOUR
Run HTab= 0
Run UNet= 0
Run PostProcess= 0
UNET Theta= 1
UNET ZTol= 0.02
UNET ZSATol= 0.1
UNET MxIter= 20
UNET MaxInSteps= 20
UNET DtIC= 0
UNET DtMin= 0
UNET MaxCRTS= 20
UNET WFStab= 2
UNET SFStab= 1
UNET WFX= 1
UNET SFX= 1
UNET Convert EG Bridges=-1
UNET Use Existing IB Tables=-1
Instantaneous Interval=1HOUR
Write IC File= 0
Write Velocity= 0
Write Detailed= 0

--- BUR.f01 (steady flow) ---

Flow Title=Imported Flow 01
Version=Version 3.0.1  Mar 2001
Number of Profiles= 5
Profile Names=10YR,20YR,30YR,50YR,80YR
River Rch & RM=RIVER-1,Reach-1         ,1017.00
    7.33    8.07    8.51    9.06    9.56
Boundary for River Rch & Prof#=RIVER-1,Reach-1         , 1
Up Type= 0
Dn Type= 3
Dn Slope=.048
Boundary for River Rch & Prof#=RIVER-1,Reach-1         , 2
Up Type= 0
Dn Type= 3
Dn Slope=.048
Boundary for River Rch & Prof#=RIVER-1,Reach-1         , 3
Up Type= 0
Dn Type= 3
Dn Slope=.048
Boundary for River Rch & Prof#=RIVER-1,Reach-1         , 4
Up Type= 0
Dn Type= 3
Dn Slope=.048
Boundary for River Rch & Prof#=RIVER-1,Reach-1         , 5
Up Type= 0
Dn Type= 3
Dn Slope=.048
DSS Import GetInterval= 0
DSS Import GetPeak= 0
DSS Import FillOption= 0

--- BUR.g01 (geometry) ---

Geom Title=Imported Geom 01
Version=Version 3.0.1  Mar 2001

River Reach=RIVER-1         ,Reach-1
Reach XY= 2
              .5             .95              .5             .05

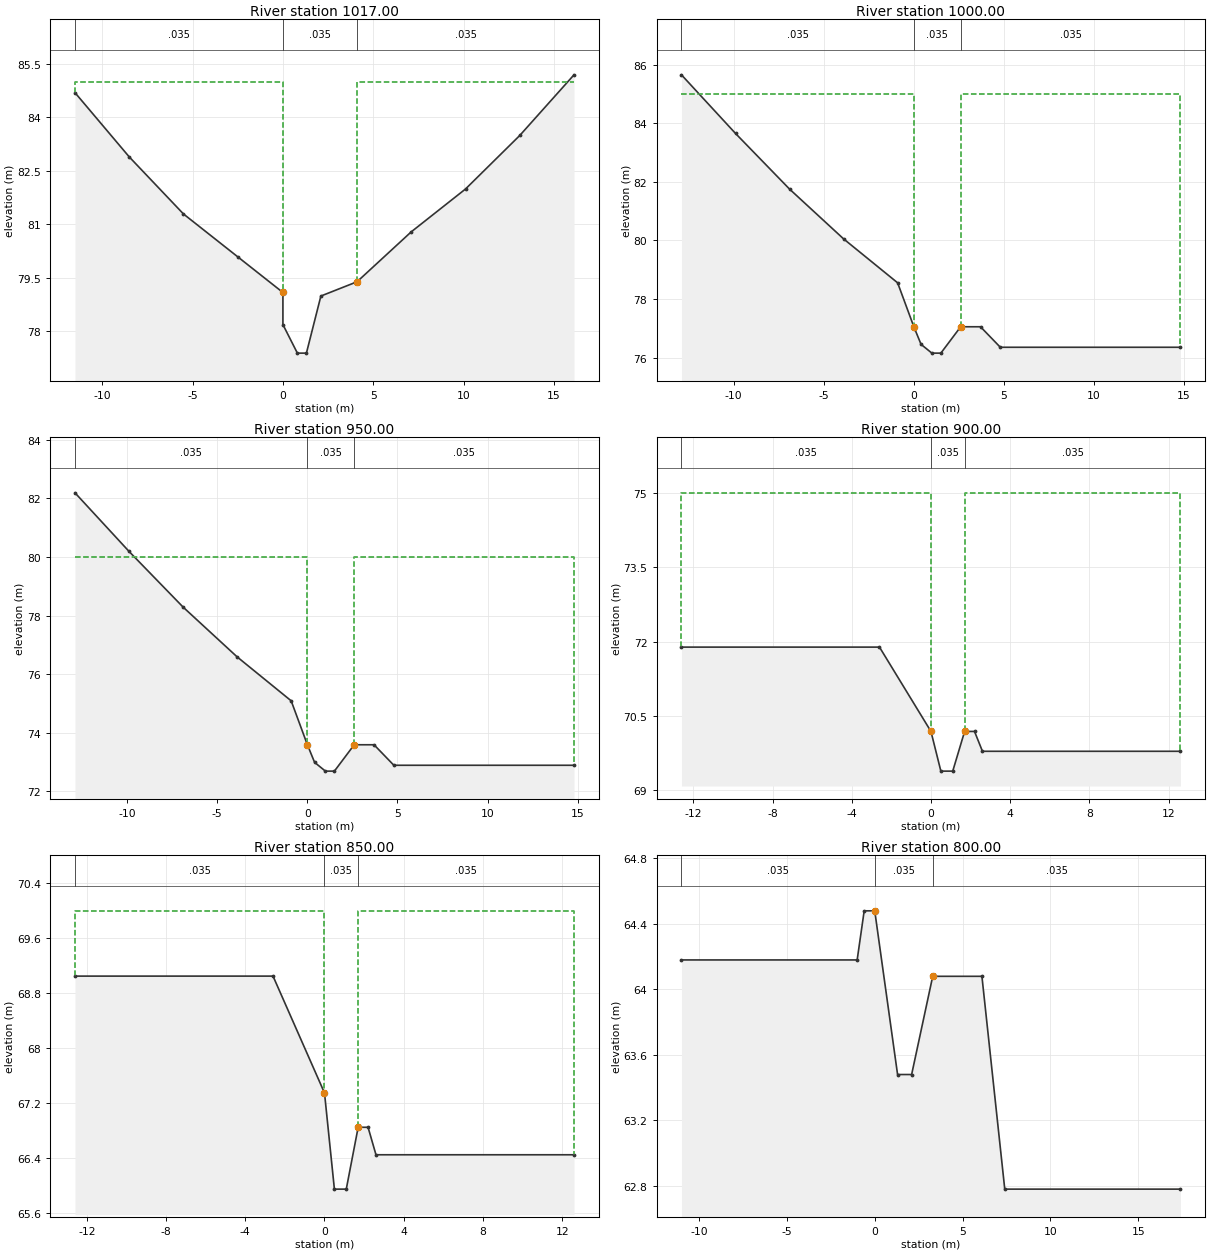
Type RM Length L Ch R = 1 ,1017.00 ,17,17,17
BEGIN DESCRIPTION:
20.017
END DESCRIPTION:
#Sta/Elev= 14
   -11.5   84.69    -8.5   82.89    -5.5   81.29    -2.5   80.09       0   79.09
       0   78.19      .8   77.39     1.3   77.39     2.1   78.99     4.1   79.39
     7.1   80.79    10.1   81.99    13.1   83.49    16.1   85.19
#Mann= 3 , 0 , 0
   -11.5    .035       0       0    .035       0     4.1    .035       0
#XS Ineff= 2 , 0
               0      85     4.1              85
Permanent Ineff=
       F       F
#Block Obstruct= 2 , 0
                             4.1
Bank Sta=0,4.1
XS Rating Curve= 0
Exp/Cntr=.3,.1

Type RM Length L Ch R = 1 ,1000.00 ,50,50,50
BEGIN DESCRIPTION:
20
END DESCRIPTION:
#Sta/Elev= 13
   -12.9   85.65    -9.9   83.65    -6.9   81.75    -3.9   80.05     -.9   78.55
       0   77.05      .4   76.45       1   76.15     1.5   76.15     2.6   77.05
     3.7   77.05     4.8   76.35    14.8   76.35
#Mann= 3 , 0 , 0
   -12.9    .035       0       0    .035       0     2.6    .035       0
#XS Ineff= 2 , 0
               0      85     2.6              85
Permanent Ineff=
       F       F
#Block Obstruct= 2 , 0
                             2.6
Bank Sta=0,2.6
XS Rating Curve= 0
Exp/Cntr=.3,.1

Type RM Length L Ch R = 1 ,950.00  ,50,50,50
BEGIN DESCRIPTION:
19
END DESCRIPTION:
#Sta/Elev= 13
   -12.9   82.19    -9.9   80.19    -6.9   78.29    -3.9   76.59     -.9   75.09
       0   73.59      .4   72.99       1   72.69     1.5   72.69     2.6   73.59
     3.7   73.59     4.8   72.89    14.8   72.89
#Mann= 3 , 0 , 0
   -12.9    .035       0       0    .035       0     2.6    .035       0
#XS Ineff= 2 , 0
               0      80     2.6              80
Permanent Ineff=
       F       F
#Block Obstruct= 2 , 0
                             2.6
Bank Sta=0,2.6
XS Rating Curve= 0
Exp/Cntr=.3,.1

Type RM Length L Ch R = 1 ,900.00  ,50,50,50
BEGIN DESCRIPTION:
18
END DESCRIPTION:
#Sta/Elev= 9
   -12.6   71.89    -2.6   71.89       0   70.19      .5   69.39     1.1   69.39
     1.7   70.19     2.2   70.19     2.6   69.79    12.6   69.79
#Mann= 3 , 0 , 0
   -12.6    .035       0       0    .035       0     1.7    .035       0
#XS Ineff= 2 , 0
               0      75     1.7              75
Permanent Ineff=
       F       F
#Block Obstruct= 2 , 0
                             1.7
Bank Sta=0,1.7
XS Rating Curve= 0
Exp/Cntr=.3,.1

Type RM Length L Ch R = 1 ,850.00  ,50,50,50
BEGIN DESCRIPTION:
17
END DESCRIPTION:
#Sta/Elev= 9
   -12.6   69.05    -2.6   69.05       0   67.35      .5   65.95     1.1   65.95
     1.7   66.85     2.2   66.85     2.6   66.45    12.6   66.45
#Mann= 3 , 0 , 0
   -12.6    .035       0       0    .035       0     1.7    .035       0
#XS Ineff= 2 , 0
               0      70     1.7              70
Permanent Ineff=
       F       F
#Block Obstruct= 2 , 0
                             1.7
Bank Sta=0,1.7
XS Rating Curve= 0
Exp/Cntr=.3,.1

Type RM Length L Ch R = 1 ,800.00  ,50,50,50
BEGIN DESCRIPTION:
16
END DESCRIPTION:
#Sta/Elev= 10
     -11   64.18      -1   64.18     -.6   64.48       0   64.48     1.3   63.48
     2.1   63.48     3.3   64.08     6.1   64.08     7.4   62.78    17.4   62.78
#Mann= 3 , 0 , 0
     -11    .035       0       0    .035       0     3.3    .035       0
#XS Ineff= 2 , 0
               0      70     3.3              70
Permanent Ineff=
       F       F
#Block Obstruct= 2 , 0
                             3.3
Bank Sta=0,3.3
XS Rating Curve= 0
Exp/Cntr=.3,.1

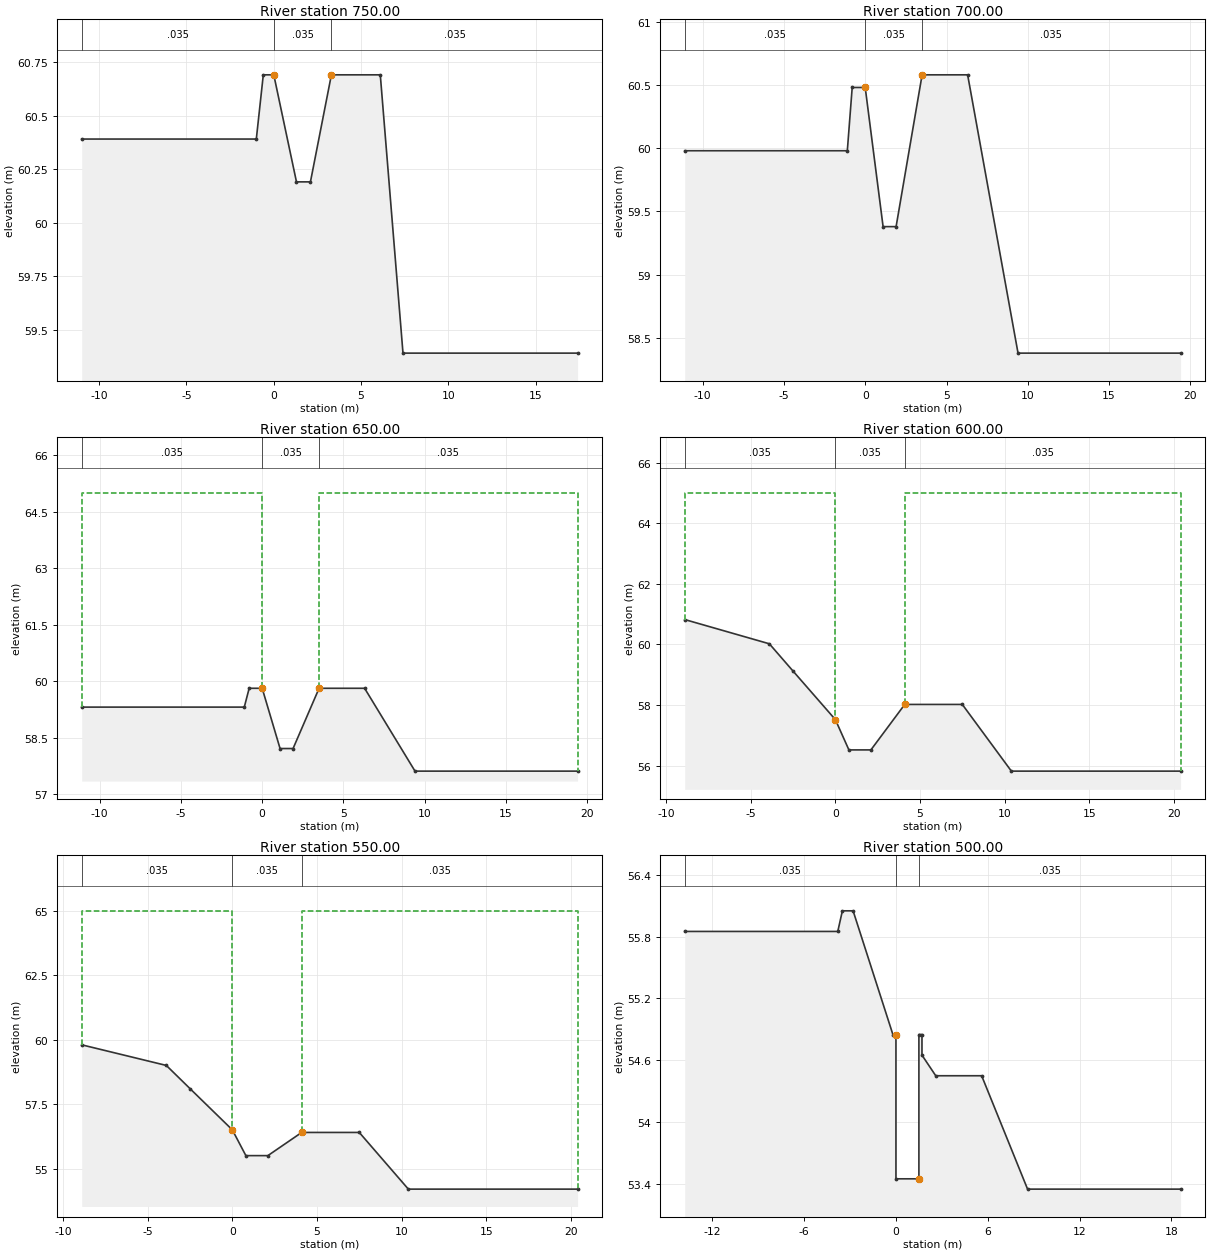
Type RM Length L Ch R = 1 ,750.00  ,50,50,50
BEGIN DESCRIPTION:
15
END DESCRIPTION:
#Sta/Elev= 10
     -11   60.39      -1   60.39     -.6   60.69       0   60.69     1.3   60.19
     2.1   60.19     3.3   60.69     6.1   60.69     7.4   59.39    17.4   59.39
#Mann= 3 , 0 , 0
     -11    .035       0       0    .035       0     3.3    .035       0
#XS Ineff= 2 , 0
               0      70     3.3              70
Permanent Ineff=
       F       F
#Block Obstruct= 2 , 0
                             3.3
Bank Sta=0,3.3
XS Rating Curve= 0
Exp/Cntr=.3,.1

Type RM Length L Ch R = 1 ,700.00  ,50,50,50
BEGIN DESCRIPTION:
14
END DESCRIPTION:
#Sta/Elev= 10
   -11.1   59.98    -1.1   59.98     -.8   60.48       0   60.48     1.1   59.38
     1.9   59.38     3.5   60.58     6.3   60.58     9.4   58.38    19.4   58.38
#Mann= 3 , 0 , 0
   -11.1    .035       0       0    .035       0     3.5    .035       0
#XS Ineff= 2 , 0
               0      70     3.5              70
Permanent Ineff=
       F       F
#Block Obstruct= 2 , 0
                             3.5
Bank Sta=0,3.5
XS Rating Curve= 0
Exp/Cntr=.3,.1

Type RM Length L Ch R = 1 ,650.00  ,50,50,50
BEGIN DESCRIPTION:
13
END DESCRIPTION:
#Sta/Elev= 10
   -11.1   59.31    -1.1   59.31     -.8   59.81       0   59.81     1.1   58.21
     1.9   58.21     3.5   59.81     6.3   59.81     9.4   57.61    19.4   57.61
#Mann= 3 , 0 , 0
   -11.1    .035       0       0    .035       0     3.5    .035       0
#XS Ineff= 2 , 0
               0      65     3.5              65
Permanent Ineff=
       F       F
#Block Obstruct= 2 , 0
                             3.5
Bank Sta=0,3.5
XS Rating Curve= 0
Exp/Cntr=.3,.1

Type RM Length L Ch R = 1 ,600.00  ,50,50,50
BEGIN DESCRIPTION:
12
END DESCRIPTION:
#Sta/Elev= 10
    -8.9   60.82    -3.9   60.02    -2.5   59.12       0   57.52      .8   56.52
     2.1   56.52     4.1   58.02     7.5   58.02    10.4   55.82    20.4   55.82
#Mann= 3 , 0 , 0
    -8.9    .035       0       0    .035       0     4.1    .035       0
#XS Ineff= 2 , 0
               0      65     4.1              65
Permanent Ineff=
       F       F
#Block Obstruct= 2 , 0
                             4.1
Bank Sta=0,4.1
XS Rating Curve= 0
Exp/Cntr=.3,.1

Type RM Length L Ch R = 1 ,550.00  ,50,50,50
BEGIN DESCRIPTION:
11
END DESCRIPTION:
#Sta/Elev= 10
    -8.9    59.8    -3.9      59    -2.5    58.1       0    56.5      .8    55.5
     2.1    55.5     4.1    56.4     7.5    56.4    10.4    54.2    20.4    54.2
#Mann= 3 , 0 , 0
    -8.9    .035       0       0    .035       0     4.1    .035       0
#XS Ineff= 2 , 0
               0      65     4.1              65
Permanent Ineff=
       F       F
#Block Obstruct= 2 , 0
                             4.1
Bank Sta=0,4.1
XS Rating Curve= 0
Exp/Cntr=.3,.1

Type RM Length L Ch R = 1 ,500.00  ,4,4,4
BEGIN DESCRIPTION:
10
END DESCRIPTION:
#Sta/Elev= 15
   -13.8   55.85    -3.8   55.85    -3.5   56.05    -2.8   56.05     -.2   54.85
       0   54.85       0   53.45     1.5   53.45     1.5   54.85     1.7   54.85
     1.7   54.65     2.6   54.45     5.6   54.45     8.6   53.35    18.6   53.35
#Mann= 3 , 0 , 0
   -13.8    .035       0       0    .035       0     1.5    .035       0
#XS Ineff= 2 , 0
               0      65     1.5              65
Permanent Ineff=
       F       F
#Block Obstruct= 2 , 0
                             1.5
Bank Sta=0,1.5
XS Rating Curve= 0
Exp/Cntr=.3,.1

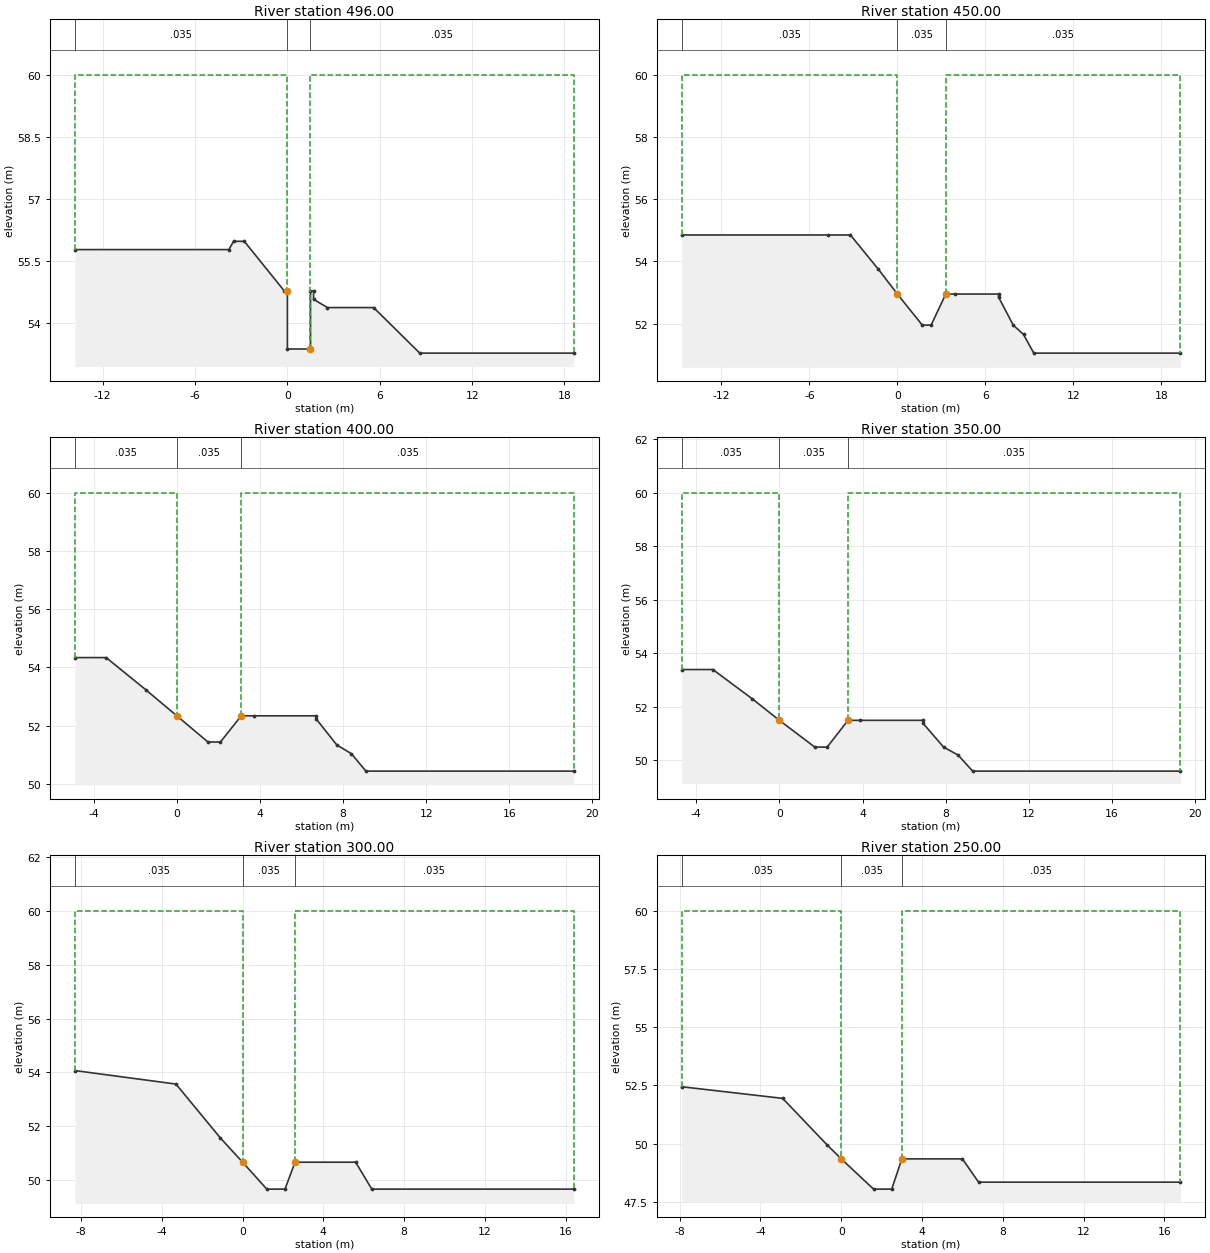
Type RM Length L Ch R = 1 ,496.00  ,46,46,46
BEGIN DESCRIPTION:
9.046
END DESCRIPTION:
#Sta/Elev= 15
   -13.8   55.78    -3.8   55.78    -3.5   55.98    -2.8   55.98     -.2   54.78
       0   54.78       0   53.38     1.5   53.38     1.5   54.78     1.7   54.78
     1.7   54.58     2.6   54.38     5.6   54.38     8.6   53.28    18.6   53.28
#Mann= 3 , 0 , 0
   -13.8    .035       0       0    .035       0     1.5    .035       0
#XS Ineff= 2 , 0
               0      60     1.5              60
Permanent Ineff=
       F       F
#Block Obstruct= 2 , 0
                             1.5
Bank Sta=0,1.5
XS Rating Curve= 0
Exp/Cntr=.3,.1

Type RM Length L Ch R = 1 ,450.00  ,50,50,50
BEGIN DESCRIPTION:
9
END DESCRIPTION:
#Sta/Elev= 15
   -14.7   54.85    -4.7   54.85    -3.2   54.85    -1.3   53.75       0   52.95
     1.7   51.95     2.3   51.95     3.3   52.95     3.9   52.95     6.9   52.95
     6.9   52.85     7.9   51.95     8.6   51.65     9.3   51.05    19.3   51.05
#Mann= 3 , 0 , 0
   -14.7    .035       0       0    .035       0     3.3    .035       0
#XS Ineff= 2 , 0
               0      60     3.3              60
Permanent Ineff=
       F       F
#Block Obstruct= 2 , 0
                             3.3
Bank Sta=0,3.3
XS Rating Curve= 0
Exp/Cntr=.3,.1

Type RM Length L Ch R = 1 ,400.00  ,50,50,50
BEGIN DESCRIPTION:
8
END DESCRIPTION:
#Sta/Elev= 14
    -4.9   54.34    -3.4   54.34    -1.5   53.24       0   52.34     1.5   51.44
     2.1   51.44     3.1   52.34     3.7   52.34     6.7   52.34     6.7   52.24
     7.7   51.34     8.4   51.04     9.1   50.44    19.1   50.44
#Mann= 3 , 0 , 0
    -4.9    .035       0       0    .035       0     3.1    .035       0
#XS Ineff= 2 , 0
               0      60     3.1              60
Permanent Ineff=
       F       F
#Block Obstruct= 2 , 0
                             3.1
Bank Sta=0,3.1
XS Rating Curve= 0
Exp/Cntr=.3,.1

Type RM Length L Ch R = 1 ,350.00  ,50,50,50
BEGIN DESCRIPTION:
7
END DESCRIPTION:
#Sta/Elev= 14
    -4.7   53.39    -3.2   53.39    -1.3   52.29       0   51.49     1.7   50.49
     2.3   50.49     3.3   51.49     3.9   51.49     6.9   51.49     6.9   51.39
     7.9   50.49     8.6   50.19     9.3   49.59    19.3   49.59
#Mann= 3 , 0 , 0
    -4.7    .035       0       0    .035       0     3.3    .035       0
#XS Ineff= 2 , 0
               0      60     3.3              60
Permanent Ineff=
       F       F
#Block Obstruct= 2 , 0
                             3.3
Bank Sta=0,3.3
XS Rating Curve= 0
Exp/Cntr=.3,.1

Type RM Length L Ch R = 1 ,300.00  ,50,50,50
BEGIN DESCRIPTION:
6
END DESCRIPTION:
#Sta/Elev= 10
    -8.3   54.07    -3.3   53.57    -1.1   51.57       0   50.67     1.2   49.67
     2.1   49.67     2.6   50.67     5.6   50.67     6.4   49.67    16.4   49.67
#Mann= 3 , 0 , 0
    -8.3    .035       0       0    .035       0     2.6    .035       0
#XS Ineff= 2 , 0
               0      60     2.6              60
Permanent Ineff=
       F       F
#Block Obstruct= 2 , 0
                             2.6
Bank Sta=0,2.6
XS Rating Curve= 0
Exp/Cntr=.3,.1

Type RM Length L Ch R = 1 ,250.00  ,50,50,50
BEGIN DESCRIPTION:
5
END DESCRIPTION:
#Sta/Elev= 10
    -7.9   52.44    -2.9   51.94     -.7   49.94       0   49.34     1.6   48.04
     2.5   48.04       3   49.34       6   49.34     6.8   48.34    16.8   48.34
#Mann= 3 , 0 , 0
    -7.9    .035       0       0    .035       0       3    .035       0
#XS Ineff= 2 , 0
               0      60       3              60
Permanent Ineff=
       F       F
#Block Obstruct= 2 , 0
                               3
Bank Sta=0,3
XS Rating Curve= 0
Exp/Cntr=.3,.1

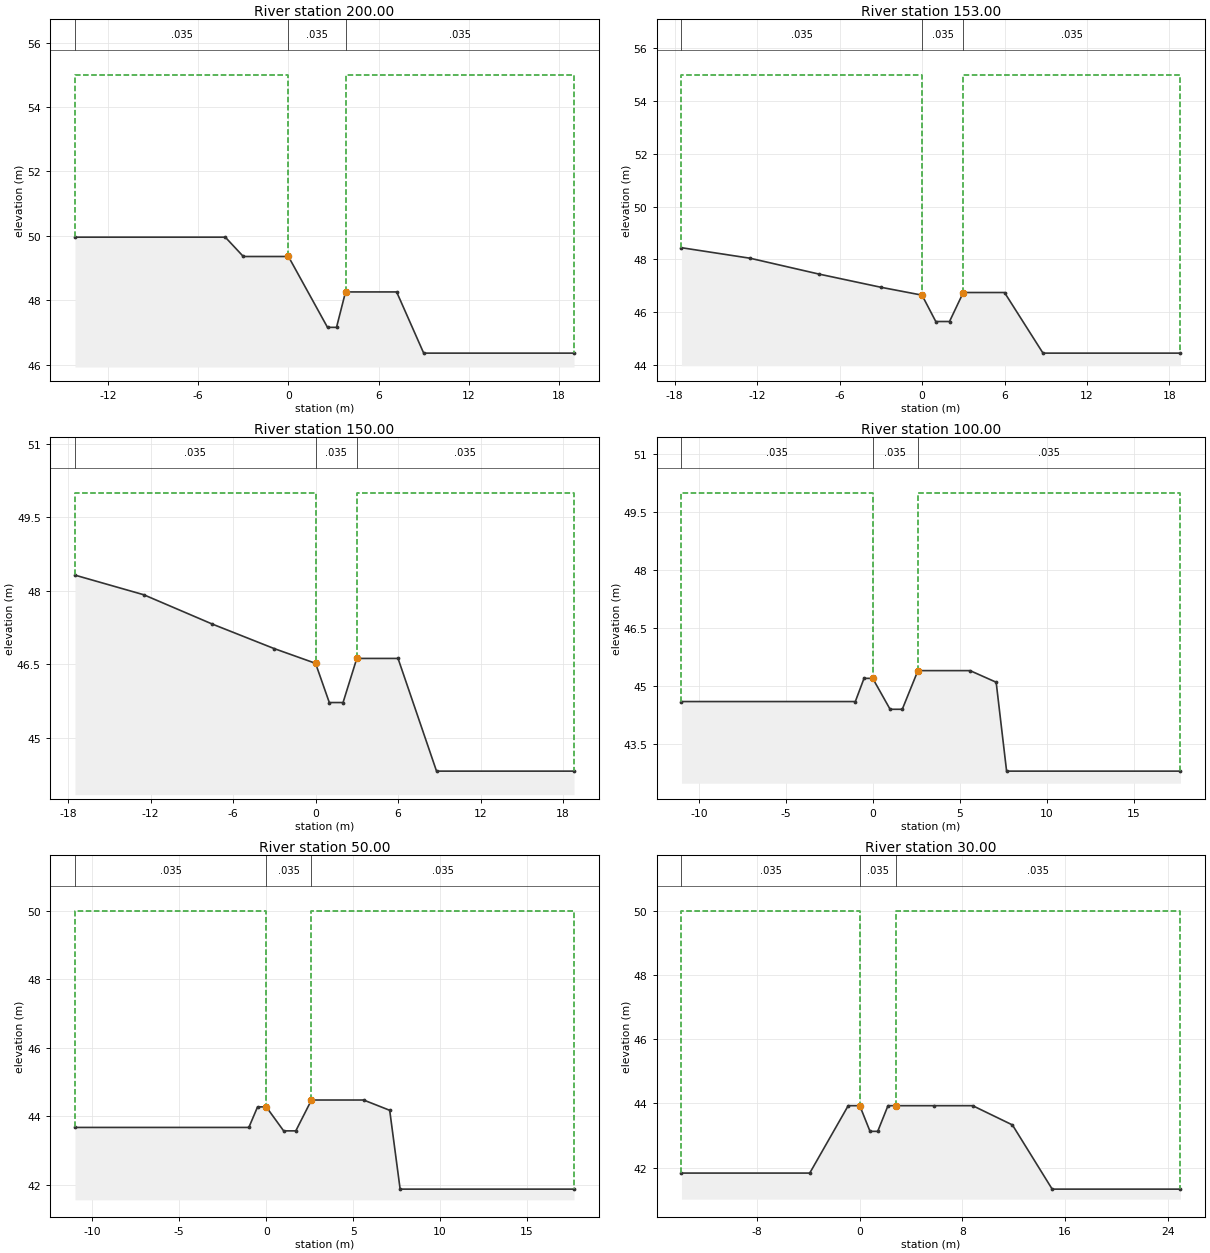
Type RM Length L Ch R = 1 ,200.00  ,47,47,47
BEGIN DESCRIPTION:
4
END DESCRIPTION:
#Sta/Elev= 10
   -14.2   49.96    -4.2   49.96      -3   49.36       0   49.36     2.6   47.16
     3.2   47.16     3.8   48.26     7.2   48.26       9   46.36      19   46.36
#Mann= 3 , 0 , 0
   -14.2    .035       0       0    .035       0     3.8    .035       0
#XS Ineff= 2 , 0
               0      55     3.8              55
Permanent Ineff=
       F       F
#Block Obstruct= 2 , 0
                             3.8
Bank Sta=0,3.8
XS Rating Curve= 0
Exp/Cntr=.3,.1

Type RM Length L Ch R = 1 ,153.00  ,3,3,3
BEGIN DESCRIPTION:
3.003
END DESCRIPTION:
#Sta/Elev= 11
   -17.5   48.44   -12.5   48.04    -7.5   47.44      -3   46.94       0   46.64
       1   45.64       2   45.64       3   46.74       6   46.74     8.8   44.44
    18.8   44.44
#Mann= 3 , 0 , 0
   -17.5    .035       0       0    .035       0       3    .035       0
#XS Ineff= 2 , 0
               0      55       3              55
Permanent Ineff=
       F       F
#Block Obstruct= 2 , 0
                               3
Bank Sta=0,3
XS Rating Curve= 0
Exp/Cntr=.3,.1

Type RM Length L Ch R = 1 ,150.00  ,50,50,50
BEGIN DESCRIPTION:
3
END DESCRIPTION:
#Sta/Elev= 11
   -17.5   48.32   -12.5   47.92    -7.5   47.32      -3   46.82       0   46.52
       1   45.72       2   45.72       3   46.62       6   46.62     8.8   44.32
    18.8   44.32
#Mann= 3 , 0 , 0
   -17.5    .035       0       0    .035       0       3    .035       0
#XS Ineff= 2 , 0
               0      50       3              50
Permanent Ineff=
       F       F
#Block Obstruct= 2 , 0
                               3
Bank Sta=0,3
XS Rating Curve= 0
Exp/Cntr=.3,.1

Type RM Length L Ch R = 1 ,100.00  ,50,50,50
BEGIN DESCRIPTION:
2
END DESCRIPTION:
#Sta/Elev= 11
     -11    44.6      -1    44.6     -.5    45.2       0    45.2       1    44.4
     1.7    44.4     2.6    45.4     5.6    45.4     7.1    45.1     7.7    42.8
    17.7    42.8
#Mann= 3 , 0 , 0
     -11    .035       0       0    .035       0     2.6    .035       0
#XS Ineff= 2 , 0
               0      50     2.6              50
Permanent Ineff=
       F       F
#Block Obstruct= 2 , 0
                             2.6
Bank Sta=0,2.6
XS Rating Curve= 0
Exp/Cntr=.3,.1

Type RM Length L Ch R = 1 ,50.00   ,20,20,20
BEGIN DESCRIPTION:
1
END DESCRIPTION:
#Sta/Elev= 11
     -11   43.68      -1   43.68     -.5   44.28       0   44.28       1   43.58
     1.7   43.58     2.6   44.48     5.6   44.48     7.1   44.18     7.7   41.88
    17.7   41.88
#Mann= 3 , 0 , 0
     -11    .035       0       0    .035       0     2.6    .035       0
#XS Ineff= 2 , 0
               0      50     2.6              50
Permanent Ineff=
       F       F
#Block Obstruct= 2 , 0
                             2.6
Bank Sta=0,2.6
XS Rating Curve= 0
Exp/Cntr=.3,.1

Type RM Length L Ch R = 1 ,30.00   ,1,1,1
BEGIN DESCRIPTION:
0.03
END DESCRIPTION:
#Sta/Elev= 13
   -13.9   41.83    -3.9   41.83     -.9   43.93       0   43.93      .8   43.13
     1.4   43.13     2.2   43.93     2.8   43.93     5.8   43.93     8.8   43.93
    11.9   43.33      15   41.33      25   41.33
#Mann= 3 , 0 , 0
   -13.9    .035       0       0    .035       0     2.8    .035       0
#XS Ineff= 2 , 0
               0      50     2.8              50
Permanent Ineff=
       F       F
#Block Obstruct= 2 , 0
                             2.8
Bank Sta=0,2.8
XS Rating Curve= 0
Exp/Cntr=.3,.1

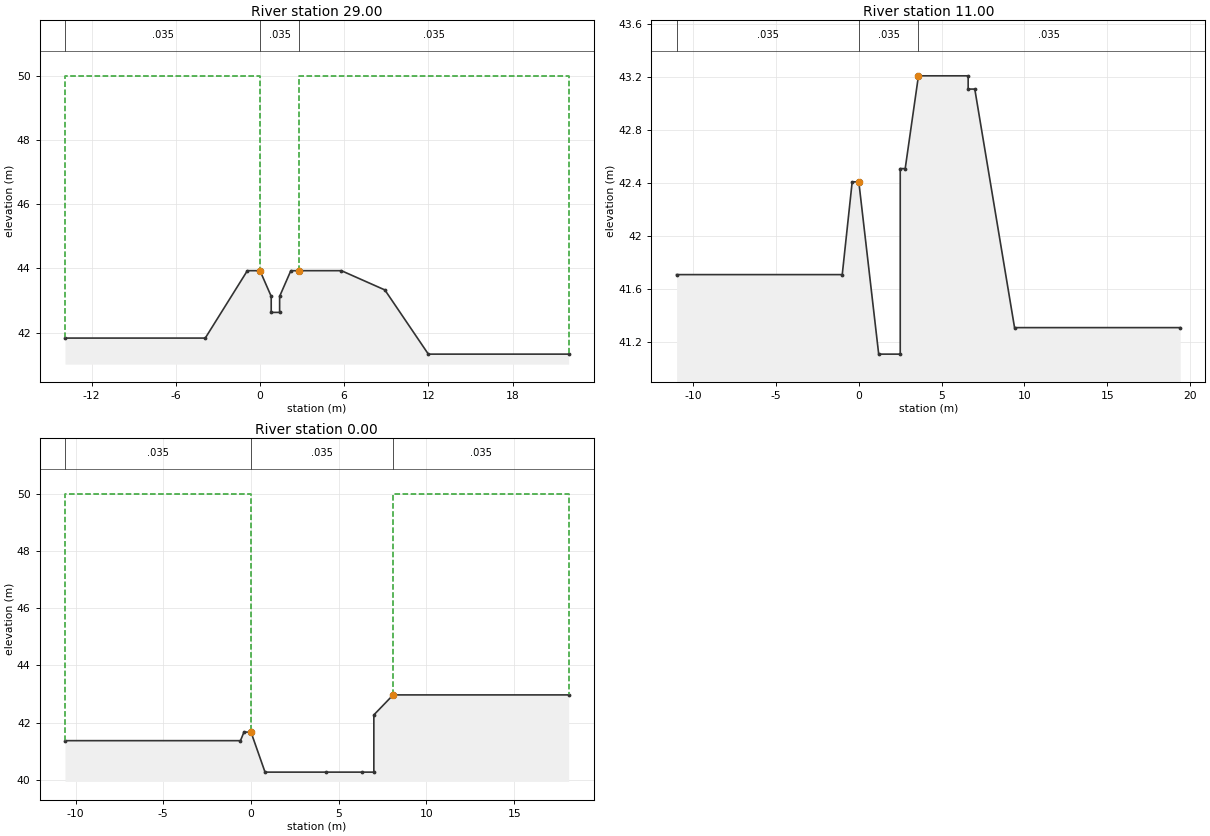
Type RM Length L Ch R = 1 ,29.00   ,18,18,18
BEGIN DESCRIPTION:
0.029
END DESCRIPTION:
#Sta/Elev= 14
   -13.9   41.83    -3.9   41.83     -.9   43.93       0   43.93      .8   43.13
      .8   42.63     1.4   42.63     1.4   43.13     2.2   43.93     2.8   43.93
     5.8   43.93     8.9   43.33      12   41.33      22   41.33
#Mann= 3 , 0 , 0
   -13.9    .035       0       0    .035       0     2.8    .035       0
#XS Ineff= 2 , 0
               0      50     2.8              50
Permanent Ineff=
       F       F
#Block Obstruct= 2 , 0
                             2.8
Bank Sta=0,2.8
XS Rating Curve= 0
Exp/Cntr=.3,.1

Type RM Length L Ch R = 1 ,11.00   ,11,11,11
BEGIN DESCRIPTION:
0.011
END DESCRIPTION:
#Sta/Elev= 14
     -11   41.71      -1   41.71     -.4   42.41       0   42.41     1.2   41.11
     2.5   41.11     2.5   42.51     2.8   42.51     3.6   43.21     6.6   43.21
     6.6   43.11       7   43.11     9.4   41.31    19.4   41.31
#Mann= 3 , 0 , 0
     -11    .035       0       0    .035       0     3.6    .035       0
#XS Ineff= 2 , 0
               0      50     3.6              50
Permanent Ineff=
       F       F
#Block Obstruct= 2 , 0
                             3.6
Bank Sta=0,3.6
XS Rating Curve= 0
Exp/Cntr=.3,.1

Type RM Length L Ch R = 1 ,0.00    ,0,0,0
BEGIN DESCRIPTION:
0
END DESCRIPTION:
#Sta/Elev= 11
   -10.6   41.37     -.6   41.37     -.4   41.67       0   41.67      .8   40.27
     4.3   40.27     6.3   40.27       7   40.27       7   42.27     8.1   42.97
    18.1   42.97
#Mann= 3 , 0 , 0
   -10.6    .035       0       0    .035       0     8.1    .035       0
#XS Ineff= 2 , 0
               0      50     8.1              50
Permanent Ineff=
       F       F
#Block Obstruct= 2 , 0
                             8.1
Bank Sta=0,8.1
XS Rating Curve= 0
Exp/Cntr=.3,.1

Chan Stop Cuts=-1