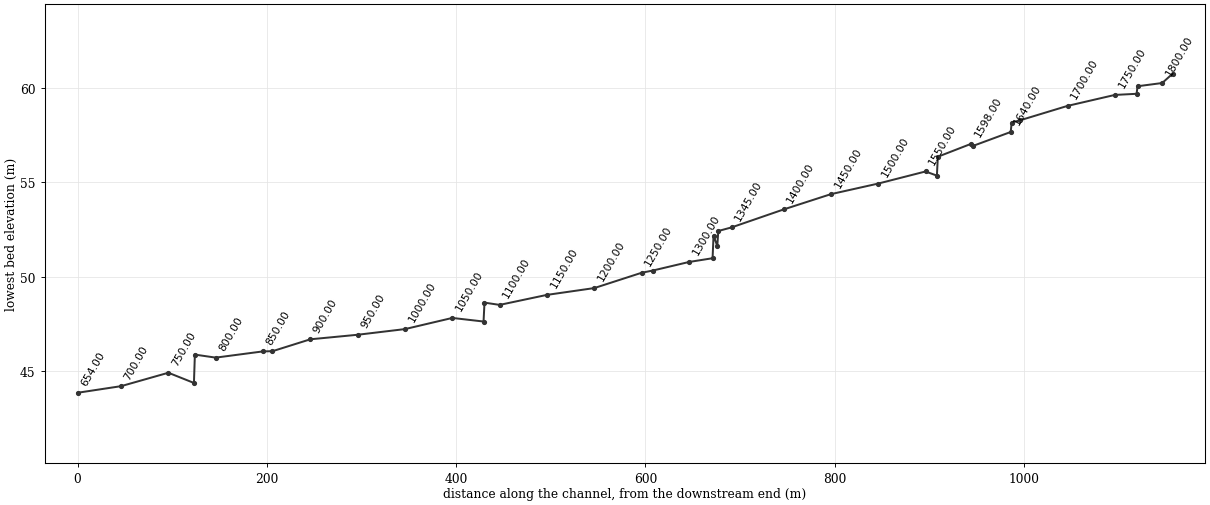
--- JANG.prj (project) ---

Proj Title=JANG
Current Plan=p01
Default Exp/Contr=.3,.1
SI Units
Geom File=g01
Flow File=f01
Plan File=p01
Y Axis Title=Elevation
X Axis Title(PF)=Main Channel Distance
X Axis Title(XS)=Station
BEGIN DESCRIPTION:
           BACK WATER COMPUTATION
      APPLICATION OF HEC-2 BY Samju Construction Engineering
      zanggoul-ch: 10,20,30,50,80 yr
END DESCRIPTION:
DSS Export Rating Curves= 0
DSS Export Rating Curve Sorted= 0
DSS Export Volume Flow Curves= 0
DXF OffsetX= 0
DXF OffsetY= 0
DXF ScaleX= 1
DXF ScaleY= 10

--- JANG.p01 (plan) ---

Plan Title=Imported Plan 01
Version=Version 3.0.1  Mar 2001
Short Identifier=Imported Pla
Geom File=g01
Flow File=f01
Subcritical Flow
K Sum by GR= 0
Std Step Tol= 0.003
Critical Tol= 0.003
Num of Std Step Trials= 20
Max Error Tol= 0.1
Flow Tol Ratio= 0.001
Split Flow NTrial= 30
Split Flow Tol= 0.02
Split Flow Ratio= 0.02
Log Output Level= 0
Friction Slope Method= 1
Unsteady Friction Slope Method= 2
Parabolic Critical Depth
Global Vel Dist= 0 , 0 , 0
Global Log Level= 0
CheckData=True
Encroach Param=-1 ,0,0, 0
Computation Interval=1HOUR
Output Interval=1HOUR
Run HTab= 0
Run UNet= 0
Run PostProcess= 0
UNET Theta= 1
UNET ZTol= 0.02
UNET ZSATol= 0.1
UNET MxIter= 20
UNET MaxInSteps= 20
UNET DtIC= 0
UNET DtMin= 0
UNET MaxCRTS= 20
UNET WFStab= 2
UNET SFStab= 1
UNET WFX= 1
UNET SFX= 1
UNET Convert EG Bridges=-1
UNET Use Existing IB Tables=-1
Instantaneous Interval=1HOUR
Write IC File= 0
Write Velocity= 0
Write Detailed= 0

--- JANG.f01 (steady flow) ---

Flow Title=Imported Flow 01
Version=Version 3.0.1  Mar 2001
Number of Profiles= 5
Profile Names=10YR,20YR,30YR,50YR,80YR
River Rch & RM=RIVER-1,Reach-1         ,1811.00
    26.8   29.54   31.13   33.15      35
Boundary for River Rch & Prof#=RIVER-1,Reach-1         , 1
Up Type= 0
Dn Type= 3
Dn Slope=.014
Boundary for River Rch & Prof#=RIVER-1,Reach-1         , 2
Up Type= 0
Dn Type= 3
Dn Slope=.014
Boundary for River Rch & Prof#=RIVER-1,Reach-1         , 3
Up Type= 0
Dn Type= 3
Dn Slope=.014
Boundary for River Rch & Prof#=RIVER-1,Reach-1         , 4
Up Type= 0
Dn Type= 3
Dn Slope=.014
Boundary for River Rch & Prof#=RIVER-1,Reach-1         , 5
Up Type= 0
Dn Type= 3
Dn Slope=.014
DSS Import GetInterval= 0
DSS Import GetPeak= 0
DSS Import FillOption= 0

--- JANG.g01 (geometry) ---

Geom Title=Imported Geom 01
Version=Version 3.0.1  Mar 2001

River Reach=RIVER-1         ,Reach-1
Reach XY= 2
              .5             .95              .5             .05

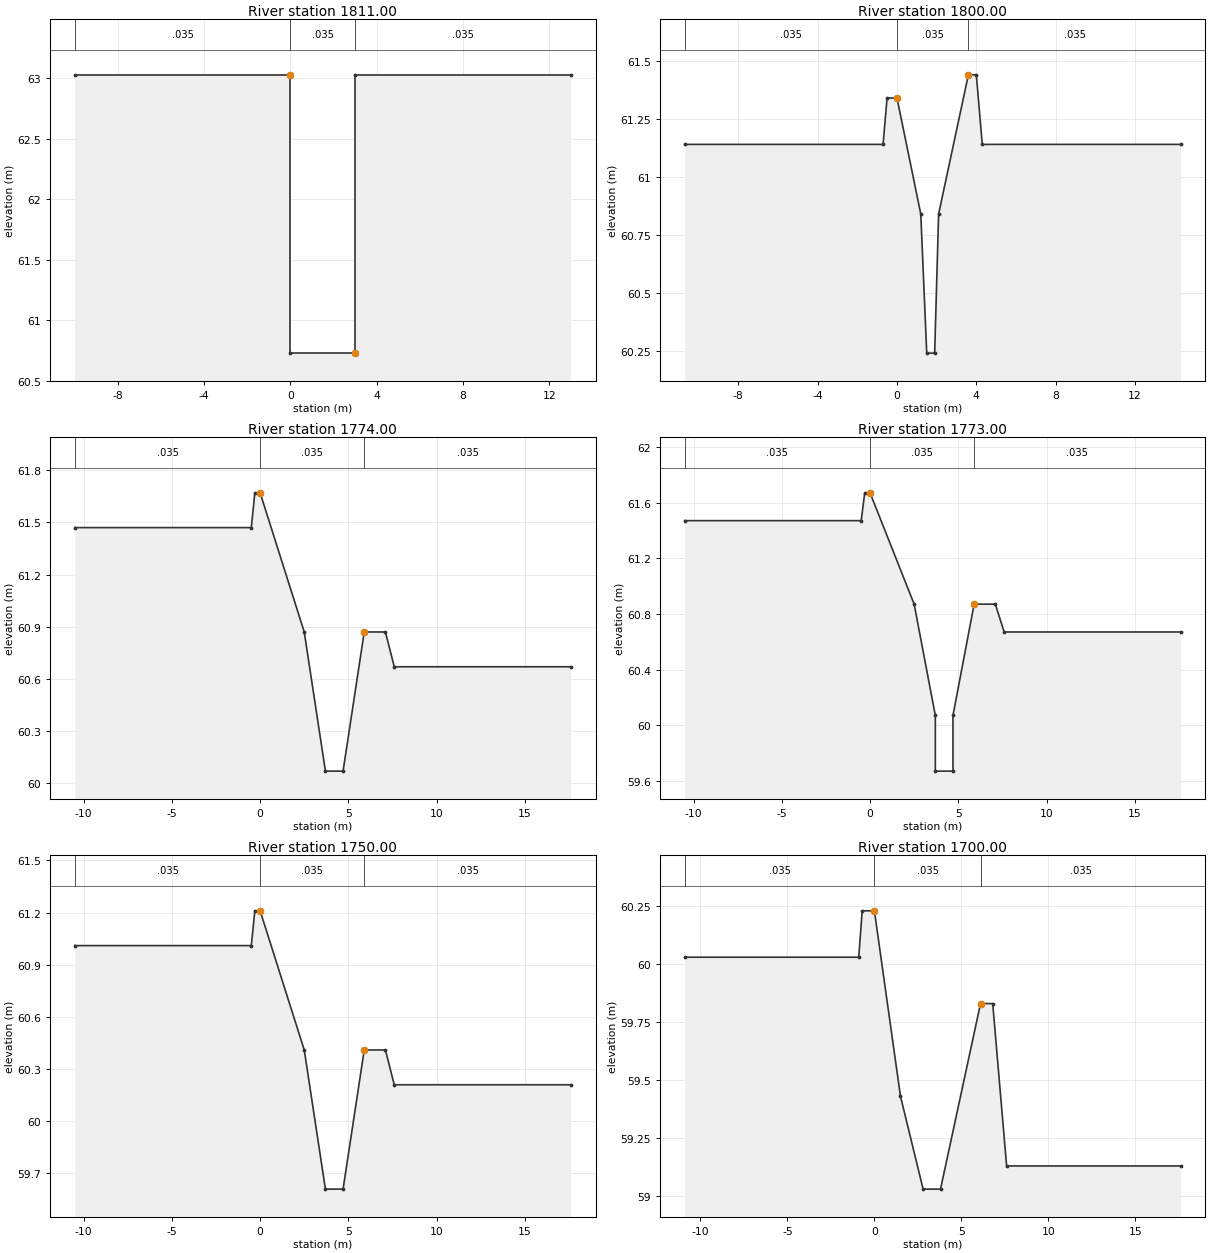
Type RM Length L Ch R = 1 ,1811.00 ,11,11,11
BEGIN DESCRIPTION:
36.011
END DESCRIPTION:
#Sta/Elev= 6
     -10   63.03       0   63.03       0   60.73       3   60.73       3   63.03
      13   63.03
#Mann= 3 , 0 , 0
     -10    .035       0       0    .035       0       3    .035       0
#XS Ineff= 2 , 0
               0      70       3              70
Permanent Ineff=
       F       F
#Block Obstruct= 2 , 0
                               3
Bank Sta=0,3
XS Rating Curve= 0
Exp/Cntr=.3,.1

Type RM Length L Ch R = 1 ,1800.00 ,26,26,26
BEGIN DESCRIPTION:
36
END DESCRIPTION:
#Sta/Elev= 12
   -10.7   61.14     -.7   61.14     -.5   61.34       0   61.34     1.2   60.84
     1.5   60.24     1.9   60.24     2.1   60.84     3.6   61.44       4   61.44
     4.3   61.14    14.3   61.14
#Mann= 3 , 0 , 0
   -10.7    .035       0       0    .035       0     3.6    .035       0
#XS Ineff= 2 , 0
               0      70     3.6              70
Permanent Ineff=
       F       F
#Block Obstruct= 2 , 0
                             3.6
Bank Sta=0,3.6
XS Rating Curve= 0
Exp/Cntr=.3,.1

Type RM Length L Ch R = 1 ,1774.00 ,1,1,1
BEGIN DESCRIPTION:
35.024
END DESCRIPTION:
#Sta/Elev= 11
   -10.5   61.47     -.5   61.47     -.3   61.67       0   61.67     2.5   60.87
     3.7   60.07     4.7   60.07     5.9   60.87     7.1   60.87     7.6   60.67
    17.6   60.67
#Mann= 3 , 0 , 0
   -10.5    .035       0       0    .035       0     5.9    .035       0
#XS Ineff= 2 , 0
               0      70     5.9              70
Permanent Ineff=
       F       F
#Block Obstruct= 2 , 0
                             5.9
Bank Sta=0,5.9
XS Rating Curve= 0
Exp/Cntr=.3,.1

Type RM Length L Ch R = 1 ,1773.00 ,23,23,23
BEGIN DESCRIPTION:
35.023
END DESCRIPTION:
#Sta/Elev= 13
   -10.5   61.47     -.5   61.47     -.3   61.67       0   61.67     2.5   60.87
     3.7   60.07     3.7   59.67     4.7   59.67     4.7   60.07     5.9   60.87
     7.1   60.87     7.6   60.67    17.6   60.67
#Mann= 3 , 0 , 0
   -10.5    .035       0       0    .035       0     5.9    .035       0
#XS Ineff= 2 , 0
               0      70     5.9              70
Permanent Ineff=
       F       F
#Block Obstruct= 2 , 0
                             5.9
Bank Sta=0,5.9
XS Rating Curve= 0
Exp/Cntr=.3,.1

Type RM Length L Ch R = 1 ,1750.00 ,50,50,50
BEGIN DESCRIPTION:
35
END DESCRIPTION:
#Sta/Elev= 11
   -10.5   61.01     -.5   61.01     -.3   61.21       0   61.21     2.5   60.41
     3.7   59.61     4.7   59.61     5.9   60.41     7.1   60.41     7.6   60.21
    17.6   60.21
#Mann= 3 , 0 , 0
   -10.5    .035       0       0    .035       0     5.9    .035       0
#XS Ineff= 2 , 0
               0      70     5.9              70
Permanent Ineff=
       F       F
#Block Obstruct= 2 , 0
                             5.9
Bank Sta=0,5.9
XS Rating Curve= 0
Exp/Cntr=.3,.1

Type RM Length L Ch R = 1 ,1700.00 ,50,50,50
BEGIN DESCRIPTION:
34
END DESCRIPTION:
#Sta/Elev= 11
   -10.9   60.03     -.9   60.03     -.7   60.23       0   60.23     1.5   59.43
     2.8   59.03     3.8   59.03     6.1   59.83     6.8   59.83     7.6   59.13
    17.6   59.13
#Mann= 3 , 0 , 0
   -10.9    .035       0       0    .035       0     6.1    .035       0
#XS Ineff= 2 , 0
               0      70     6.1              70
Permanent Ineff=
       F       F
#Block Obstruct= 2 , 0
                             6.1
Bank Sta=0,6.1
XS Rating Curve= 0
Exp/Cntr=.3,.1

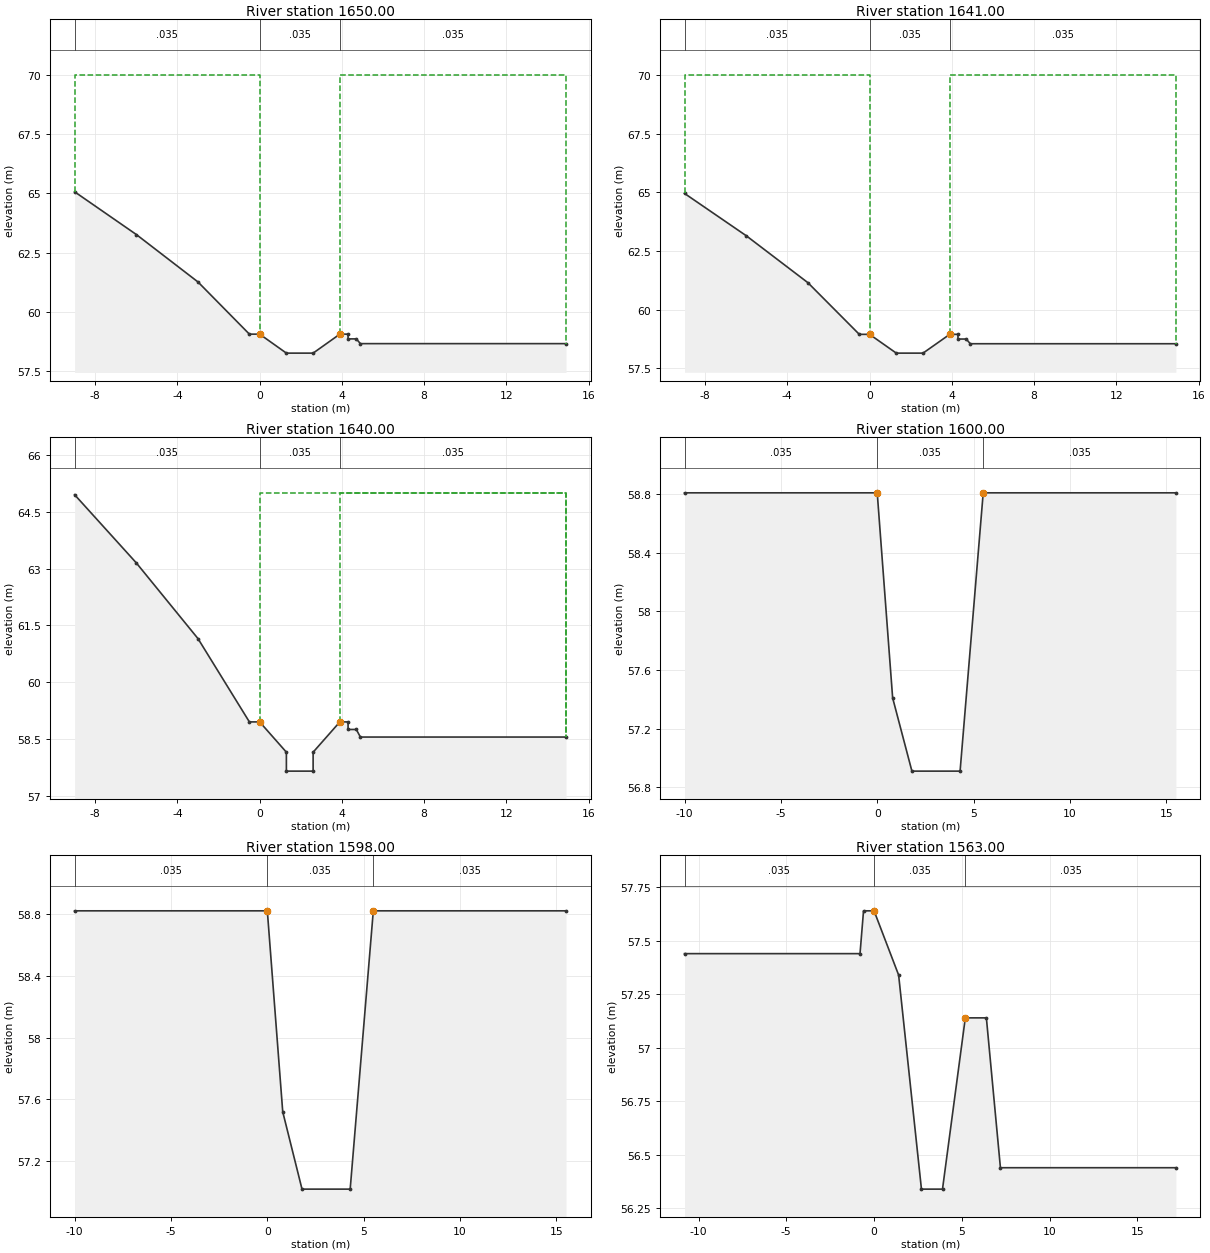
Type RM Length L Ch R = 1 ,1650.00 ,9,9,9
BEGIN DESCRIPTION:
33
END DESCRIPTION:
#Sta/Elev= 13
      -9   65.07      -6   63.27      -3   61.27     -.5   59.07       0   59.07
     1.3   58.27     2.6   58.27     3.9   59.07     4.3   59.07     4.3   58.87
     4.7   58.87     4.9   58.67    14.9   58.67
#Mann= 3 , 0 , 0
      -9    .035       0       0    .035       0     3.9    .035       0
#XS Ineff= 2 , 0
               0      70     3.9              70
Permanent Ineff=
       F       F
#Block Obstruct= 2 , 0
                             3.9
Bank Sta=0,3.9
XS Rating Curve= 0
Exp/Cntr=.3,.1

Type RM Length L Ch R = 1 ,1641.00 ,1,1,1
BEGIN DESCRIPTION:
32.041
END DESCRIPTION:
#Sta/Elev= 13
      -9   64.95      -6   63.15      -3   61.15     -.5   58.95       0   58.95
     1.3   58.15     2.6   58.15     3.9   58.95     4.3   58.95     4.3   58.75
     4.7   58.75     4.9   58.55    14.9   58.55
#Mann= 3 , 0 , 0
      -9    .035       0       0    .035       0     3.9    .035       0
#XS Ineff= 2 , 0
               0      70     3.9              70
Permanent Ineff=
       F       F
#Block Obstruct= 2 , 0
                             3.9
Bank Sta=0,3.9
XS Rating Curve= 0
Exp/Cntr=.3,.1

Type RM Length L Ch R = 1 ,1640.00 ,40,40,40
BEGIN DESCRIPTION:
32.04
END DESCRIPTION:
#Sta/Elev= 15
      -9   64.95      -6   63.15      -3   61.15     -.5   58.95       0   58.95
     1.3   58.15     1.3   57.65     2.6   57.65     2.6   58.15     3.9   58.95
     4.3   58.95     4.3   58.75     4.7   58.75     4.9   58.55    14.9   58.55
#Mann= 3 , 0 , 0
      -9    .035       0       0    .035       0     3.9    .035       0
#XS Ineff= 2 , 0
       0       0      65     3.9       0      65
Permanent Ineff=
       F       F
#Block Obstruct= 2 , 0
                             3.9
Bank Sta=0,3.9
XS Rating Curve= 0
Exp/Cntr=.3,.1

Type RM Length L Ch R = 1 ,1600.00 ,2,2,2
BEGIN DESCRIPTION:
32
END DESCRIPTION:
#Sta/Elev= 7
     -10   58.81       0   58.81      .8   57.41     1.8   56.91     4.3   56.91
     5.5   58.81    15.5   58.81
#Mann= 3 , 0 , 0
     -10    .035       0       0    .035       0     5.5    .035       0
#XS Ineff= 2 , 0
               0      65     5.5              65
Permanent Ineff=
       F       F
#Block Obstruct= 2 , 0
                             5.5
Bank Sta=0,5.5
XS Rating Curve= 0
Exp/Cntr=.3,.1

Type RM Length L Ch R = 1 ,1598.00 ,35,35,35
BEGIN DESCRIPTION:
31.048
END DESCRIPTION:
#Sta/Elev= 7
     -10   58.82       0   58.82      .8   57.52     1.8   57.02     4.3   57.02
     5.5   58.82    15.5   58.82
#Mann= 3 , 0 , 0
     -10    .035       0       0    .035       0     5.5    .035       0
#XS Ineff= 2 , 0
               0      65     5.5              65
Permanent Ineff=
       F       F
#Block Obstruct= 2 , 0
                             5.5
Bank Sta=0,5.5
XS Rating Curve= 0
Exp/Cntr=.3,.1

Type RM Length L Ch R = 1 ,1563.00 ,1,1,1
BEGIN DESCRIPTION:
31.013
END DESCRIPTION:
#Sta/Elev= 11
   -10.8   57.44     -.8   57.44     -.6   57.64       0   57.64     1.4   57.34
     2.7   56.34     3.9   56.34     5.2   57.14     6.4   57.14     7.2   56.44
    17.2   56.44
#Mann= 3 , 0 , 0
   -10.8    .035       0       0    .035       0     5.2    .035       0
#XS Ineff= 2 , 0
               0      65     5.2              65
Permanent Ineff=
       F       F
#Block Obstruct= 2 , 0
                             5.2
Bank Sta=0,5.2
XS Rating Curve= 0
Exp/Cntr=.3,.1

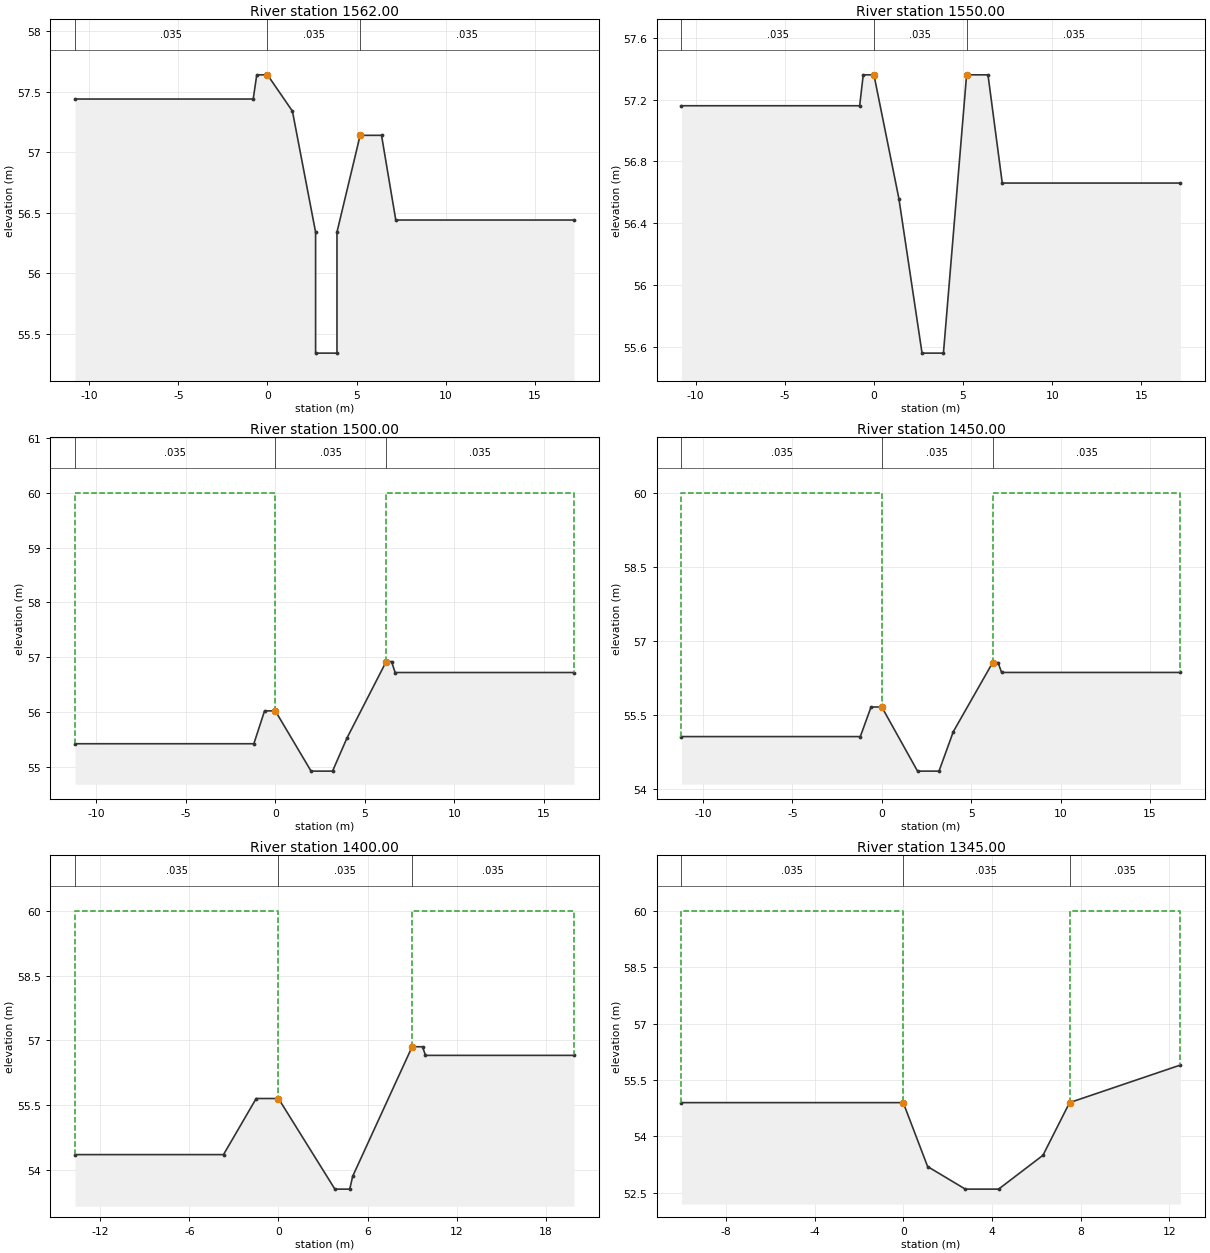
Type RM Length L Ch R = 1 ,1562.00 ,12,12,12
BEGIN DESCRIPTION:
31.012
END DESCRIPTION:
#Sta/Elev= 13
   -10.8   57.44     -.8   57.44     -.6   57.64       0   57.64     1.4   57.34
     2.7   56.34     2.7   55.34     3.9   55.34     3.9   56.34     5.2   57.14
     6.4   57.14     7.2   56.44    17.2   56.44
#Mann= 3 , 0 , 0
   -10.8    .035       0       0    .035       0     5.2    .035       0
#XS Ineff= 2 , 0
               0      65     5.2              65
Permanent Ineff=
       F       F
#Block Obstruct= 2 , 0
                             5.2
Bank Sta=0,5.2
XS Rating Curve= 0
Exp/Cntr=.3,.1

Type RM Length L Ch R = 1 ,1550.00 ,50,50,50
BEGIN DESCRIPTION:
31
END DESCRIPTION:
#Sta/Elev= 11
   -10.8   57.16     -.8   57.16     -.6   57.36       0   57.36     1.4   56.56
     2.7   55.56     3.9   55.56     5.2   57.36     6.4   57.36     7.2   56.66
    17.2   56.66
#Mann= 3 , 0 , 0
   -10.8    .035       0       0    .035       0     5.2    .035       0
#XS Ineff= 2 , 0
               0      65     5.2              65
Permanent Ineff=
       F       F
#Block Obstruct= 2 , 0
                             5.2
Bank Sta=0,5.2
XS Rating Curve= 0
Exp/Cntr=.3,.1

Type RM Length L Ch R = 1 ,1500.00 ,50,50,50
BEGIN DESCRIPTION:
30
END DESCRIPTION:
#Sta/Elev= 11
   -11.2   55.42    -1.2   55.42     -.6   56.02       0   56.02       2   54.92
     3.2   54.92       4   55.52     6.2   56.92     6.5   56.92     6.7   56.72
    16.7   56.72
#Mann= 3 , 0 , 0
   -11.2    .035       0       0    .035       0     6.2    .035       0
#XS Ineff= 2 , 0
               0      60     6.2              60
Permanent Ineff=
       F       F
#Block Obstruct= 2 , 0
                             6.2
Bank Sta=0,6.2
XS Rating Curve= 0
Exp/Cntr=.3,.1

Type RM Length L Ch R = 1 ,1450.00 ,50,50,50
BEGIN DESCRIPTION:
29
END DESCRIPTION:
#Sta/Elev= 11
   -11.2   55.06    -1.2   55.06     -.6   55.66       0   55.66       2   54.36
     3.2   54.36       4   55.16     6.2   56.56     6.5   56.56     6.7   56.36
    16.7   56.36
#Mann= 3 , 0 , 0
   -11.2    .035       0       0    .035       0     6.2    .035       0
#XS Ineff= 2 , 0
               0      60     6.2              60
Permanent Ineff=
       F       F
#Block Obstruct= 2 , 0
                             6.2
Bank Sta=0,6.2
XS Rating Curve= 0
Exp/Cntr=.3,.1

Type RM Length L Ch R = 1 ,1400.00 ,55,55,55
BEGIN DESCRIPTION:
28
END DESCRIPTION:
#Sta/Elev= 11
   -13.7   54.35    -3.7   54.35    -1.5   55.65       0   55.65     3.8   53.55
     4.8   53.55       5   53.85       9   56.85     9.7   56.85     9.9   56.65
    19.9   56.65
#Mann= 3 , 0 , 0
   -13.7    .035       0       0    .035       0       9    .035       0
#XS Ineff= 2 , 0
               0      60       9              60
Permanent Ineff=
       F       F
#Block Obstruct= 2 , 0
                               9
Bank Sta=0,9
XS Rating Curve= 0
Exp/Cntr=.3,.1

Type RM Length L Ch R = 1 ,1345.00 ,14,14,14
BEGIN DESCRIPTION:
26.045
END DESCRIPTION:
#Sta/Elev= 8
     -10    54.9       0    54.9     1.1    53.2     2.8    52.6     4.3    52.6
     6.3    53.5     7.5    54.9    12.5    55.9
#Mann= 3 , 0 , 0
     -10    .035       0       0    .035       0     7.5    .035       0
#XS Ineff= 2 , 0
               0      60     7.5              60
Permanent Ineff=
       F       F
#Block Obstruct= 2 , 0
                             7.5
Bank Sta=0,7.5
XS Rating Curve= 0
Exp/Cntr=.3,.1

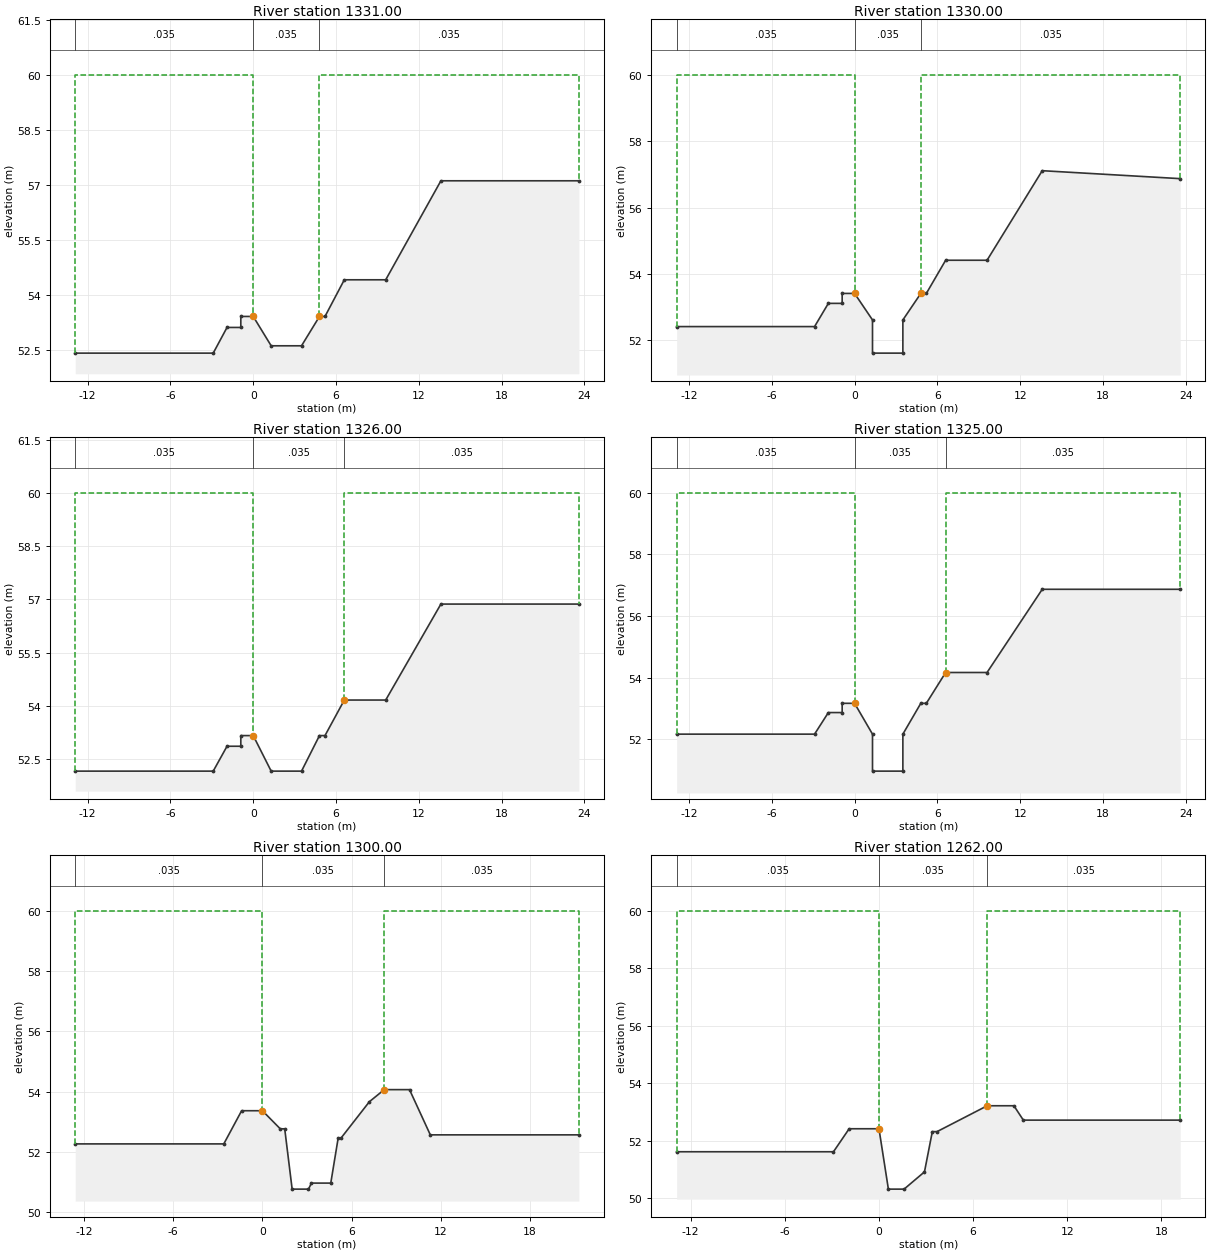
Type RM Length L Ch R = 1 ,1331.00 ,1,1,1
BEGIN DESCRIPTION:
26.031
END DESCRIPTION:
#Sta/Elev= 14
   -12.9   52.41    -2.9   52.41    -1.9   53.11     -.9   53.11     -.9   53.41
       0   53.41     1.3   52.61     3.5   52.61     4.8   53.41     5.2   53.41
     6.6   54.41     9.6   54.41    13.6   57.11    23.6   57.11
#Mann= 3 , 0 , 0
   -12.9    .035       0       0    .035       0     4.8    .035       0
#XS Ineff= 2 , 0
               0      60     4.8              60
Permanent Ineff=
       F       F
#Block Obstruct= 2 , 0
                             4.8
Bank Sta=0,4.8
XS Rating Curve= 0
Exp/Cntr=.3,.1

Type RM Length L Ch R = 1 ,1330.00 ,4,4,4
BEGIN DESCRIPTION:
26.03
END DESCRIPTION:
#Sta/Elev= 16
   -12.9   52.41    -2.9   52.41    -1.9   53.11     -.9   53.11     -.9   53.41
       0   53.41     1.3   52.61     1.3   51.61     3.5   51.61     3.5   52.61
     4.8   53.41     5.2   53.41     6.6   54.41     9.6   54.41    13.6   57.11
    23.6   56.87
#Mann= 3 , 0 , 0
   -12.9    .035       0       0    .035       0     4.8    .035       0
#XS Ineff= 2 , 0
               0      60     4.8              60
Permanent Ineff=
       F       F
#Block Obstruct= 2 , 0
                             4.8
Bank Sta=0,4.8
XS Rating Curve= 0
Exp/Cntr=.3,.1

Type RM Length L Ch R = 1 ,1326.00 ,1,1,1
BEGIN DESCRIPTION:
26.026
END DESCRIPTION:
#Sta/Elev= 14
   -12.9   52.17    -2.9   52.17    -1.9   52.87     -.9   52.87     -.9   53.17
       0   53.17     1.3   52.17     3.5   52.17     4.8   53.17     5.2   53.17
     6.6   54.17     9.6   54.17    13.6   56.87    23.6   56.87
#Mann= 3 , 0 , 0
   -12.9    .035       0       0    .035       0     6.6    .035       0
#XS Ineff= 2 , 0
               0      60     6.6              60
Permanent Ineff=
       F       F
#Block Obstruct= 2 , 0
                             6.6
Bank Sta=0,6.6
XS Rating Curve= 0
Exp/Cntr=.3,.1

Type RM Length L Ch R = 1 ,1325.00 ,25,25,25
BEGIN DESCRIPTION:
26.025
END DESCRIPTION:
#Sta/Elev= 16
   -12.9   52.17    -2.9   52.17    -1.9   52.87     -.9   52.87     -.9   53.17
       0   53.17     1.3   52.17     1.3   50.97     3.5   50.97     3.5   52.17
     4.8   53.17     5.2   53.17     6.6   54.17     9.6   54.17    13.6   56.87
    23.6   56.87
#Mann= 3 , 0 , 0
   -12.9    .035       0       0    .035       0     6.6    .035       0
#XS Ineff= 2 , 0
               0      60     6.6              60
Permanent Ineff=
       F       F
#Block Obstruct= 2 , 0
                             6.6
Bank Sta=0,6.6
XS Rating Curve= 0
Exp/Cntr=.3,.1

Type RM Length L Ch R = 1 ,1300.00 ,38,38,38
BEGIN DESCRIPTION:
26
END DESCRIPTION:
#Sta/Elev= 17
   -12.6   52.27    -2.6   52.27    -1.4   53.37       0   53.37     1.2   52.77
     1.5   52.77       2   50.77     3.1   50.77     3.3   50.97     4.6   50.97
     5.1   52.47     5.3   52.47     7.2   53.67     8.2   54.07     9.9   54.07
    11.3   52.57    21.3   52.57
#Mann= 3 , 0 , 0
   -12.6    .035       0       0    .035       0     8.2    .035       0
#XS Ineff= 2 , 0
               0      60     8.2              60
Permanent Ineff=
       F       F
#Block Obstruct= 2 , 0
                             8.2
Bank Sta=0,8.2
XS Rating Curve= 0
Exp/Cntr=.3,.1

Type RM Length L Ch R = 1 ,1262.00 ,12,12,12
BEGIN DESCRIPTION:
25.012
END DESCRIPTION:
#Sta/Elev= 13
   -12.9   51.62    -2.9   51.62    -1.9   52.42       0   52.42      .6   50.32
     1.6   50.32     2.9   50.92     3.4   52.32     3.7   52.32     6.9   53.22
     8.6   53.22     9.2   52.72    19.2   52.72
#Mann= 3 , 0 , 0
   -12.9    .035       0       0    .035       0     6.9    .035       0
#XS Ineff= 2 , 0
               0      60     6.9              60
Permanent Ineff=
       F       F
#Block Obstruct= 2 , 0
                             6.9
Bank Sta=0,6.9
XS Rating Curve= 0
Exp/Cntr=.3,.1

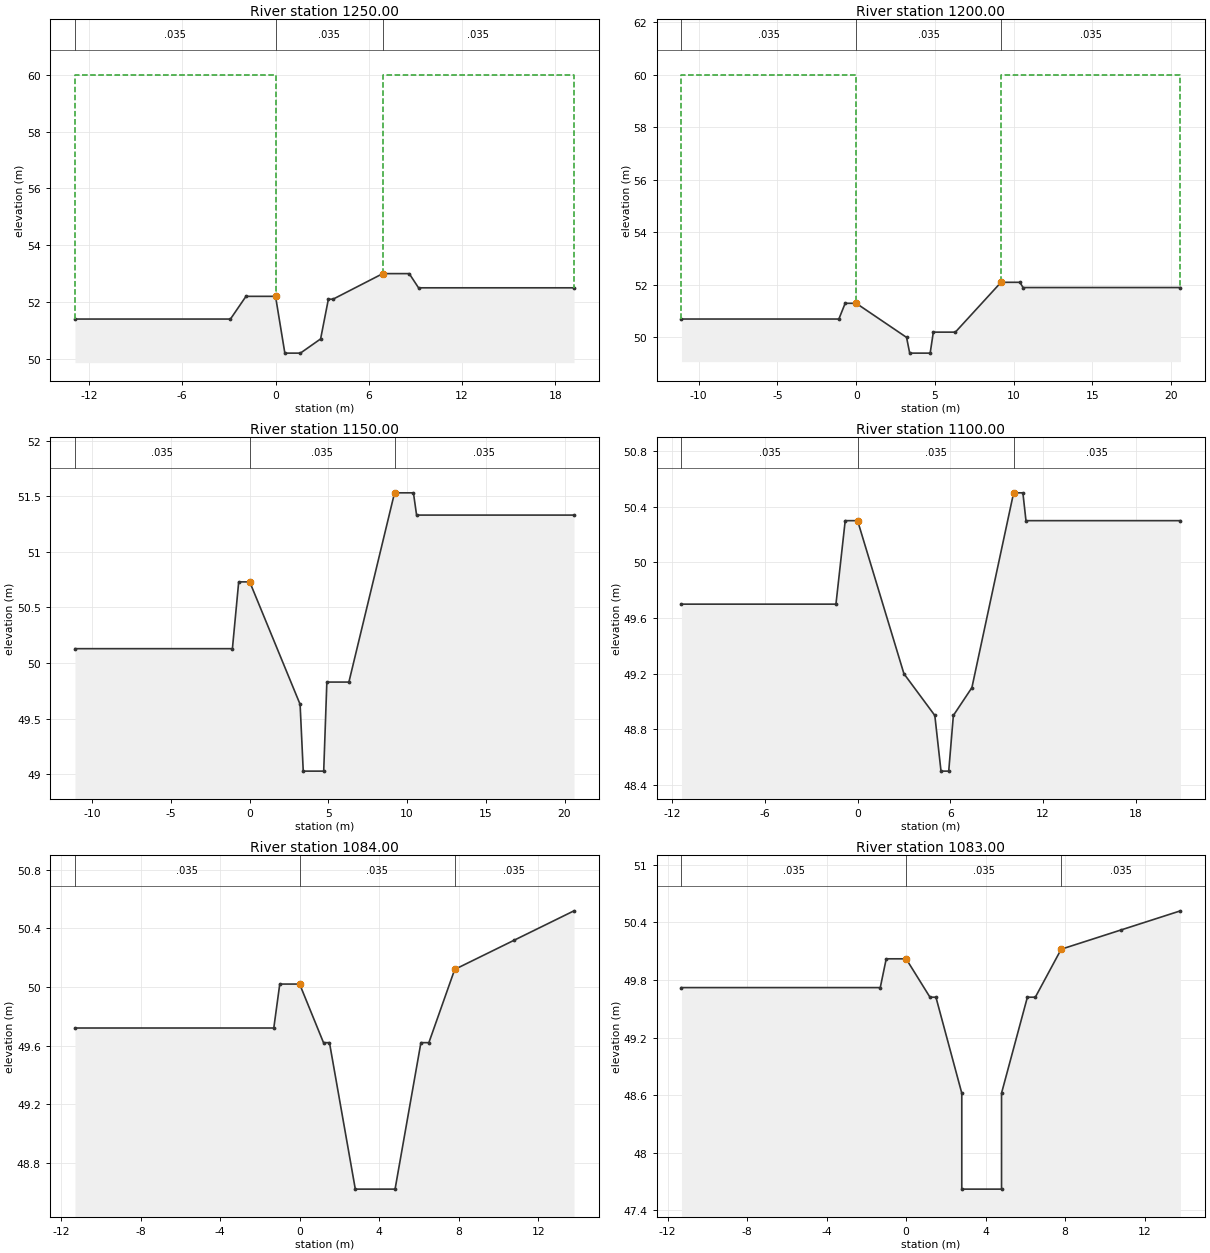
Type RM Length L Ch R = 1 ,1250.00 ,50,50,50
BEGIN DESCRIPTION:
25
END DESCRIPTION:
#Sta/Elev= 13
   -12.9    51.4    -2.9    51.4    -1.9    52.2       0    52.2      .6    50.2
     1.6    50.2     2.9    50.7     3.4    52.1     3.7    52.1     6.9      53
     8.6      53     9.2    52.5    19.2    52.5
#Mann= 3 , 0 , 0
   -12.9    .035       0       0    .035       0     6.9    .035       0
#XS Ineff= 2 , 0
               0      60     6.9              60
Permanent Ineff=
       F       F
#Block Obstruct= 2 , 0
                             6.9
Bank Sta=0,6.9
XS Rating Curve= 0
Exp/Cntr=.3,.1

Type RM Length L Ch R = 1 ,1200.00 ,50,50,50
BEGIN DESCRIPTION:
24
END DESCRIPTION:
#Sta/Elev= 13
   -11.1   50.69    -1.1   50.69     -.7   51.29       0   51.29     3.2   49.99
     3.4   49.39     4.7   49.39     4.9   50.19     6.3   50.19     9.2   52.09
    10.4   52.09    10.6   51.89    20.6   51.89
#Mann= 3 , 0 , 0
   -11.1    .035       0       0    .035       0     9.2    .035       0
#XS Ineff= 2 , 0
               0      60     9.2              60
Permanent Ineff=
       F       F
#Block Obstruct= 2 , 0
                             9.2
Bank Sta=0,9.2
XS Rating Curve= 0
Exp/Cntr=.3,.1

Type RM Length L Ch R = 1 ,1150.00 ,50,50,50
BEGIN DESCRIPTION:
23
END DESCRIPTION:
#Sta/Elev= 13
   -11.1   50.13    -1.1   50.13     -.7   50.73       0   50.73     3.2   49.63
     3.4   49.03     4.7   49.03     4.9   49.83     6.3   49.83     9.2   51.53
    10.4   51.53    10.6   51.33    20.6   51.33
#Mann= 3 , 0 , 0
   -11.1    .035       0       0    .035       0     9.2    .035       0
#XS Ineff= 2 , 0
               0      60     9.2              60
Permanent Ineff=
       F       F
#Block Obstruct= 2 , 0
                             9.2
Bank Sta=0,9.2
XS Rating Curve= 0
Exp/Cntr=.3,.1

Type RM Length L Ch R = 1 ,1100.00 ,16,16,16
BEGIN DESCRIPTION:
22
END DESCRIPTION:
#Sta/Elev= 14
   -11.4    49.7    -1.4    49.7     -.8    50.3       0    50.3       3    49.2
       5    48.9     5.4    48.5     5.9    48.5     6.2    48.9     7.4    49.1
    10.1    50.5    10.7    50.5    10.9    50.3    20.9    50.3
#Mann= 3 , 0 , 0
   -11.4    .035       0       0    .035       0    10.1    .035       0
#XS Ineff= 2 , 0
               0      60    10.1              60
Permanent Ineff=
       F       F
#Block Obstruct= 2 , 0
                            10.1
Bank Sta=0,10.1
XS Rating Curve= 0
Exp/Cntr=.3,.1

Type RM Length L Ch R = 1 ,1084.00 ,1,1,1
BEGIN DESCRIPTION:
21.034
END DESCRIPTION:
#Sta/Elev= 13
   -11.3   49.72    -1.3   49.72      -1   50.02       0   50.02     1.2   49.62
     1.5   49.62     2.8   48.62     4.8   48.62     6.1   49.62     6.5   49.62
     7.8   50.12    10.8   50.32    13.8   50.52
#Mann= 3 , 0 , 0
   -11.3    .035       0       0    .035       0     7.8    .035       0
#XS Ineff= 2 , 0
               0      60     7.8              60
Permanent Ineff=
       F       F
#Block Obstruct= 2 , 0
                             7.8
Bank Sta=0,7.8
XS Rating Curve= 0
Exp/Cntr=.3,.1

Type RM Length L Ch R = 1 ,1083.00 ,33,33,33
BEGIN DESCRIPTION:
21.033
END DESCRIPTION:
#Sta/Elev= 15
   -11.3   49.72    -1.3   49.72      -1   50.02       0   50.02     1.2   49.62
     1.5   49.62     2.8   48.62     2.8   47.62     4.8   47.62     4.8   48.62
     6.1   49.62     6.5   49.62     7.8   50.12    10.8   50.32    13.8   50.52
#Mann= 3 , 0 , 0
   -11.3    .035       0       0    .035       0     7.8    .035       0
#XS Ineff= 2 , 0
               0      60     7.8              60
Permanent Ineff=
       F       F
#Block Obstruct= 2 , 0
                             7.8
Bank Sta=0,7.8
XS Rating Curve= 0
Exp/Cntr=.3,.1

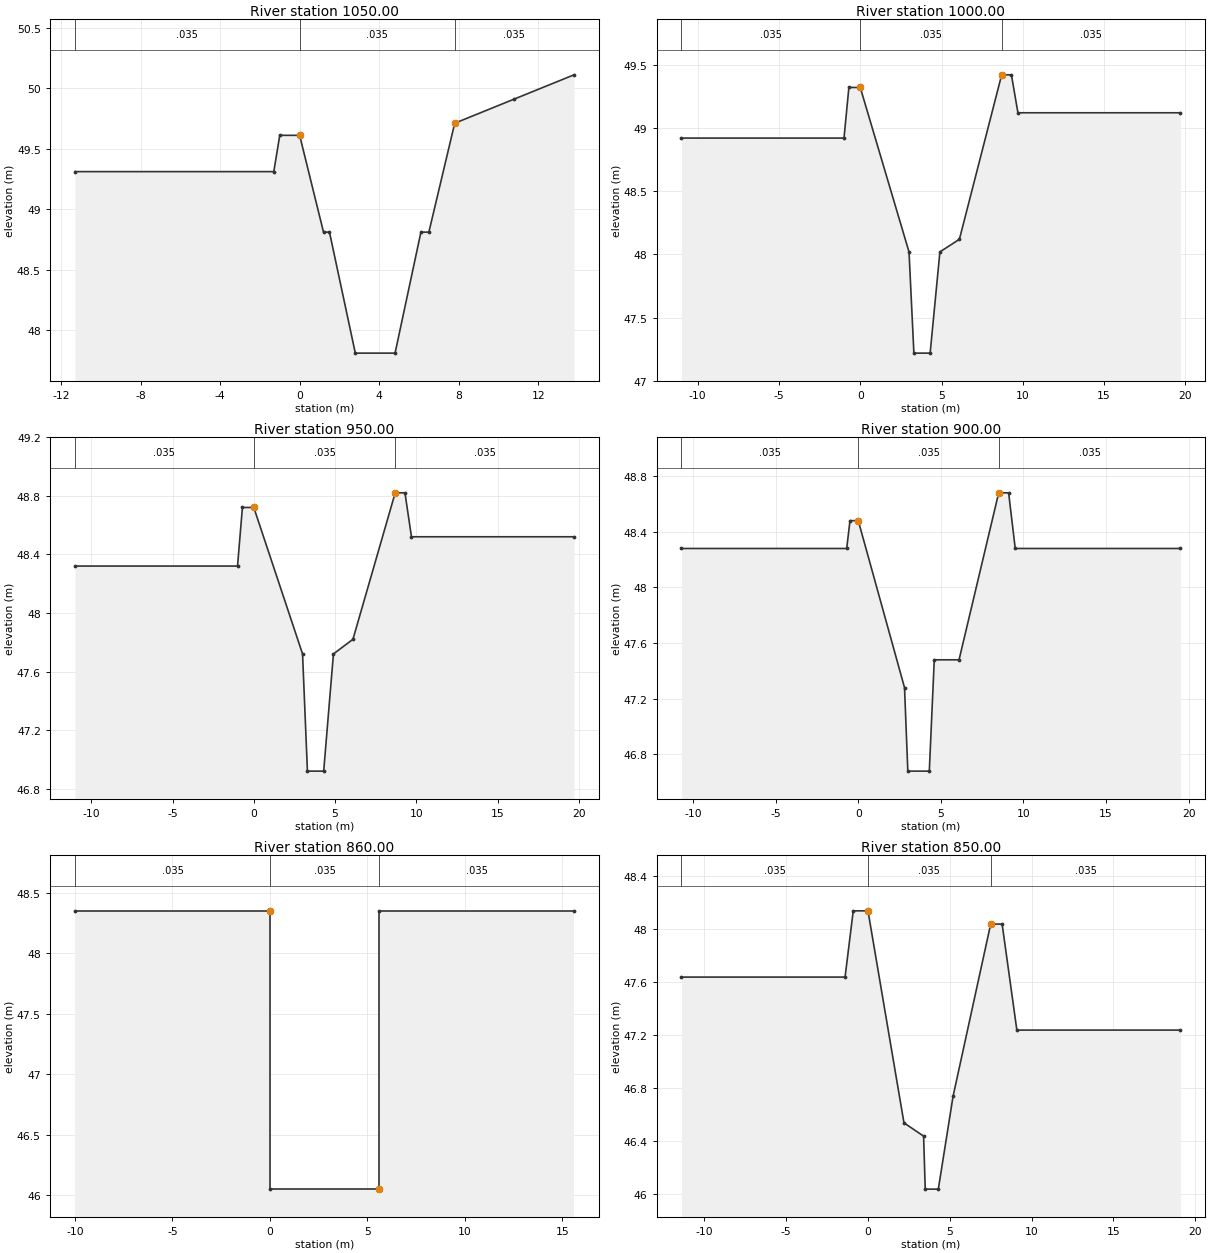
Type RM Length L Ch R = 1 ,1050.00 ,50,50,50
BEGIN DESCRIPTION:
21
END DESCRIPTION:
#Sta/Elev= 13
   -11.3   49.31    -1.3   49.31      -1   49.61       0   49.61     1.2   48.81
     1.5   48.81     2.8   47.81     4.8   47.81     6.1   48.81     6.5   48.81
     7.8   49.71    10.8   49.91    13.8   50.11
#Mann= 3 , 0 , 0
   -11.3    .035       0       0    .035       0     7.8    .035       0
#XS Ineff= 2 , 0
               0      60     7.8              60
Permanent Ineff=
       F       F
#Block Obstruct= 2 , 0
                             7.8
Bank Sta=0,7.8
XS Rating Curve= 0
Exp/Cntr=.3,.1

Type RM Length L Ch R = 1 ,1000.00 ,50,50,50
BEGIN DESCRIPTION:
20
END DESCRIPTION:
#Sta/Elev= 13
     -11   48.92      -1   48.92     -.7   49.32       0   49.32       3   48.02
     3.3   47.22     4.3   47.22     4.9   48.02     6.1   48.12     8.7   49.42
     9.3   49.42     9.7   49.12    19.7   49.12
#Mann= 3 , 0 , 0
     -11    .035       0       0    .035       0     8.7    .035       0
#XS Ineff= 2 , 0
               0      60     8.7              60
Permanent Ineff=
       F       F
#Block Obstruct= 2 , 0
                             8.7
Bank Sta=0,8.7
XS Rating Curve= 0
Exp/Cntr=.3,.1

Type RM Length L Ch R = 1 ,950.00  ,50,50,50
BEGIN DESCRIPTION:
19
END DESCRIPTION:
#Sta/Elev= 13
     -11   48.32      -1   48.32     -.7   48.72       0   48.72       3   47.72
     3.3   46.92     4.3   46.92     4.9   47.72     6.1   47.82     8.7   48.82
     9.3   48.82     9.7   48.52    19.7   48.52
#Mann= 3 , 0 , 0
     -11    .035       0       0    .035       0     8.7    .035       0
#XS Ineff= 2 , 0
               0      60     8.7              60
Permanent Ineff=
       F       F
#Block Obstruct= 2 , 0
                             8.7
Bank Sta=0,8.7
XS Rating Curve= 0
Exp/Cntr=.3,.1

Type RM Length L Ch R = 1 ,900.00  ,40,40,40
BEGIN DESCRIPTION:
18
END DESCRIPTION:
#Sta/Elev= 13
   -10.7   48.28     -.7   48.28     -.5   48.48       0   48.48     2.8   47.28
       3   46.68     4.3   46.68     4.6   47.48     6.1   47.48     8.5   48.68
     9.1   48.68     9.5   48.28    19.5   48.28
#Mann= 3 , 0 , 0
   -10.7    .035       0       0    .035       0     8.5    .035       0
#XS Ineff= 2 , 0
               0      60     8.5              60
Permanent Ineff=
       F       F
#Block Obstruct= 2 , 0
                             8.5
Bank Sta=0,8.5
XS Rating Curve= 0
Exp/Cntr=.3,.1

Type RM Length L Ch R = 1 ,860.00  ,10,10,10
BEGIN DESCRIPTION:
17.01
END DESCRIPTION:
#Sta/Elev= 6
     -10   48.35       0   48.35       0   46.05     5.6   46.05     5.6   48.35
    15.6   48.35
#Mann= 3 , 0 , 0
     -10    .035       0       0    .035       0     5.6    .035       0
#XS Ineff= 2 , 0
               0      60     5.6              60
Permanent Ineff=
       F       F
#Block Obstruct= 2 , 0
                             5.6
Bank Sta=0,5.6
XS Rating Curve= 0
Exp/Cntr=.3,.1

Type RM Length L Ch R = 1 ,850.00  ,50,50,50
BEGIN DESCRIPTION:
17
END DESCRIPTION:
#Sta/Elev= 13
   -11.4   47.64    -1.4   47.64     -.9   48.14       0   48.14     2.2   46.54
     3.4   46.44     3.5   46.04     4.3   46.04     5.2   46.74     7.5   48.04
     8.2   48.04     9.1   47.24    19.1   47.24
#Mann= 3 , 0 , 0
   -11.4    .035       0       0    .035       0     7.5    .035       0
#XS Ineff= 2 , 0
               0      60     7.5              60
Permanent Ineff=
       F       F
#Block Obstruct= 2 , 0
                             7.5
Bank Sta=0,7.5
XS Rating Curve= 0
Exp/Cntr=.3,.1

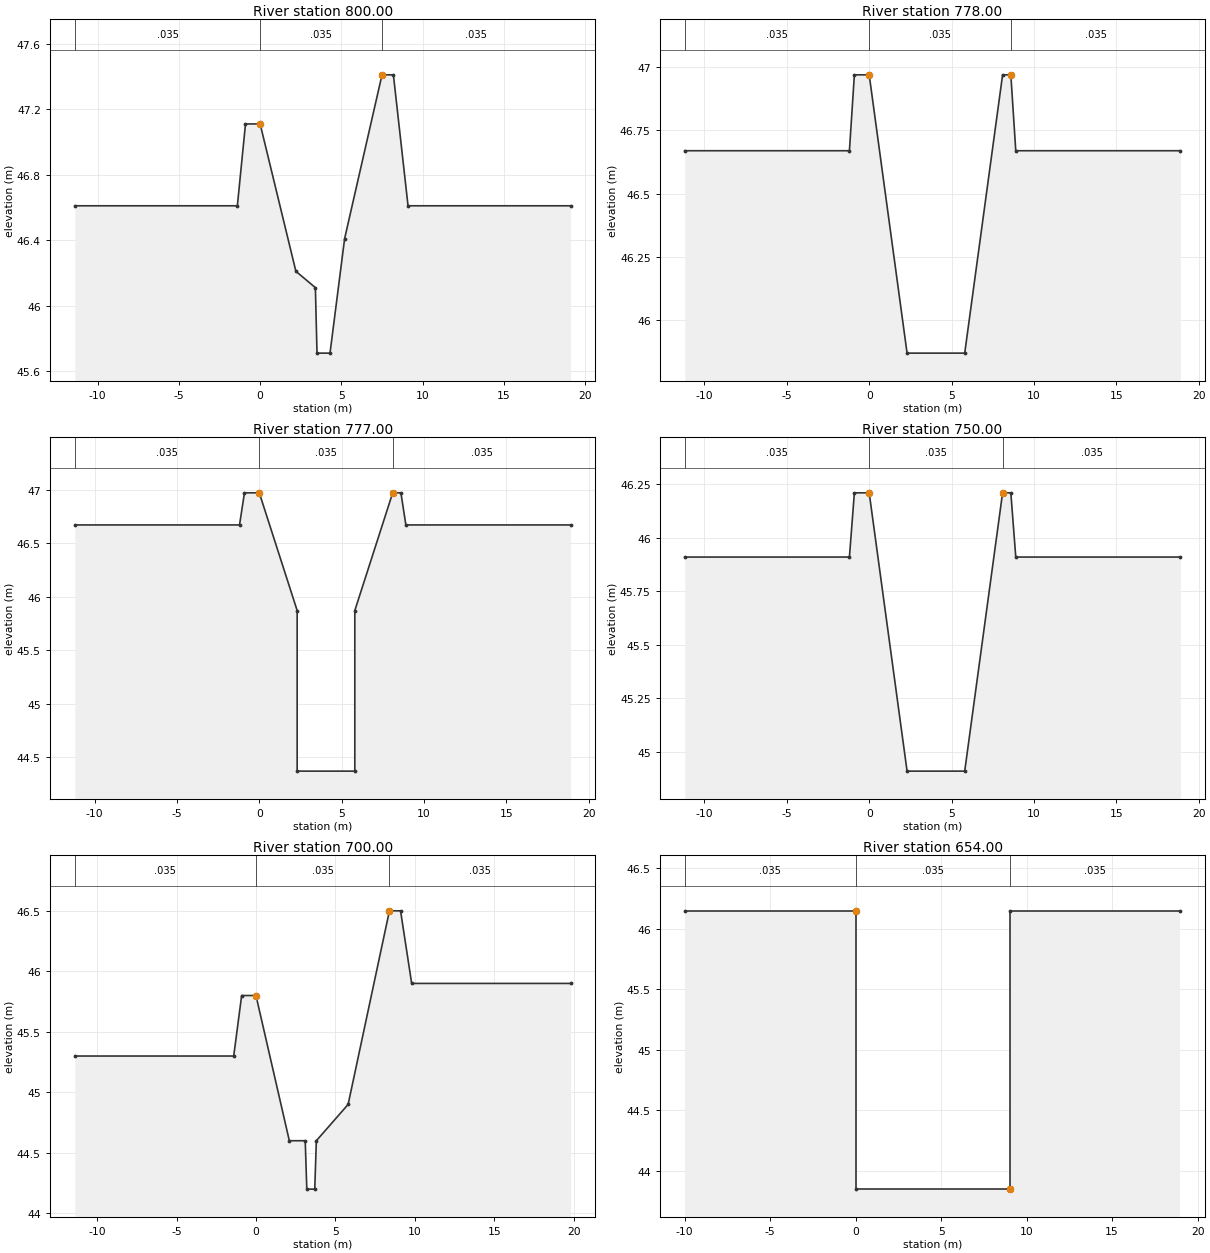
Type RM Length L Ch R = 1 ,800.00  ,22,22,22
BEGIN DESCRIPTION:
16
END DESCRIPTION:
#Sta/Elev= 13
   -11.4   46.61    -1.4   46.61     -.9   47.11       0   47.11     2.2   46.21
     3.4   46.11     3.5   45.71     4.3   45.71     5.2   46.41     7.5   47.41
     8.2   47.41     9.1   46.61    19.1   46.61
#Mann= 3 , 0 , 0
   -11.4    .035       0       0    .035       0     7.5    .035       0
#XS Ineff= 2 , 0
               0      60     7.5              60
Permanent Ineff=
       F       F
#Block Obstruct= 2 , 0
                             7.5
Bank Sta=0,7.5
XS Rating Curve= 0
Exp/Cntr=.3,.1

Type RM Length L Ch R = 1 ,778.00  ,1,1,1
BEGIN DESCRIPTION:
15.028
END DESCRIPTION:
#Sta/Elev= 10
   -11.2   46.67    -1.2   46.67     -.9   46.97       0   46.97     2.3   45.87
     5.8   45.87     8.1   46.97     8.6   46.97     8.9   46.67    18.9   46.67
#Mann= 3 , 0 , 0
   -11.2    .035       0       0    .035       0     8.6    .035       0
#XS Ineff= 2 , 0
               0      60     8.6              60
Permanent Ineff=
       F       F
#Block Obstruct= 2 , 0
                             8.6
Bank Sta=0,8.6
XS Rating Curve= 0
Exp/Cntr=.3,.1

Type RM Length L Ch R = 1 ,777.00  ,27,27,27
BEGIN DESCRIPTION:
15.027
END DESCRIPTION:
#Sta/Elev= 12
   -11.2   46.67    -1.2   46.67     -.9   46.97       0   46.97     2.3   45.87
     2.3   44.37     5.8   44.37     5.8   45.87     8.1   46.97     8.6   46.97
     8.9   46.67    18.9   46.67
#Mann= 3 , 0 , 0
   -11.2    .035       0       0    .035       0     8.1    .035       0
#XS Ineff= 2 , 0
               0      60     8.1              62
Permanent Ineff=
       F       F
#Block Obstruct= 2 , 0
                             8.1
Bank Sta=0,8.1
XS Rating Curve= 0
Exp/Cntr=.3,.1

Type RM Length L Ch R = 1 ,750.00  ,50,50,50
BEGIN DESCRIPTION:
15
END DESCRIPTION:
#Sta/Elev= 10
   -11.2   45.91    -1.2   45.91     -.9   46.21       0   46.21     2.3   44.91
     5.8   44.91     8.1   46.21     8.6   46.21     8.9   45.91    18.9   45.91
#Mann= 3 , 0 , 0
   -11.2    .035       0       0    .035       0     8.1    .035       0
#XS Ineff= 2 , 0
               0      60     8.1              60
Permanent Ineff=
       F       F
#Block Obstruct= 2 , 0
                             8.1
Bank Sta=0,8.1
XS Rating Curve= 0
Exp/Cntr=.3,.1

Type RM Length L Ch R = 1 ,700.00  ,46,46,46
BEGIN DESCRIPTION:
14
END DESCRIPTION:
#Sta/Elev= 14
   -11.4    45.3    -1.4    45.3     -.9    45.8       0    45.8     2.1    44.6
     3.1    44.6     3.2    44.2     3.7    44.2     3.8    44.6     5.8    44.9
     8.4    46.5     9.1    46.5     9.8    45.9    19.8    45.9
#Mann= 3 , 0 , 0
   -11.4    .035       0       0    .035       0     8.4    .035       0
#XS Ineff= 2 , 0
               0      60     8.4              60
Permanent Ineff=
       F       F
#Block Obstruct= 2 , 0
                             8.4
Bank Sta=0,8.4
XS Rating Curve= 0
Exp/Cntr=.3,.1

Type RM Length L Ch R = 1 ,654.00  ,4,4,4
BEGIN DESCRIPTION:
13.004
END DESCRIPTION:
#Sta/Elev= 6
     -10   46.15       0   46.15       0   43.85       9   43.85       9   46.15
      19   46.15
#Mann= 3 , 0 , 0
     -10    .035       0       0    .035       0       9    .035       0
#XS Ineff= 2 , 0
               0      60       9              60
Permanent Ineff=
       F       F
#Block Obstruct= 2 , 0
                               9
Bank Sta=0,9
XS Rating Curve= 0
Exp/Cntr=.3,.1