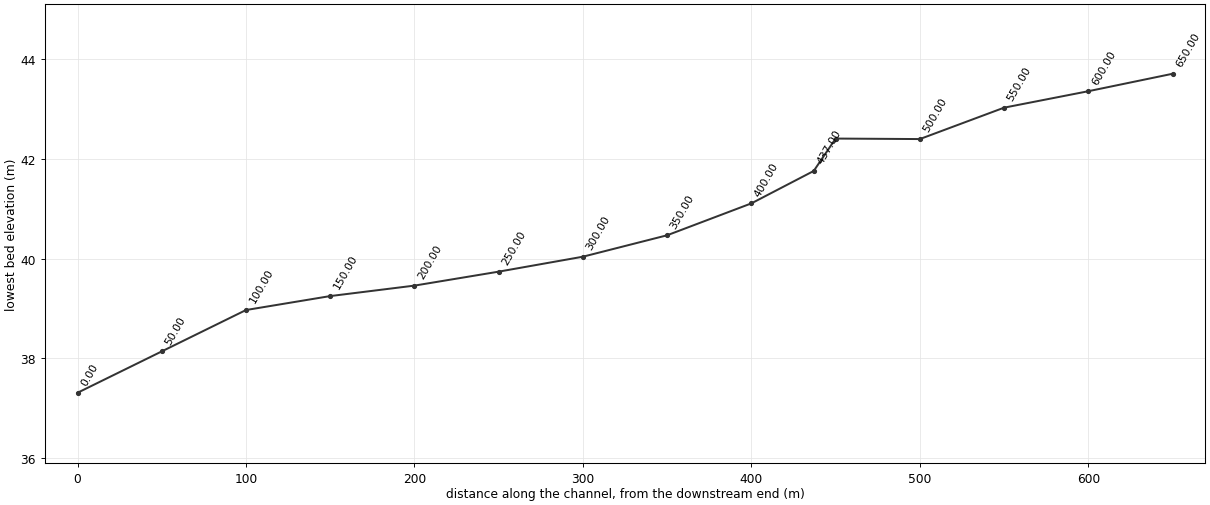
HEC-RAS study JANG.prj: JANG

--- JANG.g01 (geometry) --- (continued)

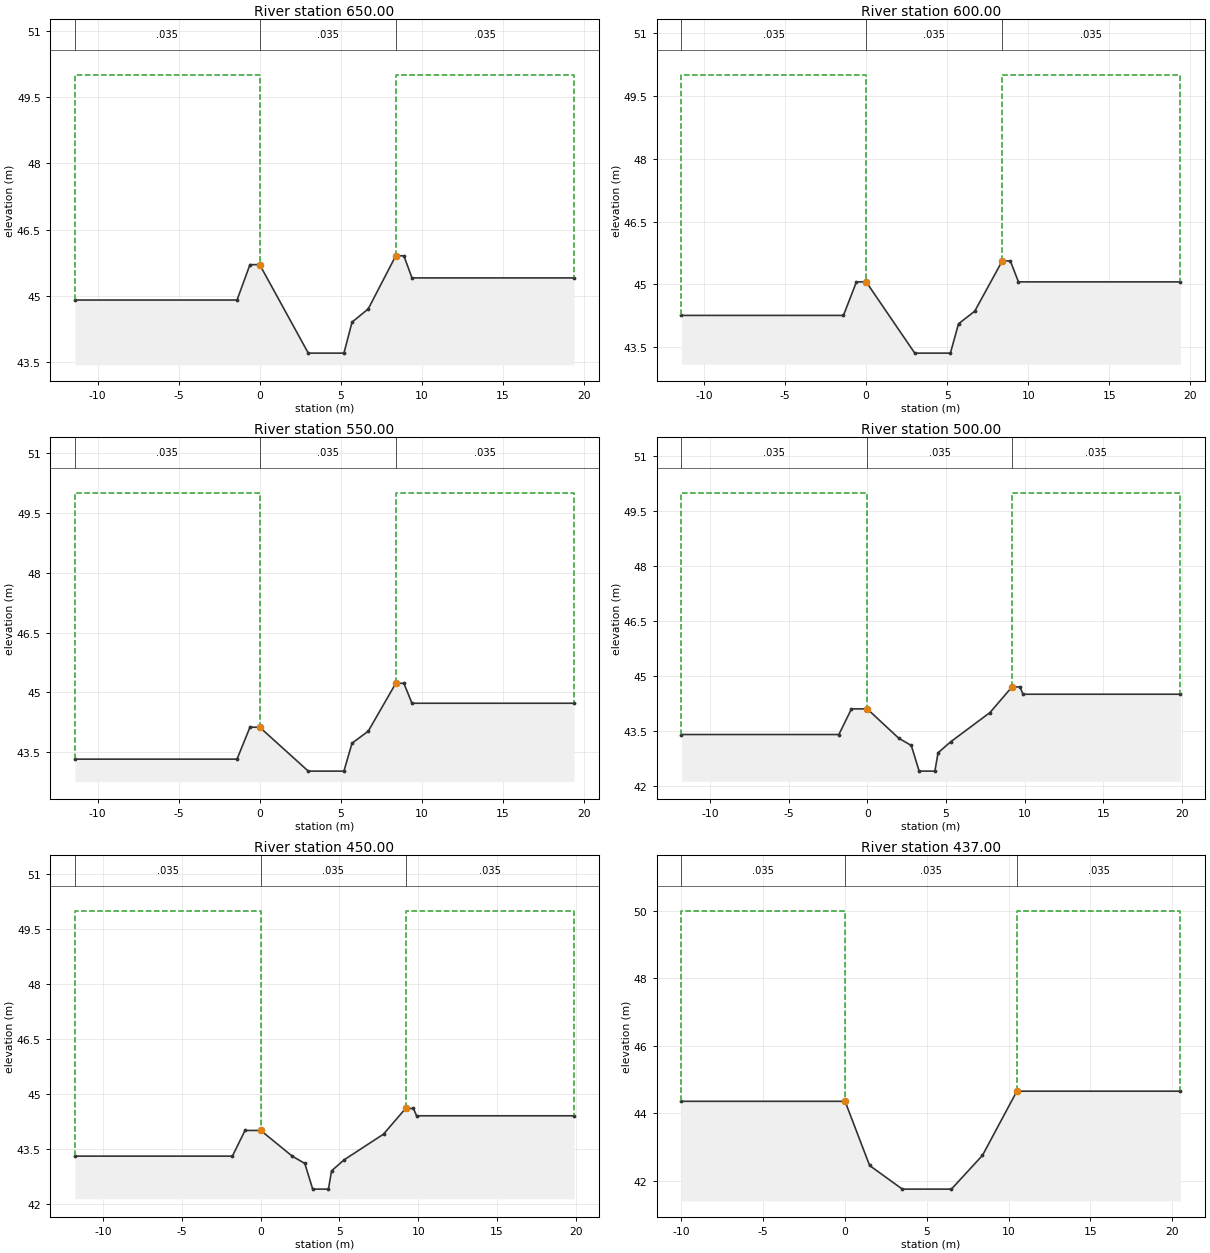
Type RM Length L Ch R = 1 ,650.00  ,50,50,50
BEGIN DESCRIPTION:
13
END DESCRIPTION:
#Sta/Elev= 12
   -11.4   44.91    -1.4   44.91     -.6   45.71       0   45.71       3   43.71
     5.2   43.71     5.7   44.41     6.7   44.71     8.4   45.91     8.9   45.91
     9.4   45.41    19.4   45.41
#Mann= 3 , 0 , 0
   -11.4    .035       0       0    .035       0     8.4    .035       0
#XS Ineff= 2 , 0
               0      50     8.4              50
Permanent Ineff=
       F       F
#Block Obstruct= 2 , 0
                             8.4
Bank Sta=0,8.4
XS Rating Curve= 0
Exp/Cntr=.3,.1

Type RM Length L Ch R = 1 ,600.00  ,50,50,50
BEGIN DESCRIPTION:
12
END DESCRIPTION:
#Sta/Elev= 12
   -11.4   44.26    -1.4   44.26     -.6   45.06       0   45.06       3   43.36
     5.2   43.36     5.7   44.06     6.7   44.36     8.4   45.56     8.9   45.56
     9.4   45.06    19.4   45.06
#Mann= 3 , 0 , 0
   -11.4    .035       0       0    .035       0     8.4    .035       0
#XS Ineff= 2 , 0
               0      50     8.4              50
Permanent Ineff=
       F       F
#Block Obstruct= 2 , 0
                             8.4
Bank Sta=0,8.4
XS Rating Curve= 0
Exp/Cntr=.3,.1

Type RM Length L Ch R = 1 ,550.00  ,50,50,50
BEGIN DESCRIPTION:
11
END DESCRIPTION:
#Sta/Elev= 12
   -11.4   43.33    -1.4   43.33     -.6   44.13       0   44.13       3   43.03
     5.2   43.03     5.7   43.73     6.7   44.03     8.4   45.23     8.9   45.23
     9.4   44.73    19.4   44.73
#Mann= 3 , 0 , 0
   -11.4    .035       0       0    .035       0     8.4    .035       0
#XS Ineff= 2 , 0
               0      50     8.4              50
Permanent Ineff=
       F       F
#Block Obstruct= 2 , 0
                             8.4
Bank Sta=0,8.4
XS Rating Curve= 0
Exp/Cntr=.3,.1

Type RM Length L Ch R = 1 ,500.00  ,50,50,50
BEGIN DESCRIPTION:
10
END DESCRIPTION:
#Sta/Elev= 15
   -11.8    43.4    -1.8    43.4      -1    44.1       0    44.1       2    43.3
     2.8    43.1     3.3    42.4     4.3    42.4     4.5    42.9     5.3    43.2
     7.8      44     9.2    44.7     9.7    44.7     9.9    44.5    19.9    44.5
#Mann= 3 , 0 , 0
   -11.8    .035       0       0    .035       0     9.2    .035       0
#XS Ineff= 2 , 0
               0      50     9.2              50
Permanent Ineff=
       F       F
#Block Obstruct= 2 , 0
                             9.2
Bank Sta=0,9.2
XS Rating Curve= 0
Exp/Cntr=.3,.1

Type RM Length L Ch R = 1 ,450.00  ,13,13,13
BEGIN DESCRIPTION:
9
END DESCRIPTION:
#Sta/Elev= 15
   -11.8   43.31    -1.8   43.31      -1   44.01       0   44.01       2   43.31
     2.8   43.11     3.3   42.41     4.3   42.41     4.5   42.91     5.3   43.21
     7.8   43.91     9.2   44.61     9.7   44.61     9.9   44.41    19.9   44.41
#Mann= 3 , 0 , 0
   -11.8    .035       0       0    .035       0     9.2    .035       0
#XS Ineff= 2 , 0
               0      50     9.2              50
Permanent Ineff=
       F       F
#Block Obstruct= 2 , 0
                             9.2
Bank Sta=0,9.2
XS Rating Curve= 0
Exp/Cntr=.3,.1

Type RM Length L Ch R = 1 ,437.00  ,37,37,37
BEGIN DESCRIPTION:
8.037
END DESCRIPTION:
#Sta/Elev= 8
     -10   44.36       0   44.36     1.5   42.46     3.5   41.76     6.5   41.76
     8.4   42.76    10.5   44.66    20.5   44.66
#Mann= 3 , 0 , 0
     -10    .035       0       0    .035       0    10.5    .035       0
#XS Ineff= 2 , 0
               0      50    10.5              50
Permanent Ineff=
       F       F
#Block Obstruct= 2 , 0
                            10.5
Bank Sta=0,10.5
XS Rating Curve= 0
Exp/Cntr=.3,.1

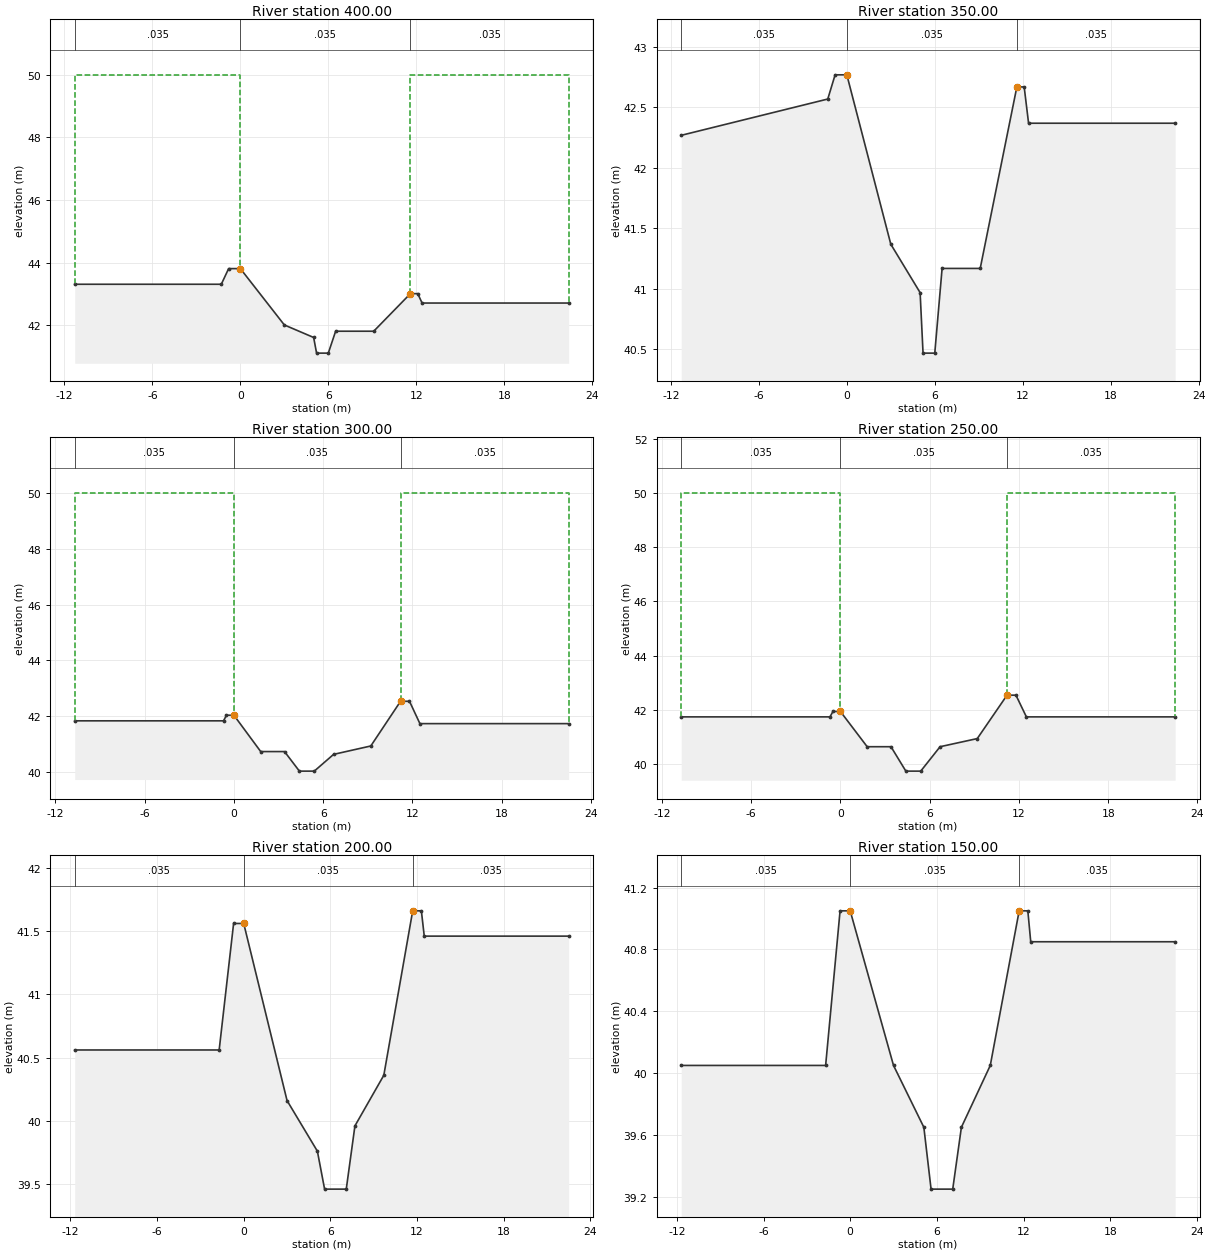
Type RM Length L Ch R = 1 ,400.00  ,50,50,50
BEGIN DESCRIPTION:
8
END DESCRIPTION:
#Sta/Elev= 14
   -11.3   43.31    -1.3   43.31     -.8   43.81       0   43.81       3   42.01
       5   41.61     5.2   41.11       6   41.11     6.5   41.81     9.1   41.81
    11.6   43.01    12.1   43.01    12.4   42.71    22.4   42.71
#Mann= 3 , 0 , 0
   -11.3    .035       0       0    .035       0    11.6    .035       0
#XS Ineff= 2 , 0
               0      50    11.6              50
Permanent Ineff=
       F       F
#Block Obstruct= 2 , 0
                            11.6
Bank Sta=0,11.6
XS Rating Curve= 0
Exp/Cntr=.3,.1

Type RM Length L Ch R = 1 ,350.00  ,50,50,50
BEGIN DESCRIPTION:
7
END DESCRIPTION:
#Sta/Elev= 14
   -11.3   42.27    -1.3   42.57     -.8   42.77       0   42.77       3   41.37
       5   40.97     5.2   40.47       6   40.47     6.5   41.17     9.1   41.17
    11.6   42.67    12.1   42.67    12.4   42.37    22.4   42.37
#Mann= 3 , 0 , 0
   -11.3    .035       0       0    .035       0    11.6    .035       0
#XS Ineff= 2 , 0
               0      50    11.6              50
Permanent Ineff=
       F       F
#Block Obstruct= 2 , 0
                            11.6
Bank Sta=0,11.6
XS Rating Curve= 0
Exp/Cntr=.3,.1

Type RM Length L Ch R = 1 ,300.00  ,50,50,50
BEGIN DESCRIPTION:
6
END DESCRIPTION:
#Sta/Elev= 14
   -10.7   41.84     -.7   41.84     -.5   42.04       0   42.04     1.8   40.74
     3.4   40.74     4.4   40.04     5.4   40.04     6.7   40.64     9.2   40.94
    11.2   42.54    11.8   42.54    12.5   41.74    22.5   41.74
#Mann= 3 , 0 , 0
   -10.7    .035       0       0    .035       0    11.2    .035       0
#XS Ineff= 2 , 0
               0      50    11.2              50
Permanent Ineff=
       F       F
#Block Obstruct= 2 , 0
                            11.2
Bank Sta=0,11.2
XS Rating Curve= 0
Exp/Cntr=.3,.1

Type RM Length L Ch R = 1 ,250.00  ,50,50,50
BEGIN DESCRIPTION:
5
END DESCRIPTION:
#Sta/Elev= 14
   -10.7   41.74     -.7   41.74     -.5   41.94       0   41.94     1.8   40.64
     3.4   40.64     4.4   39.74     5.4   39.74     6.7   40.64     9.2   40.94
    11.2   42.54    11.8   42.54    12.5   41.74    22.5   41.74
#Mann= 3 , 0 , 0
   -10.7    .035       0       0    .035       0    11.2    .035       0
#XS Ineff= 2 , 0
               0      50    11.2              50
Permanent Ineff=
       F       F
#Block Obstruct= 2 , 0
                            11.2
Bank Sta=0,11.2
XS Rating Curve= 0
Exp/Cntr=.3,.1

Type RM Length L Ch R = 1 ,200.00  ,50,50,50
BEGIN DESCRIPTION:
4
END DESCRIPTION:
#Sta/Elev= 14
   -11.7   40.56    -1.7   40.56     -.7   41.56       0   41.56       3   40.16
     5.1   39.76     5.6   39.46     7.1   39.46     7.7   39.96     9.7   40.36
    11.7   41.66    12.3   41.66    12.5   41.46    22.5   41.46
#Mann= 3 , 0 , 0
   -11.7    .035       0       0    .035       0    11.7    .035       0
#XS Ineff= 2 , 0
               0      50    11.7              50
Permanent Ineff=
       F       F
#Block Obstruct= 2 , 0
                            11.7
Bank Sta=0,11.7
XS Rating Curve= 0
Exp/Cntr=.3,.1

Type RM Length L Ch R = 1 ,150.00  ,50,50,50
BEGIN DESCRIPTION:
3
END DESCRIPTION:
#Sta/Elev= 14
   -11.7   40.05    -1.7   40.05     -.7   41.05       0   41.05       3   40.05
     5.1   39.65     5.6   39.25     7.1   39.25     7.7   39.65     9.7   40.05
    11.7   41.05    12.3   41.05    12.5   40.85    22.5   40.85
#Mann= 3 , 0 , 0
   -11.7    .035       0       0    .035       0    11.7    .035       0
#XS Ineff= 2 , 0
               0      50    11.7              50
Permanent Ineff=
       F       F
#Block Obstruct= 2 , 0
                            11.7
Bank Sta=0,11.7
XS Rating Curve= 0
Exp/Cntr=.3,.1

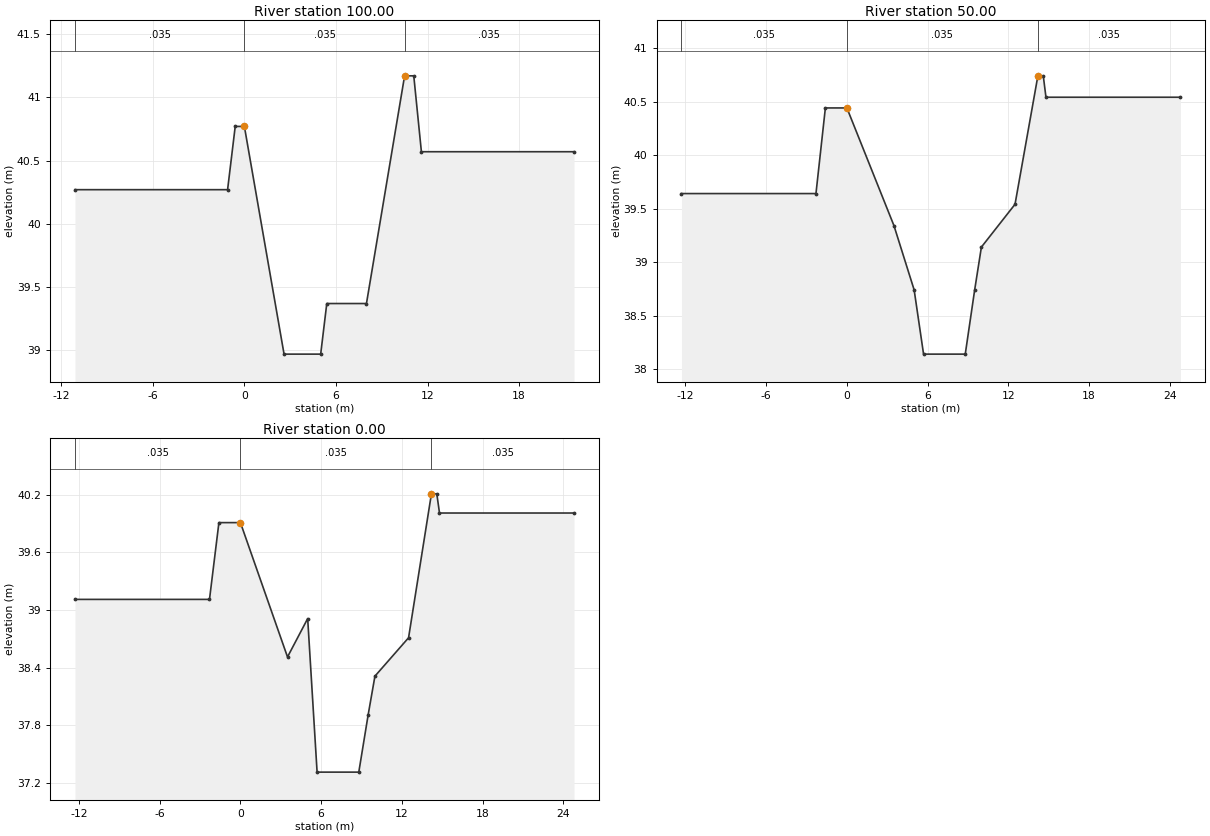
Type RM Length L Ch R = 1 ,100.00  ,50,50,50
BEGIN DESCRIPTION:
2
END DESCRIPTION:
#Sta/Elev= 12
   -11.1   40.27    -1.1   40.27     -.6   40.77       0   40.77     2.6   38.97
       5   38.97     5.4   39.37       8   39.37    10.5   41.17    11.1   41.17
    11.6   40.57    21.6   40.57
#Mann= 3 , 0 , 0
   -11.1    .035       0       0    .035       0    10.5    .035       0
#XS Ineff= 2 , 0
               0      50    10.5              50
Permanent Ineff=
       F       F
#Block Obstruct= 2 , 0
                            10.5
Bank Sta=0,10.5
XS Rating Curve= 0
Exp/Cntr=.3,.1

Type RM Length L Ch R = 1 ,50.00   ,50,50,50
BEGIN DESCRIPTION:
1
END DESCRIPTION:
#Sta/Elev= 15
   -12.3   39.64    -2.3   39.64    -1.6   40.44       0   40.44     3.5   39.34
       5   38.74     5.7   38.14     8.8   38.14     9.5   38.74      10   39.14
    12.5   39.54    14.2   40.74    14.6   40.74    14.8   40.54    24.8   40.54
#Mann= 3 , 0 , 0
   -12.3    .035       0       0    .035       0    14.2    .035       0
#XS Ineff= 2 , 0
               0      50    14.2              50
Permanent Ineff=
       F       F
#Block Obstruct= 2 , 0
                            14.2
Bank Sta=0,14.2
XS Rating Curve= 0
Exp/Cntr=.3,.1

Type RM Length L Ch R = 1 ,0.00    ,0,0,0
BEGIN DESCRIPTION:
0
END DESCRIPTION:
#Sta/Elev= 15
   -12.3   39.11    -2.3   39.11    -1.6   39.91       0   39.91     3.5   38.51
       5   38.91     5.7   37.31     8.8   37.31     9.5   37.91      10   38.31
    12.5   38.71    14.2   40.21    14.6   40.21    14.8   40.01    24.8   40.01
#Mann= 3 , 0 , 0
   -12.3    .035       0       0    .035       0    14.2    .035       0
#XS Ineff= 2 , 0
               0      50    14.2              50
Permanent Ineff=
       F       F
#Block Obstruct= 2 , 0
                            14.2
Bank Sta=0,14.2
XS Rating Curve= 0
Exp/Cntr=.3,.1

Chan Stop Cuts=-1