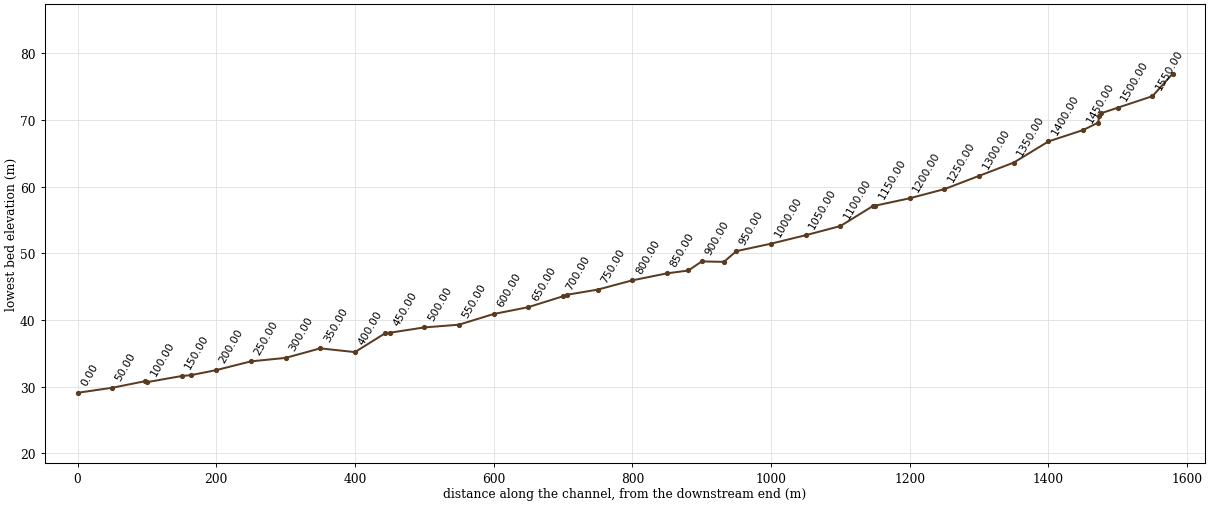
--- EUP.prj (project) ---

Proj Title=eupne-chun
Current Plan=p01
Default Exp/Contr=.3,.1
SI Units
Geom File=g01
Flow File=f01
Plan File=p01
Y Axis Title=Elevation
X Axis Title(PF)=Main Channel Distance
X Axis Title(XS)=Station
BEGIN DESCRIPTION:
           BACK WATER COMPUTATION
      APPLICATION OF HEC-2 BY Samju Construction Engineering
      eupne-chun: 10,20,30,50,80 yr
END DESCRIPTION:
DSS Export Rating Curves= 0
DSS Export Rating Curve Sorted= 0
DSS Export Volume Flow Curves= 0
DXF OffsetX= 0
DXF OffsetY= 0
DXF ScaleX= 1
DXF ScaleY= 10

--- EUP.p01 (plan) ---

Plan Title=Imported Plan 01
Version=Version 3.0.1  Mar 2001
Short Identifier=Imported Pla
Geom File=g01
Flow File=f01
Subcritical Flow
K Sum by GR= 0
Std Step Tol= 0.003
Critical Tol= 0.003
Num of Std Step Trials= 20
Max Error Tol= 0.1
Flow Tol Ratio= 0.001
Split Flow NTrial= 30
Split Flow Tol= 0.02
Split Flow Ratio= 0.02
Log Output Level= 0
Friction Slope Method= 1
Unsteady Friction Slope Method= 2
Parabolic Critical Depth
Global Vel Dist= 0 , 0 , 0
Global Log Level= 0
CheckData=True
Encroach Param=-1 ,0,0, 0
Computation Interval=1HOUR
Output Interval=1HOUR
Run HTab= 0
Run UNet= 0
Run PostProcess= 0
UNET Theta= 1
UNET ZTol= 0.02
UNET ZSATol= 0.1
UNET MxIter= 20
UNET MaxInSteps= 20
UNET DtIC= 0
UNET DtMin= 0
UNET MaxCRTS= 20
UNET WFStab= 2
UNET SFStab= 1
UNET WFX= 1
UNET SFX= 1
UNET Convert EG Bridges=-1
UNET Use Existing IB Tables=-1
Instantaneous Interval=1HOUR
Write IC File= 0
Write Velocity= 0
Write Detailed= 0

--- EUP.f01 (steady flow) ---

Flow Title=Imported Flow 01
Version=Version 3.0.1  Mar 2001
Number of Profiles= 5
Profile Names=10YR,20YR,30YR,50YR,80YR
River Rch & RM=RIVER-1,Reach-1         ,1579.00
   16.12   17.76   18.72   19.92   21.03
River Rch & RM=RIVER-1,Reach-1         ,650.00
   20.08   22.12   23.32   24.83   26.22
Boundary for River Rch & Prof#=RIVER-1,Reach-1         , 1
Up Type= 0
Dn Type= 3
Dn Slope=.064
Boundary for River Rch & Prof#=RIVER-1,Reach-1         , 2
Up Type= 0
Dn Type= 3
Dn Slope=.064
Boundary for River Rch & Prof#=RIVER-1,Reach-1         , 3
Up Type= 0
Dn Type= 3
Dn Slope=.064
Boundary for River Rch & Prof#=RIVER-1,Reach-1         , 4
Up Type= 0
Dn Type= 3
Dn Slope=.064
Boundary for River Rch & Prof#=RIVER-1,Reach-1         , 5
Up Type= 0
Dn Type= 3
Dn Slope=.064
DSS Import GetInterval= 0
DSS Import GetPeak= 0
DSS Import FillOption= 0

--- EUP.g01 (geometry) ---

Geom Title=Imported Geom 01
Version=Version 3.0.1  Mar 2001

River Reach=RIVER-1         ,Reach-1
Reach XY= 2
              .5             .95              .5             .05

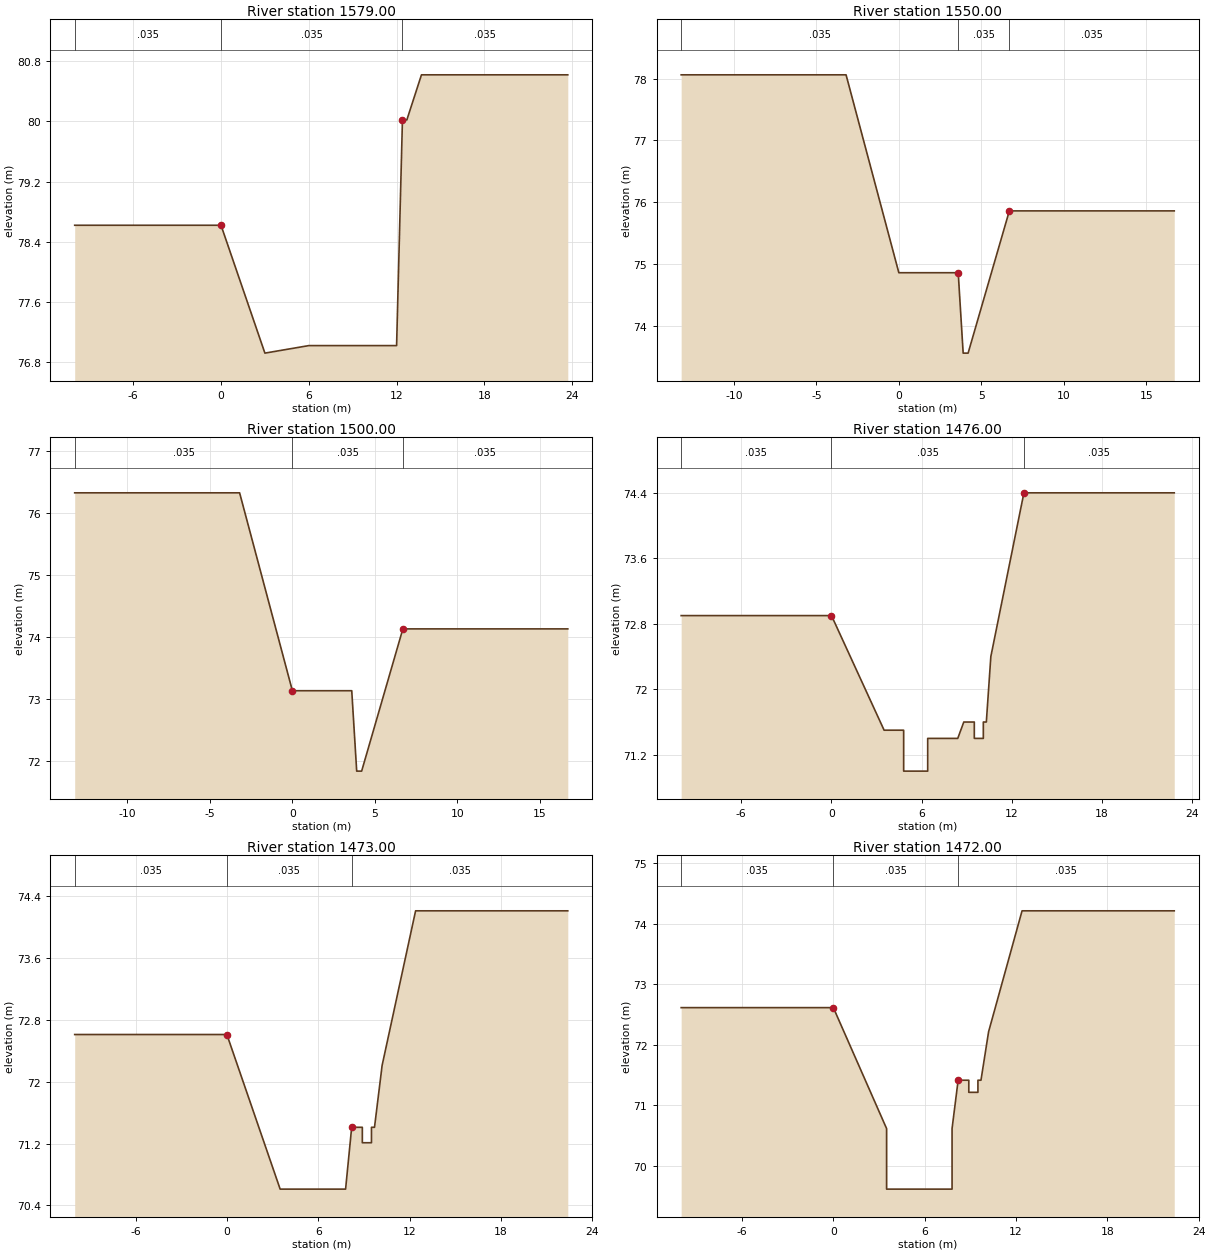
Type RM Length L Ch R = 1 ,1579.00 ,29,29,29
BEGIN DESCRIPTION:
31.029
END DESCRIPTION:
#Sta/Elev= 9
     -10   78.62       0   78.62       3   76.92       6   77.02      12   77.02
    12.4   80.02    12.7   80.02    13.7   80.62    23.7   80.62
#Mann= 3 , 0 , 0
     -10    .035       0       0    .035       0    12.4    .035       0
#XS Ineff= 2 , 0
               0   78.62    12.4           80.02
Permanent Ineff=
       F       F
Bank Sta=0,12.4
XS Rating Curve= 0
Exp/Cntr=.3,.1

Type RM Length L Ch R = 1 ,1550.00 ,50,50,50
BEGIN DESCRIPTION:
31
END DESCRIPTION:
#Sta/Elev= 8
   -13.2   78.06    -3.2   78.06       0   74.86     3.6   74.86     3.9   73.56
     4.2   73.56     6.7   75.86    16.7   75.86
#Mann= 3 , 0 , 0
   -13.2    .035       0     3.6    .035       0     6.7    .035       0
#XS Ineff= 2 , 0
             3.6   74.86     6.7           75.86
Permanent Ineff=
       F       F
Bank Sta=3.6,6.7
XS Rating Curve= 0
Exp/Cntr=.3,.1

Type RM Length L Ch R = 1 ,1500.00 ,24,24,24
BEGIN DESCRIPTION:
30
END DESCRIPTION:
#Sta/Elev= 8
   -13.2   76.33    -3.2   76.33       0   73.13     3.6   73.13     3.9   71.83
     4.2   71.83     6.7   74.13    16.7   74.13
#Mann= 3 , 0 , 0
   -13.2    .035       0       0    .035       0     6.7    .035       0
#XS Ineff= 2 , 0
               0   73.13     6.7           74.13
Permanent Ineff=
       F       F
Bank Sta=0,6.7
XS Rating Curve= 0
Exp/Cntr=.3,.1

Type RM Length L Ch R = 1 ,1476.00 ,3,3,3
BEGIN DESCRIPTION:
29.026
END DESCRIPTION:
#Sta/Elev= 17
     -10    72.9       0    72.9     3.5    71.5     4.8    71.5     4.8      71
     6.4      71     6.4    71.4     8.4    71.4     8.8    71.6     9.5    71.6
     9.5    71.4    10.1    71.4    10.1    71.6    10.3    71.6    10.6    72.4
    12.8    74.4    22.8    74.4
#Mann= 3 , 0 , 0
     -10    .035       0       0    .035       0    12.8    .035       0
#XS Ineff= 2 , 0
               0    72.9    12.8            74.4
Permanent Ineff=
       F       F
Bank Sta=0,12.8
XS Rating Curve= 0
Exp/Cntr=.3,.1

Type RM Length L Ch R = 1 ,1473.00 ,1,1,1
BEGIN DESCRIPTION:
29.023
END DESCRIPTION:
#Sta/Elev= 13
     -10   72.61       0   72.61     3.5   70.61     7.8   70.61     8.2   71.41
     8.9   71.41     8.9   71.21     9.5   71.21     9.5   71.41     9.7   71.41
    10.2   72.21    12.4   74.21    22.4   74.21
#Mann= 3 , 0 , 0
     -10    .035       0       0    .035       0     8.2    .035       0
#XS Ineff= 2 , 0
               0   72.61     8.2           71.41
Permanent Ineff=
       F       F
Bank Sta=0,8.2
XS Rating Curve= 0
Exp/Cntr=.3,.1

Type RM Length L Ch R = 1 ,1472.00 ,22,22,22
BEGIN DESCRIPTION:
29.022
END DESCRIPTION:
#Sta/Elev= 15
     -10   72.61       0   72.61     3.5   70.61     3.5   69.61     7.8   69.61
     7.8   70.61     8.2   71.41     8.9   71.41     8.9   71.21     9.5   71.21
     9.5   71.41     9.7   71.41    10.2   72.21    12.4   74.21    22.4   74.21
#Mann= 3 , 0 , 0
     -10    .035       0       0    .035       0     8.2    .035       0
#XS Ineff= 2 , 0
               0   72.61     8.2           71.41
Permanent Ineff=
       F       F
Bank Sta=0,8.2
XS Rating Curve= 0
Exp/Cntr=.3,.1

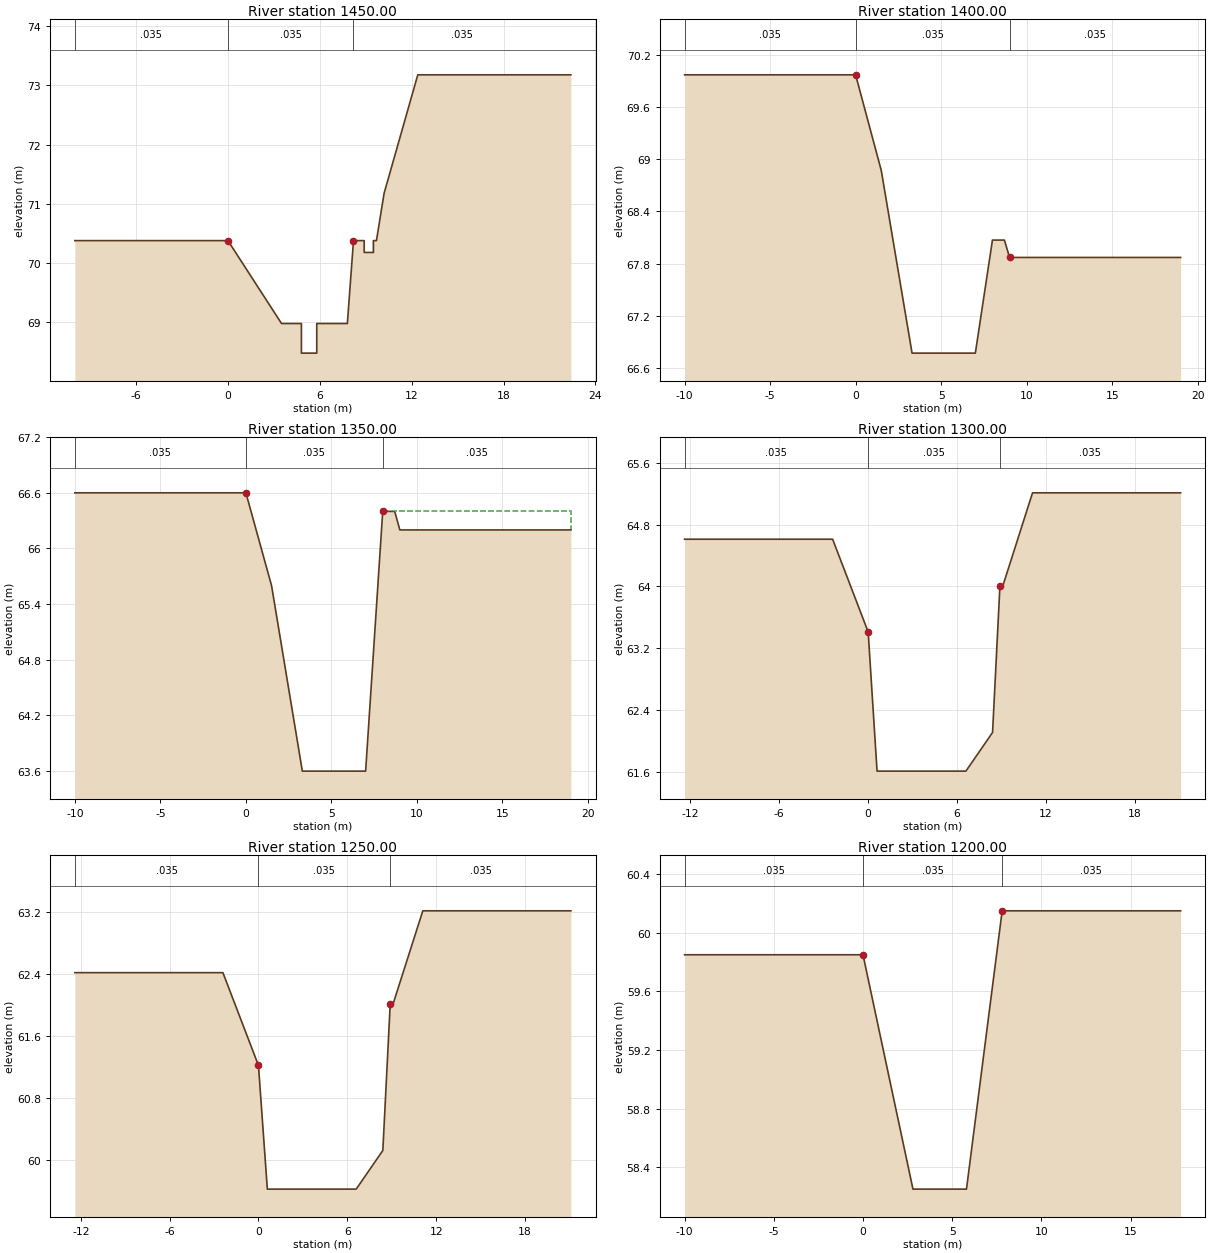
Type RM Length L Ch R = 1 ,1450.00 ,50,50,50
BEGIN DESCRIPTION:
29
END DESCRIPTION:
#Sta/Elev= 17
     -10   70.38       0   70.38     3.5   68.98     4.8   68.98     4.8   68.48
     5.8   68.48     5.8   68.98     7.8   68.98     8.2   70.38     8.9   70.38
     8.9   70.18     9.5   70.18     9.5   70.38     9.7   70.38    10.2   71.18
    12.4   73.18    22.4   73.18
#Mann= 3 , 0 , 0
     -10    .035       0       0    .035       0     8.2    .035       0
#XS Ineff= 2 , 0
               0   70.38     8.2           70.38
Permanent Ineff=
       F       F
Bank Sta=0,8.2
XS Rating Curve= 0
Exp/Cntr=.3,.1

Type RM Length L Ch R = 1 ,1400.00 ,50,50,50
BEGIN DESCRIPTION:
28
END DESCRIPTION:
#Sta/Elev= 9
     -10   69.97       0   69.97     1.5   68.87     3.3   66.77       7   66.77
       8   68.07     8.7   68.07       9   67.87      19   67.87
#Mann= 3 , 0 , 0
     -10    .035       0       0    .035       0       9    .035       0
#XS Ineff= 2 , 0
               0   69.97       9           67.87
Permanent Ineff=
       F       F
Bank Sta=0,9
XS Rating Curve= 0
Exp/Cntr=.3,.1

Type RM Length L Ch R = 1 ,1350.00 ,50,50,50
BEGIN DESCRIPTION:
27
END DESCRIPTION:
#Sta/Elev= 9
     -10    66.6       0    66.6     1.5    65.6     3.3    63.6       7    63.6
       8    66.4     8.7    66.4       9    66.2      19    66.2
#Mann= 3 , 0 , 0
     -10    .035       0       0    .035       0       8    .035       0
#XS Ineff= 2 , 0
               0    66.6       8            66.4
Permanent Ineff=
       F       F
Bank Sta=0,8
XS Rating Curve= 0
Exp/Cntr=.3,.1

Type RM Length L Ch R = 1 ,1300.00 ,50,50,50
BEGIN DESCRIPTION:
26
END DESCRIPTION:
#Sta/Elev= 10
   -12.4   64.61    -2.4   64.61       0   63.41      .6   61.61     6.6   61.61
     8.4   62.11     8.9   64.01     9.1   64.01    11.1   65.21    21.1   65.21
#Mann= 3 , 0 , 0
   -12.4    .035       0       0    .035       0     8.9    .035       0
#XS Ineff= 2 , 0
               0   63.41     8.9           64.01
Permanent Ineff=
       F       F
Bank Sta=0,8.9
XS Rating Curve= 0
Exp/Cntr=.3,.1

Type RM Length L Ch R = 1 ,1250.00 ,50,50,50
BEGIN DESCRIPTION:
25
END DESCRIPTION:
#Sta/Elev= 10
   -12.4   62.42    -2.4   62.42       0   61.22      .6   59.62     6.6   59.62
     8.4   60.12     8.9   62.02     9.1   62.02    11.1   63.22    21.1   63.22
#Mann= 3 , 0 , 0
   -12.4    .035       0       0    .035       0     8.9    .035       0
#XS Ineff= 2 , 0
               0   61.22     8.9           62.02
Permanent Ineff=
       F       F
Bank Sta=0,8.9
XS Rating Curve= 0
Exp/Cntr=.3,.1

Type RM Length L Ch R = 1 ,1200.00 ,50,50,50
BEGIN DESCRIPTION:
24
END DESCRIPTION:
#Sta/Elev= 6
     -10   59.85       0   59.85     2.8   58.25     5.8   58.25     7.8   60.15
    17.8   60.15
#Mann= 3 , 0 , 0
     -10    .035       0       0    .035       0     7.8    .035       0
#XS Ineff= 2 , 0
               0   59.85     7.8           60.15
Permanent Ineff=
       F       F
Bank Sta=0,7.8
XS Rating Curve= 0
Exp/Cntr=.3,.1

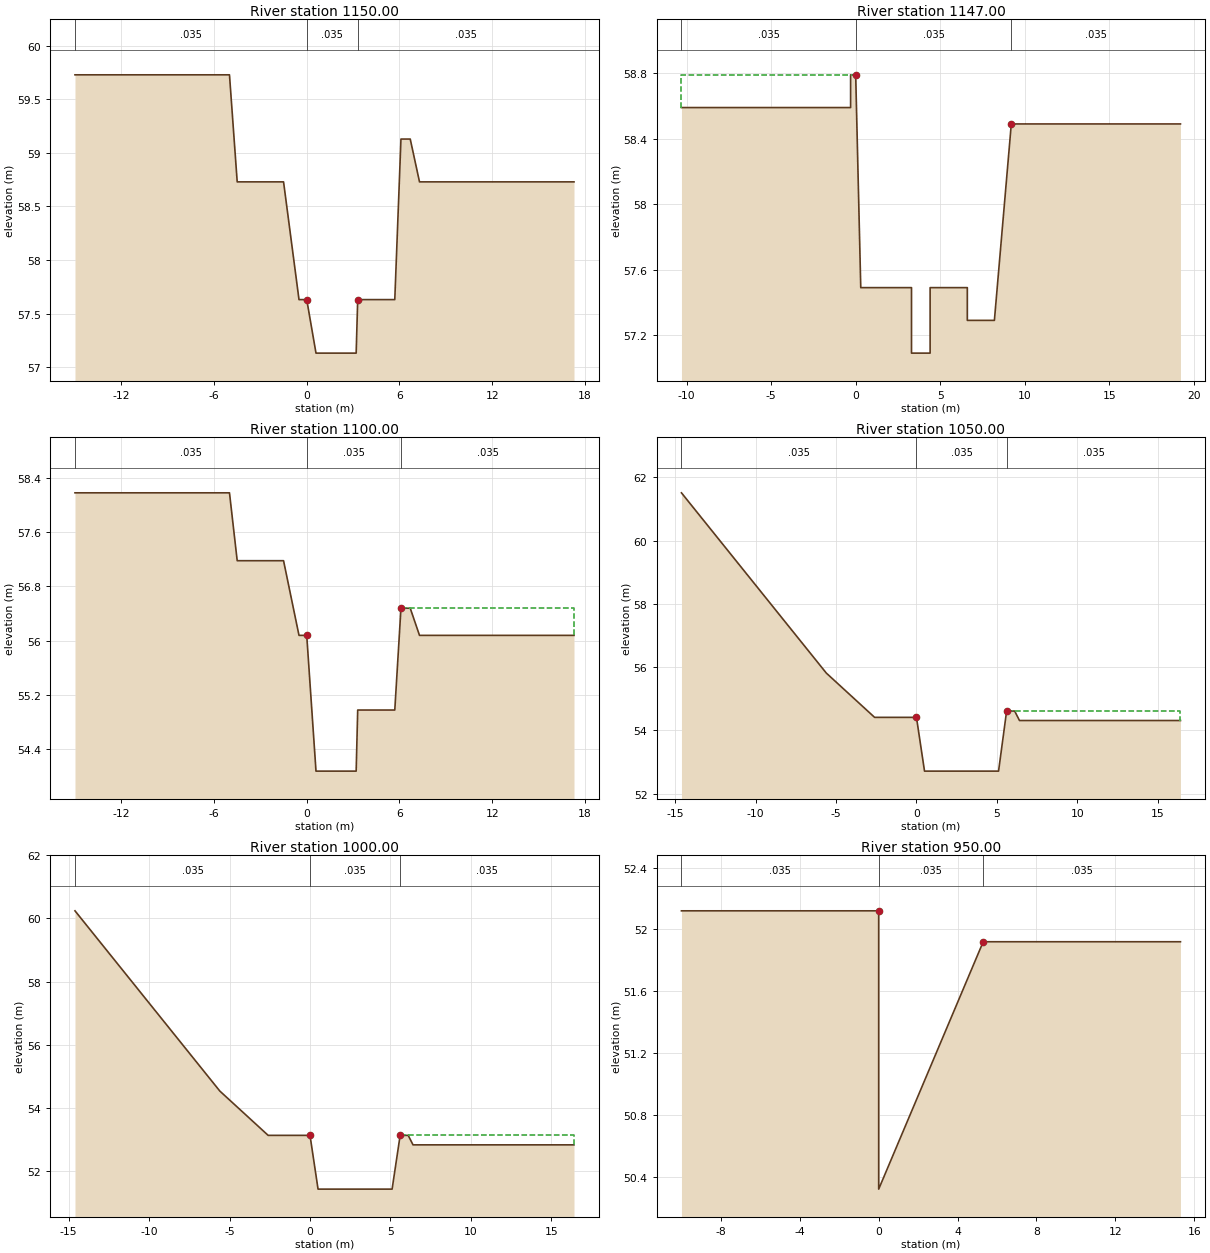
Type RM Length L Ch R = 1 ,1150.00 ,3,3,3
BEGIN DESCRIPTION:
23
END DESCRIPTION:
#Sta/Elev= 14
     -15   59.73      -5   59.73    -4.5   58.73    -1.5   58.73     -.5   57.63
       0   57.63      .6   57.13     3.2   57.13     3.3   57.63     5.7   57.63
     6.1   59.13     6.7   59.13     7.3   58.73    17.3   58.73
#Mann= 3 , 0 , 0
     -15    .035       0       0    .035       0     3.3    .035       0
#XS Ineff= 2 , 0
               0   57.63     3.3           57.63
Permanent Ineff=
       F       F
Bank Sta=0,3.3
XS Rating Curve= 0
Exp/Cntr=.3,.1

Type RM Length L Ch R = 1 ,1147.00 ,47,47,47
BEGIN DESCRIPTION:
22.047
END DESCRIPTION:
#Sta/Elev= 14
   -10.3   58.59     -.3   58.59     -.3   58.79       0   58.79      .3   57.49
     3.3   57.49     3.3   57.09     4.4   57.09     4.4   57.49     6.6   57.49
     6.6   57.29     8.2   57.29     9.2   58.49    19.2   58.49
#Mann= 3 , 0 , 0
   -10.3    .035       0       0    .035       0     9.2    .035       0
#XS Ineff= 2 , 0
               0   58.79     9.2           58.49
Permanent Ineff=
       F       F
Bank Sta=0,9.2
XS Rating Curve= 0
Exp/Cntr=.3,.1

Type RM Length L Ch R = 1 ,1100.00 ,50,50,50
BEGIN DESCRIPTION:
22
END DESCRIPTION:
#Sta/Elev= 14
     -15   58.18      -5   58.18    -4.5   57.18    -1.5   57.18     -.5   56.08
       0   56.08      .6   54.08     3.2   54.08     3.3   54.98     5.7   54.98
     6.1   56.48     6.7   56.48     7.3   56.08    17.3   56.08
#Mann= 3 , 0 , 0
     -15    .035       0       0    .035       0     6.1    .035       0
#XS Ineff= 2 , 0
               0   56.08     6.1           56.48
Permanent Ineff=
       F       F
Bank Sta=0,6.1
XS Rating Curve= 0
Exp/Cntr=.3,.1

Type RM Length L Ch R = 1 ,1050.00 ,50,50,50
BEGIN DESCRIPTION:
21
END DESCRIPTION:
#Sta/Elev= 12
   -14.6   61.51   -11.6   59.61    -8.6   57.71    -5.6   55.81    -2.6   54.41
       0   54.41      .5   52.71     5.1   52.71     5.6   54.61     6.1   54.61
     6.4   54.31    16.4   54.31
#Mann= 3 , 0 , 0
   -14.6    .035       0       0    .035       0     5.6    .035       0
#XS Ineff= 2 , 0
               0   54.41     5.6           54.61
Permanent Ineff=
       F       F
Bank Sta=0,5.6
XS Rating Curve= 0
Exp/Cntr=.3,.1

Type RM Length L Ch R = 1 ,1000.00 ,50,50,50
BEGIN DESCRIPTION:
20
END DESCRIPTION:
#Sta/Elev= 10
   -14.6   60.24    -5.6   54.54    -2.6   53.14       0   53.14      .5   51.44
     5.1   51.44     5.6   53.14     6.1   53.14     6.4   52.84    16.4   52.84
#Mann= 3 , 0 , 0
   -14.6    .035       0       0    .035       0     5.6    .035       0
#XS Ineff= 2 , 0
               0   53.14     5.6           53.14
Permanent Ineff=
       F       F
Bank Sta=0,5.6
XS Rating Curve= 0
Exp/Cntr=.3,.1

Type RM Length L Ch R = 1 ,950.00  ,18,18,18
BEGIN DESCRIPTION:
19
END DESCRIPTION:
#Sta/Elev= 5
     -10   52.12       0   52.12       0   50.32     5.3   51.92    15.3   51.92
#Mann= 3 , 0 , 0
     -10    .035       0       0    .035       0     5.3    .035       0
#XS Ineff= 2 , 0
               0   52.12     5.3           51.92
Permanent Ineff=
       F       F
Bank Sta=0,5.3
XS Rating Curve= 0
Exp/Cntr=.3,.1

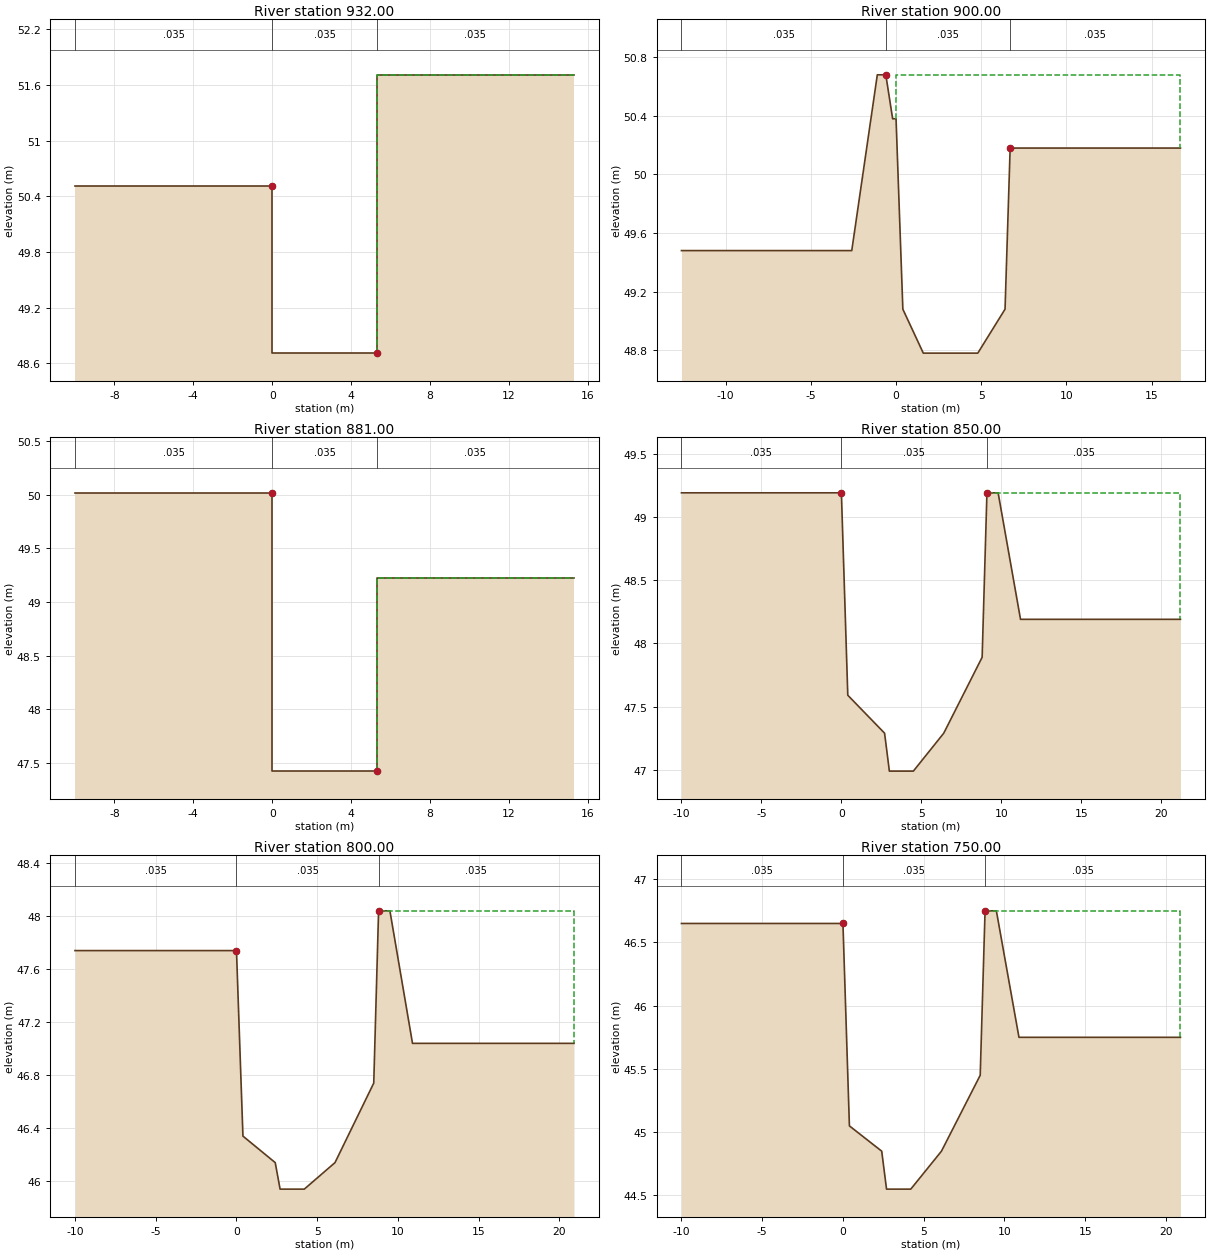
Type RM Length L Ch R = 1 ,932.00  ,32,32,32
BEGIN DESCRIPTION:
18.032
END DESCRIPTION:
#Sta/Elev= 6
     -10   50.51       0   50.51       0   48.71     5.3   48.71     5.3   51.71
    15.3   51.71
#Mann= 3 , 0 , 0
     -10    .035       0       0    .035       0     5.3    .035       0
#XS Ineff= 2 , 0
               0   50.51     5.3           51.71
Permanent Ineff=
       F       F
Bank Sta=0,5.3
XS Rating Curve= 0
Exp/Cntr=.3,.1

Type RM Length L Ch R = 1 ,900.00  ,19,19,19
BEGIN DESCRIPTION:
18
END DESCRIPTION:
#Sta/Elev= 12
   -12.6   49.48    -2.6   49.48    -1.1   50.68     -.6   50.68     -.2   50.38
       0   50.38      .4   49.08     1.6   48.78     4.8   48.78     6.4   49.08
     6.7   50.18    16.7   50.18
#Mann= 3 , 0 , 0
   -12.6    .035       0     -.6    .035       0     6.7    .035       0
#XS Ineff= 2 , 0
       0     -.6   50.68     6.7       0   50.18
Permanent Ineff=
       F       F
Bank Sta=-.6,6.7
XS Rating Curve= 0
Exp/Cntr=.3,.1

Type RM Length L Ch R = 1 ,881.00  ,31,31,31
BEGIN DESCRIPTION:
17.031
END DESCRIPTION:
#Sta/Elev= 6
     -10   50.02       0   50.02       0   47.42     5.3   47.42     5.3   49.22
    15.3   49.22
#Mann= 3 , 0 , 0
     -10    .035       0       0    .035       0     5.3    .035       0
#XS Ineff= 2 , 0
               0   50.02     5.3           49.22
Permanent Ineff=
       F       F
Bank Sta=0,5.3
XS Rating Curve= 0
Exp/Cntr=.3,.1

Type RM Length L Ch R = 1 ,850.00  ,50,50,50
BEGIN DESCRIPTION:
17
END DESCRIPTION:
#Sta/Elev= 12
     -10   49.19       0   49.19      .4   47.59     2.7   47.29       3   46.99
     4.5   46.99     6.4   47.29     8.8   47.89     9.1   49.19     9.8   49.19
    11.2   48.19    21.2   48.19
#Mann= 3 , 0 , 0
     -10    .035       0       0    .035       0     9.1    .035       0
#XS Ineff= 2 , 0
               0   49.19     9.1           49.19
Permanent Ineff=
       F       F
Bank Sta=0,9.1
XS Rating Curve= 0
Exp/Cntr=.3,.1

Type RM Length L Ch R = 1 ,800.00  ,50,50,50
BEGIN DESCRIPTION:
16
END DESCRIPTION:
#Sta/Elev= 12
     -10   47.74       0   47.74      .4   46.34     2.4   46.14     2.7   45.94
     4.2   45.94     6.1   46.14     8.5   46.74     8.8   48.04     9.5   48.04
    10.9   47.04    20.9   47.04
#Mann= 3 , 0 , 0
     -10    .035       0       0    .035       0     8.8    .035       0
#XS Ineff= 2 , 0
               0   47.74     8.8           48.04
Permanent Ineff=
       F       F
Bank Sta=0,8.8
XS Rating Curve= 0
Exp/Cntr=.3,.1

Type RM Length L Ch R = 1 ,750.00  ,44,44,44
BEGIN DESCRIPTION:
15
END DESCRIPTION:
#Sta/Elev= 12
     -10   46.65       0   46.65      .4   45.05     2.4   44.85     2.7   44.55
     4.2   44.55     6.1   44.85     8.5   45.45     8.8   46.75     9.5   46.75
    10.9   45.75    20.9   45.75
#Mann= 3 , 0 , 0
     -10    .035       0       0    .035       0     8.8    .035       0
#XS Ineff= 2 , 0
               0   46.65     8.8           46.75
Permanent Ineff=
       F       F
Bank Sta=0,8.8
XS Rating Curve= 0
Exp/Cntr=.3,.1

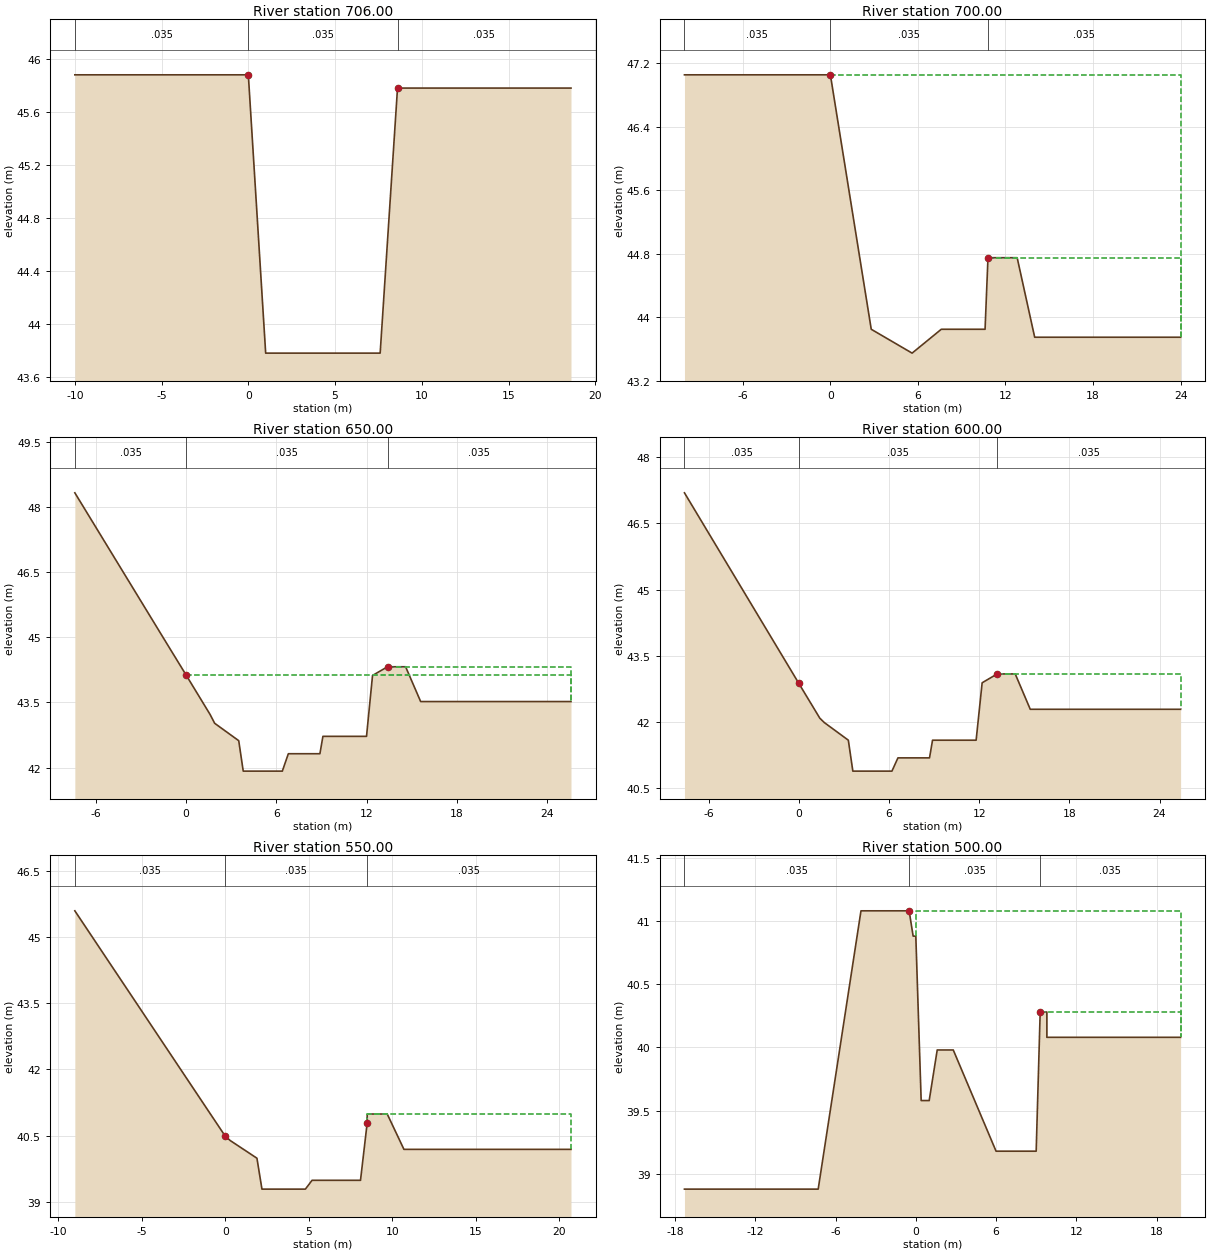
Type RM Length L Ch R = 1 ,706.00  ,6,6,6
BEGIN DESCRIPTION:
14.006
END DESCRIPTION:
#Sta/Elev= 6
     -10   45.88       0   45.88       1   43.78     7.6   43.78     8.6   45.78
    18.6   45.78
#Mann= 3 , 0 , 0
     -10    .035       0       0    .035       0     8.6    .035       0
#XS Ineff= 2 , 0
               0   45.88     8.6           45.78
Permanent Ineff=
       F       F
Bank Sta=0,8.6
XS Rating Curve= 0
Exp/Cntr=.3,.1

Type RM Length L Ch R = 1 ,700.00  ,50,50,50
BEGIN DESCRIPTION:
14
END DESCRIPTION:
#Sta/Elev= 10
     -10   47.05       0   47.05     2.8   43.85     5.6   43.55     7.6   43.85
    10.6   43.85    10.8   44.75    12.8   44.75      14   43.75      24   43.75
#Mann= 3 , 0 , 0
     -10    .035       0       0    .035       0    10.8    .035       0
#XS Ineff= 2 , 0
       0       0   47.05    10.8       0   44.75
Permanent Ineff=
       F       F
Bank Sta=0,10.8
XS Rating Curve= 0
Exp/Cntr=.3,.1

Type RM Length L Ch R = 1 ,650.00  ,50,50,50
BEGIN DESCRIPTION:
13
END DESCRIPTION:
#Sta/Elev= 18
    -7.4   48.32    -4.4   46.62    -1.4   44.92       0   44.13     1.6   43.22
     1.9   43.02     3.5   42.62     3.8   41.92     6.4   41.92     6.8   42.32
     8.9   42.32     9.1   42.72      12   42.72    12.4   44.12    13.4   44.32
    14.6   44.32    15.6   43.52    25.6   43.52
#Mann= 3 , 0 , 0
    -7.4    .035       0       0    .035       0    13.4    .035       0
#XS Ineff= 2 , 0
       0       0   44.13    13.4       0   44.32
Permanent Ineff=
       F       F
Bank Sta=0,13.4
XS Rating Curve= 0
Exp/Cntr=.3,.1

Type RM Length L Ch R = 1 ,600.00  ,50,50,50
BEGIN DESCRIPTION:
12
END DESCRIPTION:
#Sta/Elev= 16
    -7.6   47.19       0   42.88     1.4   42.09     1.7   41.99     3.3   41.59
     3.6   40.89     6.2   40.89     6.6   41.19     8.7   41.19     8.9   41.59
    11.8   41.59    12.2   42.89    13.2   43.09    14.4   43.09    15.4   42.29
    25.4   42.29
#Mann= 3 , 0 , 0
    -7.6    .035       0       0    .035       0    13.2    .035       0
#XS Ineff= 2 , 0
               0   42.88    13.2           43.09
Permanent Ineff=
       F       F
Bank Sta=0,13.2
XS Rating Curve= 0
Exp/Cntr=.3,.1

Type RM Length L Ch R = 1 ,550.00  ,50,50,50
BEGIN DESCRIPTION:
11
END DESCRIPTION:
#Sta/Elev= 15
      -9   45.59      -6   43.89      -3   42.19       0   40.49      .3   40.39
     1.9   39.99     2.2   39.29     4.8   39.29     5.2   39.49     8.1   39.49
     8.5   40.79     8.5   40.99     9.7   40.99    10.7   40.19    20.7   40.19
#Mann= 3 , 0 , 0
      -9    .035       0       0    .035       0     8.5    .035       0
#XS Ineff= 2 , 0
               0   40.49     8.5           40.99
Permanent Ineff=
       F       F
Bank Sta=0,8.5
XS Rating Curve= 0
Exp/Cntr=.3,.1

Type RM Length L Ch R = 1 ,500.00  ,50,50,50
BEGIN DESCRIPTION:
10
END DESCRIPTION:
#Sta/Elev= 16
   -17.3   38.88    -7.3   38.88    -4.1   41.08     -.5   41.08     -.2   40.88
       0   40.88      .4   39.58       1   39.58     1.6   39.98     2.8   39.98
       6   39.18       9   39.18     9.3   40.28     9.8   40.28     9.8   40.08
    19.8   40.08
#Mann= 3 , 0 , 0
   -17.3    .035       0     -.5    .035       0     9.3    .035       0
#XS Ineff= 2 , 0
       0     -.5   41.08     9.3       0   40.28
Permanent Ineff=
       F       F
Bank Sta=-.5,9.3
XS Rating Curve= 0
Exp/Cntr=.3,.1

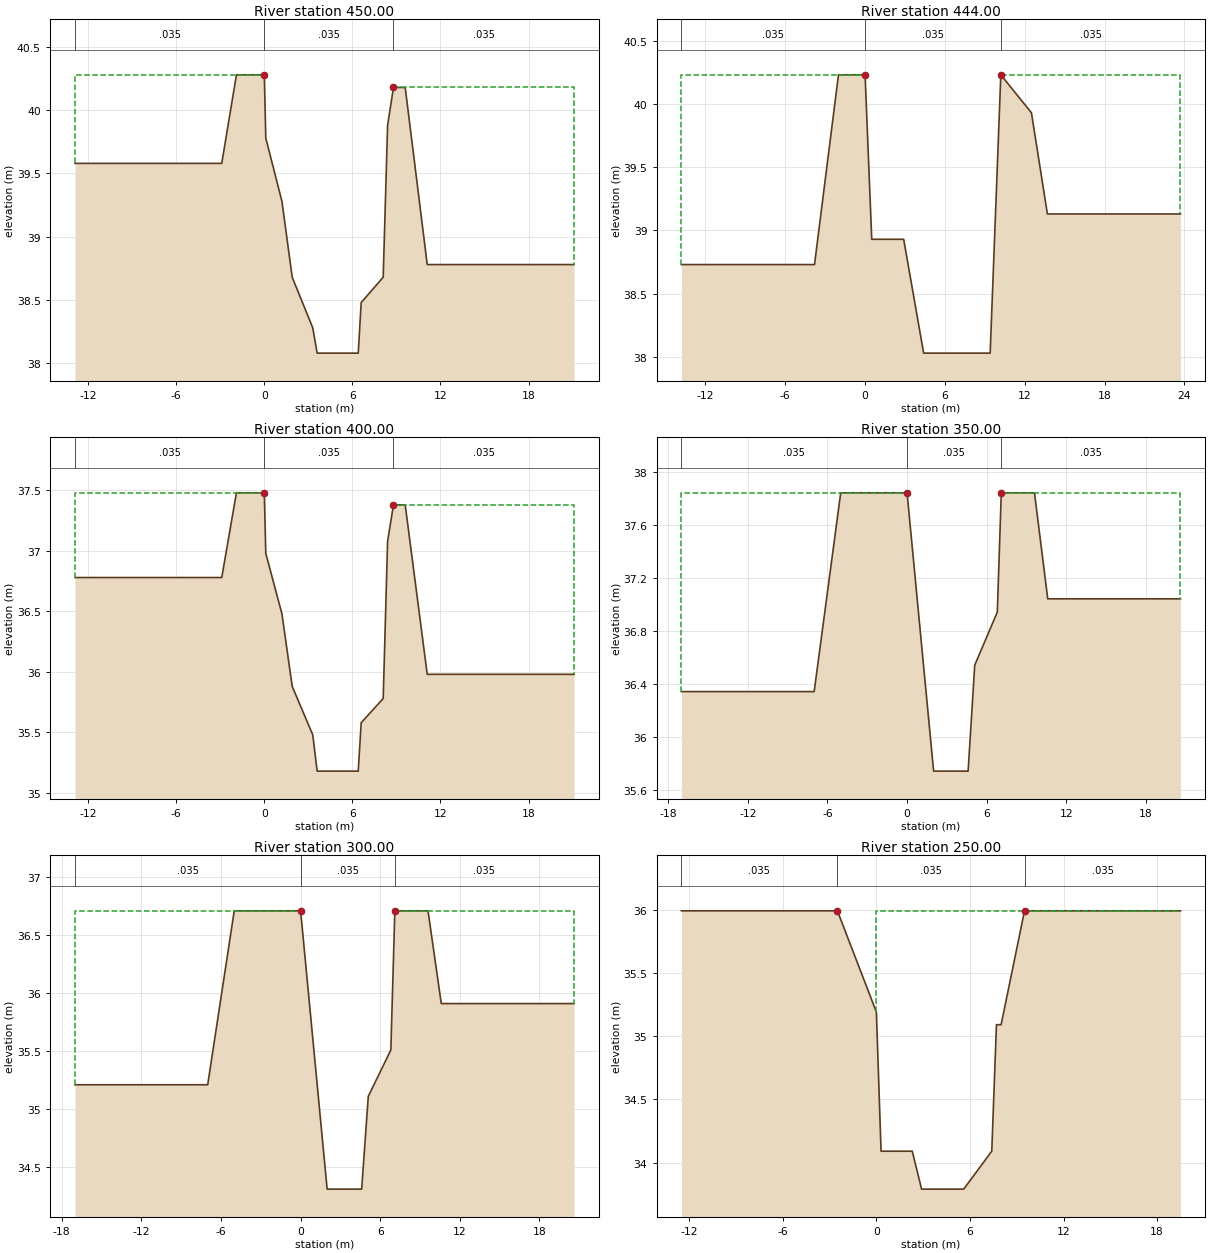
Type RM Length L Ch R = 1 ,450.00  ,6,6,6
BEGIN DESCRIPTION:
9
END DESCRIPTION:
#Sta/Elev= 17
   -12.9   39.58    -2.9   39.58    -1.9   40.28       0   40.28      .1   39.78
     1.2   39.28     1.9   38.68     3.3   38.28     3.6   38.08     6.4   38.08
     6.6   38.48     8.1   38.68     8.4   39.88     8.8   40.18     9.6   40.18
    11.1   38.78    21.1   38.78
#Mann= 3 , 0 , 0
   -12.9    .035       0       0    .035       0     8.8    .035       0
#XS Ineff= 2 , 0
               0   40.28     8.8           40.18
Permanent Ineff=
       F       F
Bank Sta=0,8.8
XS Rating Curve= 0
Exp/Cntr=.3,.1

Type RM Length L Ch R = 1 ,444.00  ,44,44,44
BEGIN DESCRIPTION:
8.044
END DESCRIPTION:
#Sta/Elev= 12
   -13.8   38.73    -3.8   38.73      -2   40.23       0   40.23      .5   38.93
     2.9   38.93     4.4   38.03     9.4   38.03    10.2   40.23    12.5   39.93
    13.7   39.13    23.7   39.13
#Mann= 3 , 0 , 0
   -13.8    .035       0       0    .035       0    10.2    .035       0
#XS Ineff= 2 , 0
               0   40.23    10.2           40.23
Permanent Ineff=
       F       F
Bank Sta=0,10.2
XS Rating Curve= 0
Exp/Cntr=.3,.1

Type RM Length L Ch R = 1 ,400.00  ,50,50,50
BEGIN DESCRIPTION:
8
END DESCRIPTION:
#Sta/Elev= 17
   -12.9   36.78    -2.9   36.78    -1.9   37.48       0   37.48      .1   36.98
     1.2   36.48     1.9   35.88     3.3   35.48     3.6   35.18     6.4   35.18
     6.6   35.58     8.1   35.78     8.4   37.08     8.8   37.38     9.6   37.38
    11.1   35.98    21.1   35.98
#Mann= 3 , 0 , 0
   -12.9    .035       0       0    .035       0     8.8    .035       0
#XS Ineff= 2 , 0
               0   37.48     8.8           37.38
Permanent Ineff=
       F       F
Bank Sta=0,8.8
XS Rating Curve= 0
Exp/Cntr=.3,.1

Type RM Length L Ch R = 1 ,350.00  ,50,50,50
BEGIN DESCRIPTION:
7
END DESCRIPTION:
#Sta/Elev= 12
     -17   36.34      -7   36.34      -5   37.84       0   37.84       2   35.74
     4.6   35.74     5.1   36.54     6.8   36.94     7.1   37.84     9.6   37.84
    10.6   37.04    20.6   37.04
#Mann= 3 , 0 , 0
     -17    .035       0       0    .035       0     7.1    .035       0
#XS Ineff= 2 , 0
               0   37.84     7.1           37.84
Permanent Ineff=
       F       F
Bank Sta=0,7.1
XS Rating Curve= 0
Exp/Cntr=.3,.1

Type RM Length L Ch R = 1 ,300.00  ,50,50,50
BEGIN DESCRIPTION:
6
END DESCRIPTION:
#Sta/Elev= 12
     -17   35.21      -7   35.21      -5   36.71       0   36.71       2   34.31
     4.6   34.31     5.1   35.11     6.8   35.51     7.1   36.71     9.6   36.71
    10.6   35.91    20.6   35.91
#Mann= 3 , 0 , 0
     -17    .035       0       0    .035       0     7.1    .035       0
#XS Ineff= 2 , 0
               0   36.71     7.1           36.71
Permanent Ineff=
       F       F
Bank Sta=0,7.1
XS Rating Curve= 0
Exp/Cntr=.3,.1

Type RM Length L Ch R = 1 ,250.00  ,50,50,50
BEGIN DESCRIPTION:
5
END DESCRIPTION:
#Sta/Elev= 12
   -12.5   35.99    -2.5   35.99       0   35.19      .3   34.09     2.3   34.09
     2.9   33.79     5.6   33.79     7.4   34.09     7.7   35.09       8   35.09
     9.5   35.99    19.5   35.99
#Mann= 3 , 0 , 0
   -12.5    .035       0    -2.5    .035       0     9.5    .035       0
#XS Ineff= 2 , 0
       0    -2.5   35.99     9.5       0   35.99
Permanent Ineff=
       F       F
Bank Sta=-2.5,9.5
XS Rating Curve= 0
Exp/Cntr=.3,.1

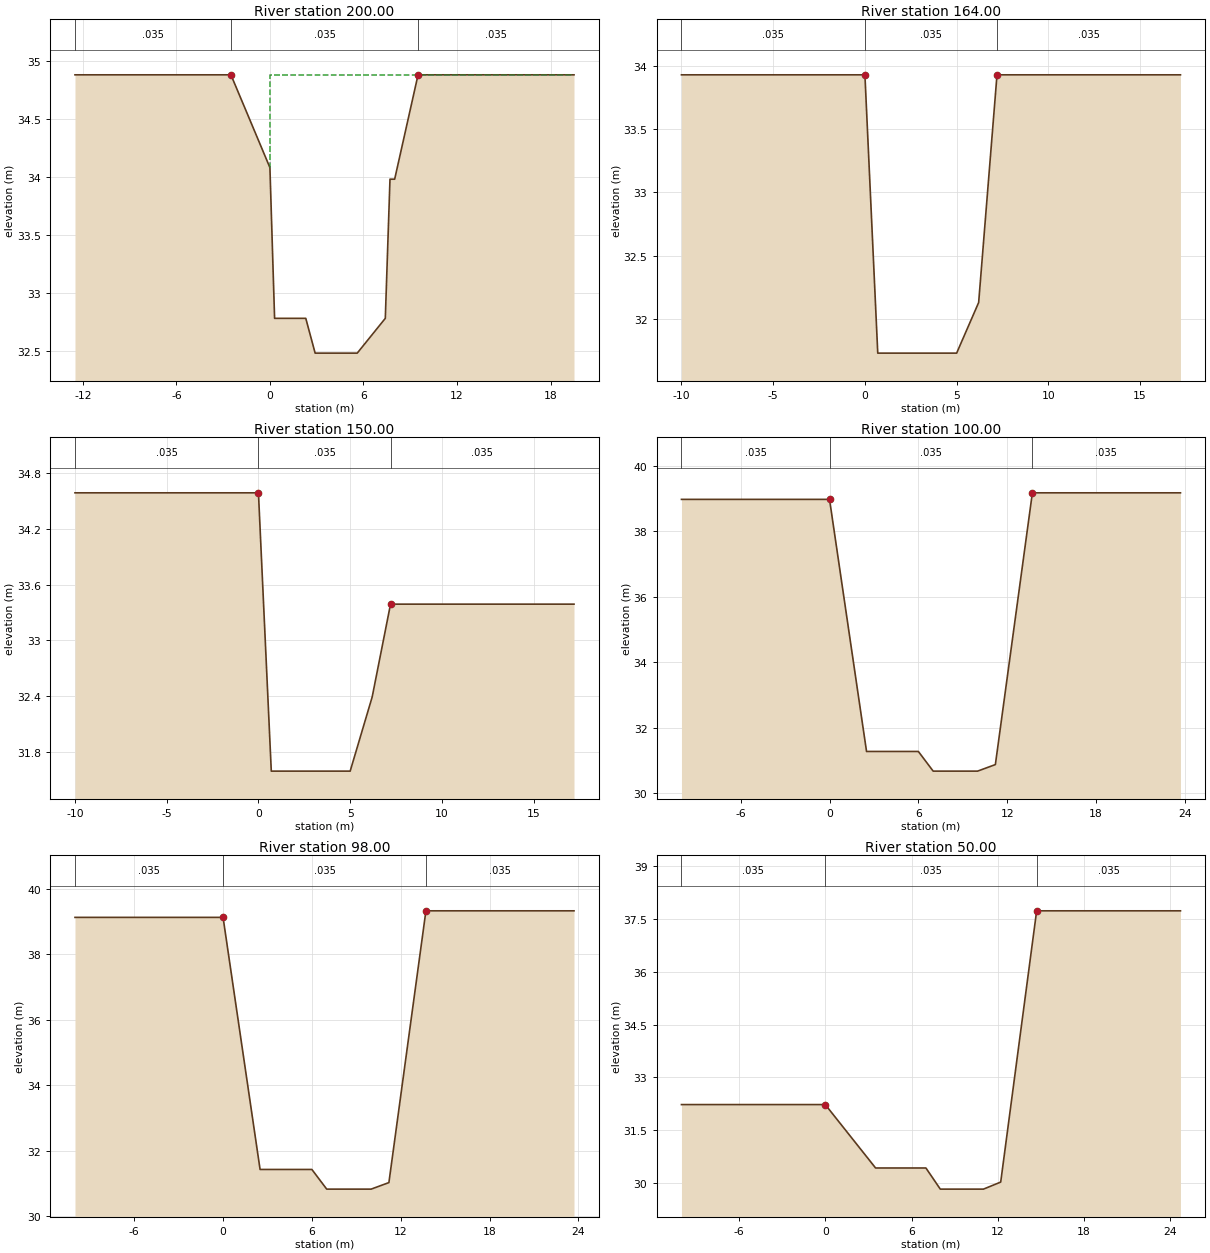
Type RM Length L Ch R = 1 ,200.00  ,36,36,36
BEGIN DESCRIPTION:
4
END DESCRIPTION:
#Sta/Elev= 12
   -12.5   34.88    -2.5   34.88       0   34.08      .3   32.78     2.3   32.78
     2.9   32.48     5.6   32.48     7.4   32.78     7.7   33.98       8   33.98
     9.5   34.88    19.5   34.88
#Mann= 3 , 0 , 0
   -12.5    .035       0    -2.5    .035       0     9.5    .035       0
#XS Ineff= 2 , 0
       0    -2.5   34.88     9.5       0   34.88
Permanent Ineff=
       F       F
Bank Sta=-2.5,9.5
XS Rating Curve= 0
Exp/Cntr=.3,.1

Type RM Length L Ch R = 1 ,164.00  ,14,14,14
BEGIN DESCRIPTION:
3.014
END DESCRIPTION:
#Sta/Elev= 7
     -10   33.93       0   33.93      .7   31.73       5   31.73     6.2   32.13
     7.2   33.93    17.2   33.93
#Mann= 3 , 0 , 0
     -10    .035       0       0    .035       0     7.2    .035       0
#XS Ineff= 2 , 0
               0   33.93     7.2           33.93
Permanent Ineff=
       F       F
Bank Sta=0,7.2
XS Rating Curve= 0
Exp/Cntr=.3,.1

Type RM Length L Ch R = 1 ,150.00  ,50,50,50
BEGIN DESCRIPTION:
3
END DESCRIPTION:
#Sta/Elev= 7
     -10   34.59       0   34.59      .7   31.59       5   31.59     6.2   32.39
     7.2   33.39    17.2   33.39
#Mann= 3 , 0 , 0
     -10    .035       0       0    .035       0     7.2    .035       0
#XS Ineff= 2 , 0
               0   34.59     7.2           33.39
Permanent Ineff=
       F       F
Bank Sta=0,7.2
XS Rating Curve= 0
Exp/Cntr=.3,.1

Type RM Length L Ch R = 1 ,100.00  ,2,2,2
BEGIN DESCRIPTION:
2
END DESCRIPTION:
#Sta/Elev= 9
     -10   38.97       0   38.97     2.5   31.27       6   31.27       7   30.67
      10   30.67    11.2   30.87    13.7   39.17    23.7   39.17
#Mann= 3 , 0 , 0
     -10    .035       0       0    .035       0    13.7    .035       0
#XS Ineff= 2 , 0
               0   38.97    13.7           39.17
Permanent Ineff=
       F       F
Bank Sta=0,13.7
XS Rating Curve= 0
Exp/Cntr=.3,.1

Type RM Length L Ch R = 1 ,98.00   ,48,48,48
BEGIN DESCRIPTION:
1.048
END DESCRIPTION:
#Sta/Elev= 9
     -10   39.13       0   39.13     2.5   31.43       6   31.43       7   30.83
      10   30.83    11.2   31.03    13.7   39.33    23.7   39.33
#Mann= 3 , 0 , 0
     -10    .035       0       0    .035       0    13.7    .035       0
#XS Ineff= 2 , 0
               0   39.13    13.7           39.33
Permanent Ineff=
       F       F
Bank Sta=0,13.7
XS Rating Curve= 0
Exp/Cntr=.3,.1

Type RM Length L Ch R = 1 ,50.00   ,50,50,50
BEGIN DESCRIPTION:
1
END DESCRIPTION:
#Sta/Elev= 9
     -10   32.23       0   32.23     3.5   30.43       7   30.43       8   29.83
      11   29.83    12.2   30.03    14.7   37.73    24.7   37.73
#Mann= 3 , 0 , 0
     -10    .035       0       0    .035       0    14.7    .035       0
#XS Ineff= 2 , 0
               0   32.23    14.7           37.73
Permanent Ineff=
       F       F
Bank Sta=0,14.7
XS Rating Curve= 0
Exp/Cntr=.3,.1

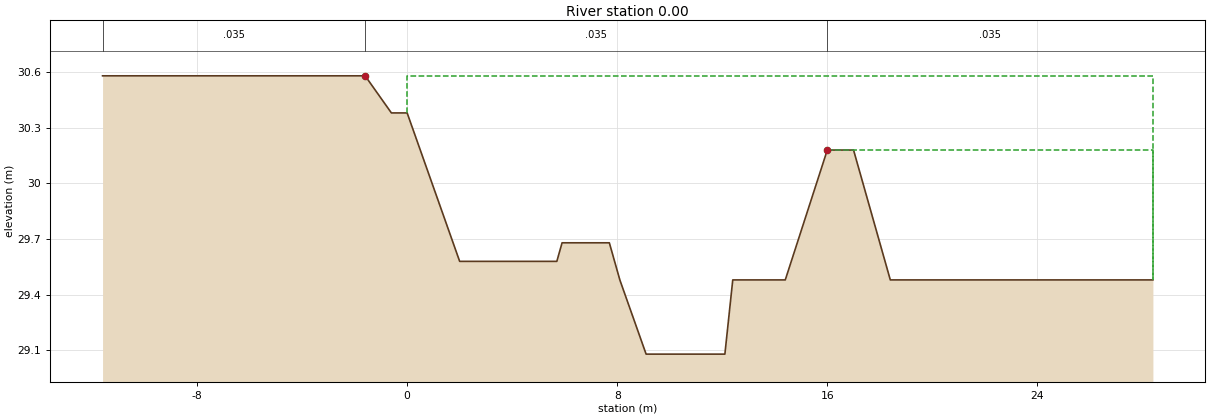
Type RM Length L Ch R = 1 ,0.00    ,0,0,0
BEGIN DESCRIPTION:
0
END DESCRIPTION:
#Sta/Elev= 17
   -11.6   30.58    -1.6   30.58     -.6   30.38       0   30.38       2   29.58
     5.7   29.58     5.9   29.68     7.7   29.68     8.1   29.48     9.1   29.08
    12.1   29.08    12.4   29.48    14.4   29.48      16   30.18      17   30.18
    18.4   29.48    28.4   29.48
#Mann= 3 , 0 , 0
   -11.6    .035       0    -1.6    .035       0      16    .035       0
#XS Ineff= 2 , 0
       0    -1.6   30.58      16       0   30.18
Permanent Ineff=
       F       F
Bank Sta=-1.6,16
XS Rating Curve= 0
Exp/Cntr=.3,.1

Chan Stop Cuts=-1