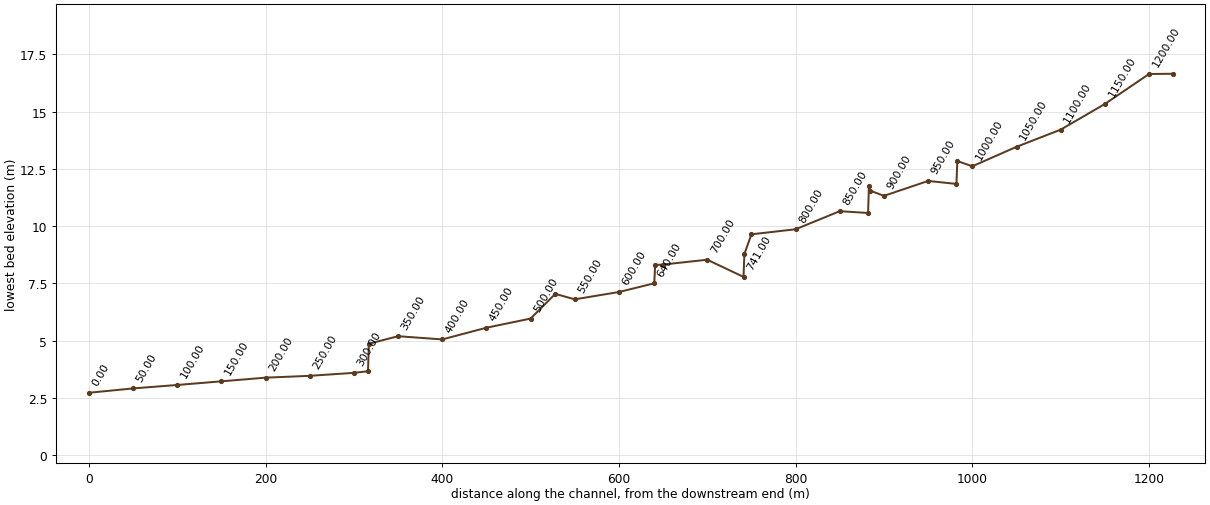
--- DAE.prj (project) ---

Proj Title=deya-chon
Current Plan=p01
Default Exp/Contr=.3,.1
SI Units
Geom File=g01
Flow File=f01
Plan File=p01
Y Axis Title=Elevation
X Axis Title(PF)=Main Channel Distance
X Axis Title(XS)=Station
BEGIN DESCRIPTION:
           BACK WATER COMPUTATION
      APPLICATION OF HEC-2 BY Samju Construction Engineering
      deya-chon: 10,20,30,50,80 yr
END DESCRIPTION:
DSS Export Rating Curves= 0
DSS Export Rating Curve Sorted= 0
DSS Export Volume Flow Curves= 0
DXF OffsetX= 0
DXF OffsetY= 0
DXF ScaleX= 1
DXF ScaleY= 10

--- DAE.p01 (plan) ---

Plan Title=Imported Plan 01
Version=Version 3.0.1  Mar 2001
Short Identifier=Imported Pla
Geom File=g01
Flow File=f01
Subcritical Flow
K Sum by GR= 0
Std Step Tol= 0.003
Critical Tol= 0.003
Num of Std Step Trials= 20
Max Error Tol= 0.1
Flow Tol Ratio= 0.001
Split Flow NTrial= 30
Split Flow Tol= 0.02
Split Flow Ratio= 0.02
Log Output Level= 0
Friction Slope Method= 1
Unsteady Friction Slope Method= 2
Parabolic Critical Depth
Global Vel Dist= 0 , 0 , 0
Global Log Level= 0
CheckData=True
Encroach Param=-1 ,0,0, 0
Computation Interval=1HOUR
Output Interval=1HOUR
Run HTab= 0
Run UNet= 0
Run PostProcess= 0
UNET Theta= 1
UNET ZTol= 0.02
UNET ZSATol= 0.1
UNET MxIter= 20
UNET MaxInSteps= 20
UNET DtIC= 0
UNET DtMin= 0
UNET MaxCRTS= 20
UNET WFStab= 2
UNET SFStab= 1
UNET WFX= 1
UNET SFX= 1
UNET Convert EG Bridges=-1
UNET Use Existing IB Tables=-1
Instantaneous Interval=1HOUR
Write IC File= 0
Write Velocity= 0
Write Detailed= 0

--- DAE.f01 (steady flow) ---

Flow Title=Imported Flow 01
Version=Version 3.0.1  Mar 2001
Number of Profiles= 5
Profile Names=10YR,20YR,30YR,50YR,80YR
River Rch & RM=RIVER-1,Reach-1         ,24.027
   30.56   33.68    35.5    37.8   39.91
River Rch & RM=NAMPO,NAMPO           ,24.027
   30.56   33.68    35.5    37.8   39.91
River Rch & RM=DAEYA,DAEYA           ,1227.00
   30.56   33.68    35.5    37.8   39.91
Boundary for River Rch & Prof#=DAEYA,DAEYA           , 1
Up Type= 0
Dn Type= 3
Dn Slope=.012
Boundary for River Rch & Prof#=DAEYA,DAEYA           , 2
Up Type= 0
Dn Type= 3
Dn Slope=.012
Boundary for River Rch & Prof#=DAEYA,DAEYA           , 3
Up Type= 0
Dn Type= 3
Dn Slope=.012
Boundary for River Rch & Prof#=DAEYA,DAEYA           , 4
Up Type= 0
Dn Type= 3
Dn Slope=.012
Boundary for River Rch & Prof#=DAEYA,DAEYA           , 5
Up Type= 0
Dn Type= 3
Dn Slope=.012
DSS Import GetInterval= 0
DSS Import GetPeak= 0
DSS Import FillOption= 0

--- DAE.g01 (geometry) ---

Geom Title=Imported Geom 01
Version=Version 3.0.1  Mar 2001

River Reach=DAEYA           ,DAEYA
Reach XY= 2
              .5             .95              .5             .05

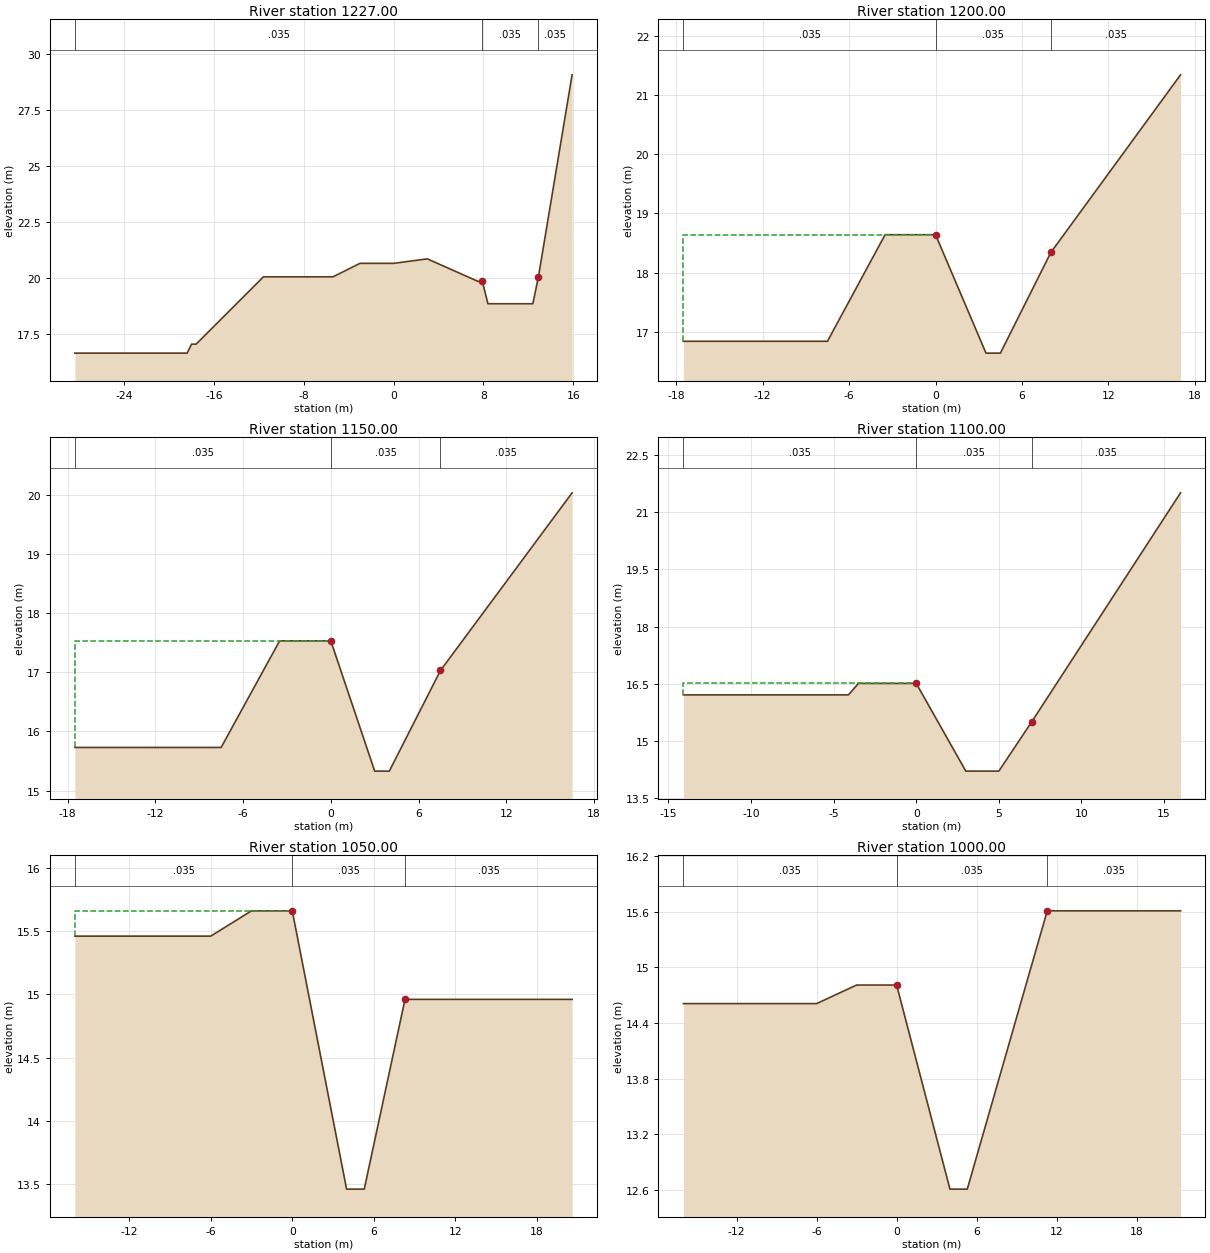
Type RM Length L Ch R = 1 ,1227.00 ,27,27,27
BEGIN DESCRIPTION:
24.027
END DESCRIPTION:
#Sta/Elev= 17
   -28.4   16.65   -18.4   16.65     -18   17.05   -17.6   17.05   -11.6   20.05
    -5.4   20.05      -3   20.65       0   20.65       3   20.85     7.5   19.85
     7.9   19.85     8.4   18.85    12.4   18.85    12.9   20.05    13.9   23.05
    14.9   26.05    15.9   29.05
#Mann= 3 , 0 , 0
   -28.4    .035       0     7.9    .035       0    12.9    .035       0
#XS Ineff= 2 , 0
       0     7.9   19.85    12.9       0   20.05
Permanent Ineff=
       F       F
Bank Sta=7.9,12.9
XS Rating Curve= 0
Exp/Cntr=.3,.1

Type RM Length L Ch R = 1 ,1200.00 ,50,50,50
BEGIN DESCRIPTION:
24
END DESCRIPTION:
#Sta/Elev= 11
   -17.5   16.84    -7.5   16.84    -3.5   18.64     -.5   18.64       0   18.64
     3.5   16.64     4.5   16.64       8   18.34      11   19.34      14   20.34
      17   21.34
#Mann= 3 , 0 , 0
   -17.5    .035       0       0    .035       0       8    .035       0
#XS Ineff= 2 , 0
               0   18.64       8           18.34
Permanent Ineff=
       F       F
Bank Sta=0,8
XS Rating Curve= 0
Exp/Cntr=.3,.1

Type RM Length L Ch R = 1 ,1150.00 ,50,50,50
BEGIN DESCRIPTION:
23
END DESCRIPTION:
#Sta/Elev= 11
   -17.5   15.73    -7.5   15.73    -3.5   17.53     -.5   17.53       0   17.53
       3   15.33       4   15.33     7.5   17.03    10.5   18.03    13.5   19.03
    16.5   20.03
#Mann= 3 , 0 , 0
   -17.5    .035       0       0    .035       0     7.5    .035       0
#XS Ineff= 2 , 0
               0   17.53     7.5           17.03
Permanent Ineff=
       F       F
Bank Sta=0,7.5
XS Rating Curve= 0
Exp/Cntr=.3,.1

Type RM Length L Ch R = 1 ,1100.00 ,50,50,50
BEGIN DESCRIPTION:
22
END DESCRIPTION:
#Sta/Elev= 11
   -14.1   16.21    -4.1   16.21    -3.5   16.51     -.5   16.51       0   16.51
       3   14.21       5   14.21       7   15.51      10   17.51      13   19.51
      16   21.51
#Mann= 3 , 0 , 0
   -14.1    .035       0       0    .035       0       7    .035       0
#XS Ineff= 2 , 0
               0   16.51       7           15.51
Permanent Ineff=
       F       F
Bank Sta=0,7
XS Rating Curve= 0
Exp/Cntr=.3,.1

Type RM Length L Ch R = 1 ,1050.00 ,50,50,50
BEGIN DESCRIPTION:
21
END DESCRIPTION:
#Sta/Elev= 9
     -16   15.46      -6   15.46      -3   15.66       0   15.66       4   13.46
     5.3   13.46     8.3   14.96    10.6   14.96    20.6   14.96
#Mann= 3 , 0 , 0
     -16    .035       0       0    .035       0     8.3    .035       0
#XS Ineff= 2 , 0
               0   15.66     8.3           14.96
Permanent Ineff=
       F       F
Bank Sta=0,8.3
XS Rating Curve= 0
Exp/Cntr=.3,.1

Type RM Length L Ch R = 1 ,1000.00 ,17,17,17
BEGIN DESCRIPTION:
20
END DESCRIPTION:
#Sta/Elev= 9
     -16   14.61      -6   14.61      -3   14.81       0   14.81       4   12.61
     5.3   12.61     8.3   14.11    11.3   15.61    21.3   15.61
#Mann= 3 , 0 , 0
     -16    .035       0       0    .035       0    11.3    .035       0
#XS Ineff= 2 , 0
       0       0   14.81    11.3       0   15.61
Permanent Ineff=
       F       F
Bank Sta=0,11.3
XS Rating Curve= 0
Exp/Cntr=.3,.1

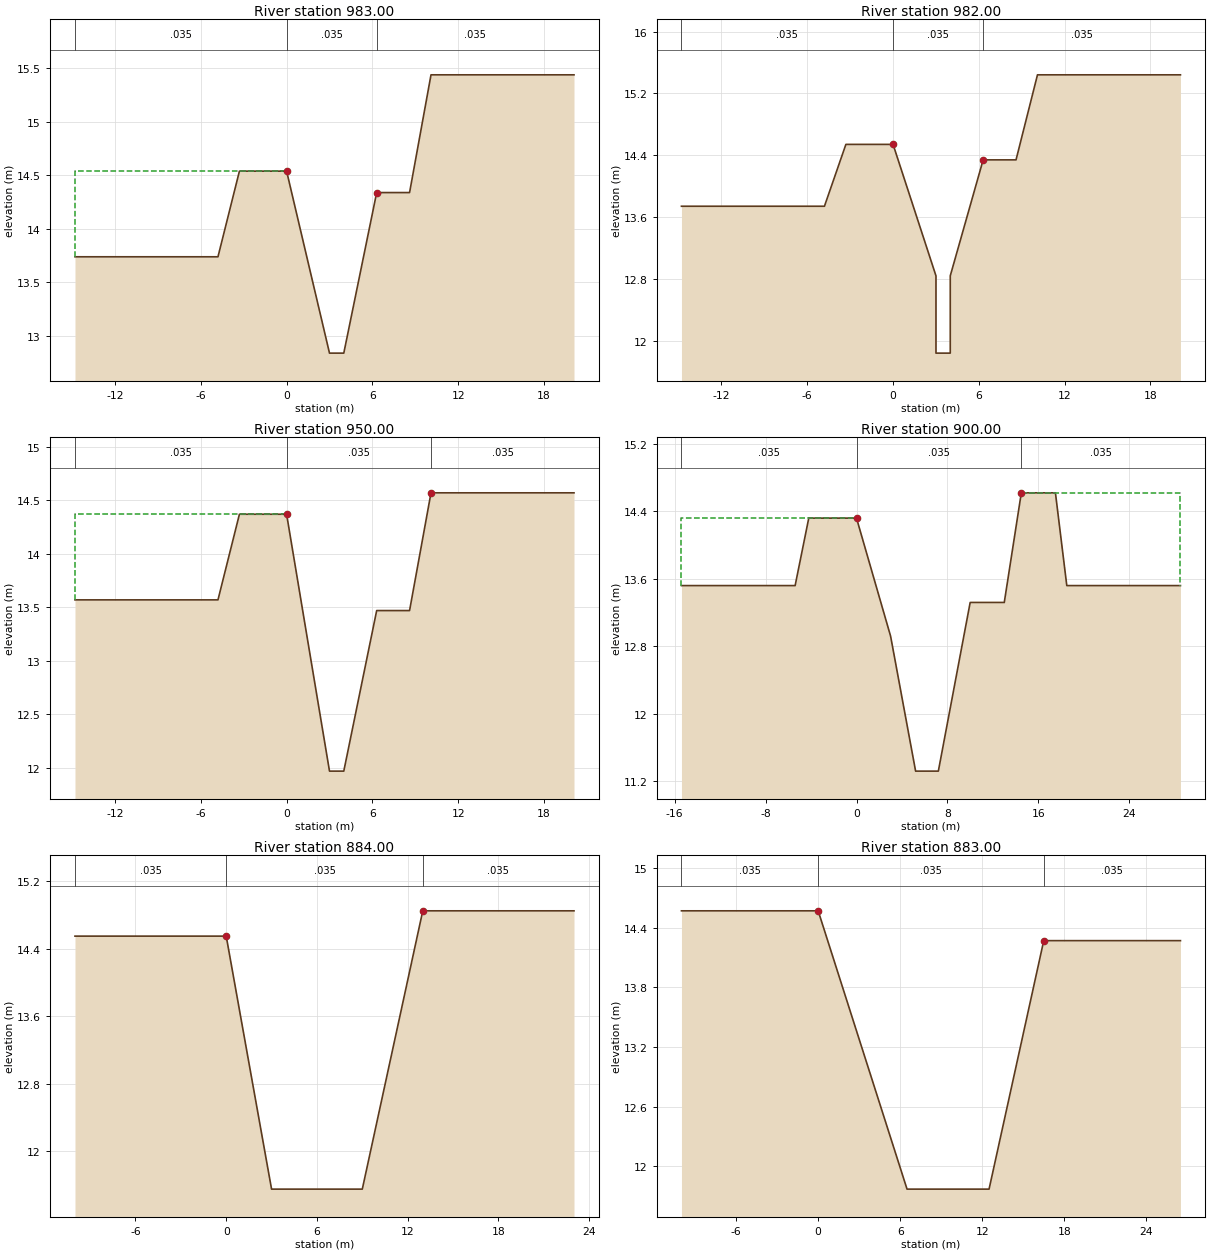
Type RM Length L Ch R = 1 ,983.00  ,1,1,1
BEGIN DESCRIPTION:
19.033
END DESCRIPTION:
#Sta/Elev= 11
   -14.8   13.74    -4.8   13.74    -3.3   14.54     -.3   14.54       0   14.54
       3   12.84       4   12.84     6.3   14.34     8.6   14.34    10.1   15.44
    20.1   15.44
#Mann= 3 , 0 , 0
   -14.8    .035       0       0    .035       0     6.3    .035       0
#XS Ineff= 2 , 0
               0   14.54     6.3           14.34
Permanent Ineff=
       F       F
Bank Sta=0,6.3
XS Rating Curve= 0
Exp/Cntr=.3,.1

Type RM Length L Ch R = 1 ,982.00  ,32,32,32
BEGIN DESCRIPTION:
19.032
END DESCRIPTION:
#Sta/Elev= 13
   -14.8   13.74    -4.8   13.74    -3.3   14.54     -.3   14.54       0   14.54
       3   12.84       3   11.84       4   11.84       4   12.84     6.3   14.34
     8.6   14.34    10.1   15.44    20.1   15.44
#Mann= 3 , 0 , 0
   -14.8    .035       0       0    .035       0     6.3    .035       0
#XS Ineff= 2 , 0
       0       0   14.54     6.3       0   14.34
Permanent Ineff=
       F       F
Bank Sta=0,6.3
XS Rating Curve= 0
Exp/Cntr=.3,.1

Type RM Length L Ch R = 1 ,950.00  ,50,50,50
BEGIN DESCRIPTION:
19
END DESCRIPTION:
#Sta/Elev= 11
   -14.8   13.57    -4.8   13.57    -3.3   14.37     -.3   14.37       0   14.37
       3   11.97       4   11.97     6.3   13.47     8.6   13.47    10.1   14.57
    20.1   14.57
#Mann= 3 , 0 , 0
   -14.8    .035       0       0    .035       0    10.1    .035       0
#XS Ineff= 2 , 0
               0   14.37    10.1           14.57
Permanent Ineff=
       F       F
Bank Sta=0,10.1
XS Rating Curve= 0
Exp/Cntr=.3,.1

Type RM Length L Ch R = 1 ,900.00  ,16,16,16
BEGIN DESCRIPTION:
18
END DESCRIPTION:
#Sta/Elev= 15
   -15.4   13.52    -5.4   13.52    -4.2   14.32    -3.5   14.32     -.5   14.32
       0   14.32       3   12.92     5.2   11.32     7.2   11.32      10   13.32
      13   13.32    14.5   14.62    17.5   14.62    18.5   13.52    28.5   13.52
#Mann= 3 , 0 , 0
   -15.4    .035       0       0    .035       0    14.5    .035       0
#XS Ineff= 2 , 0
               0   14.32    14.5           14.62
Permanent Ineff=
       F       F
Bank Sta=0,14.5
XS Rating Curve= 0
Exp/Cntr=.3,.1

Type RM Length L Ch R = 1 ,884.00  ,1,1,1
BEGIN DESCRIPTION:
17.034
END DESCRIPTION:
#Sta/Elev= 6
     -10   14.55       0   14.55       3   11.55       9   11.55      13   14.85
      23   14.85
#Mann= 3 , 0 , 0
     -10    .035       0       0    .035       0      13    .035       0
#XS Ineff= 2 , 0
               0   14.55      13           14.85
Permanent Ineff=
       F       F
Bank Sta=0,13
XS Rating Curve= 0
Exp/Cntr=.3,.1

Type RM Length L Ch R = 1 ,883.00  ,1,1,1
BEGIN DESCRIPTION:
17.033
END DESCRIPTION:
#Sta/Elev= 6
     -10   14.57       0   14.57     6.5   11.77    12.5   11.77    16.5   14.27
    26.5   14.27
#Mann= 3 , 0 , 0
     -10    .035       0       0    .035       0    16.5    .035       0
#XS Ineff= 2 , 0
               0   14.57    16.5           14.27
Permanent Ineff=
       F       F
Bank Sta=0,16.5
XS Rating Curve= 0
Exp/Cntr=.3,.1

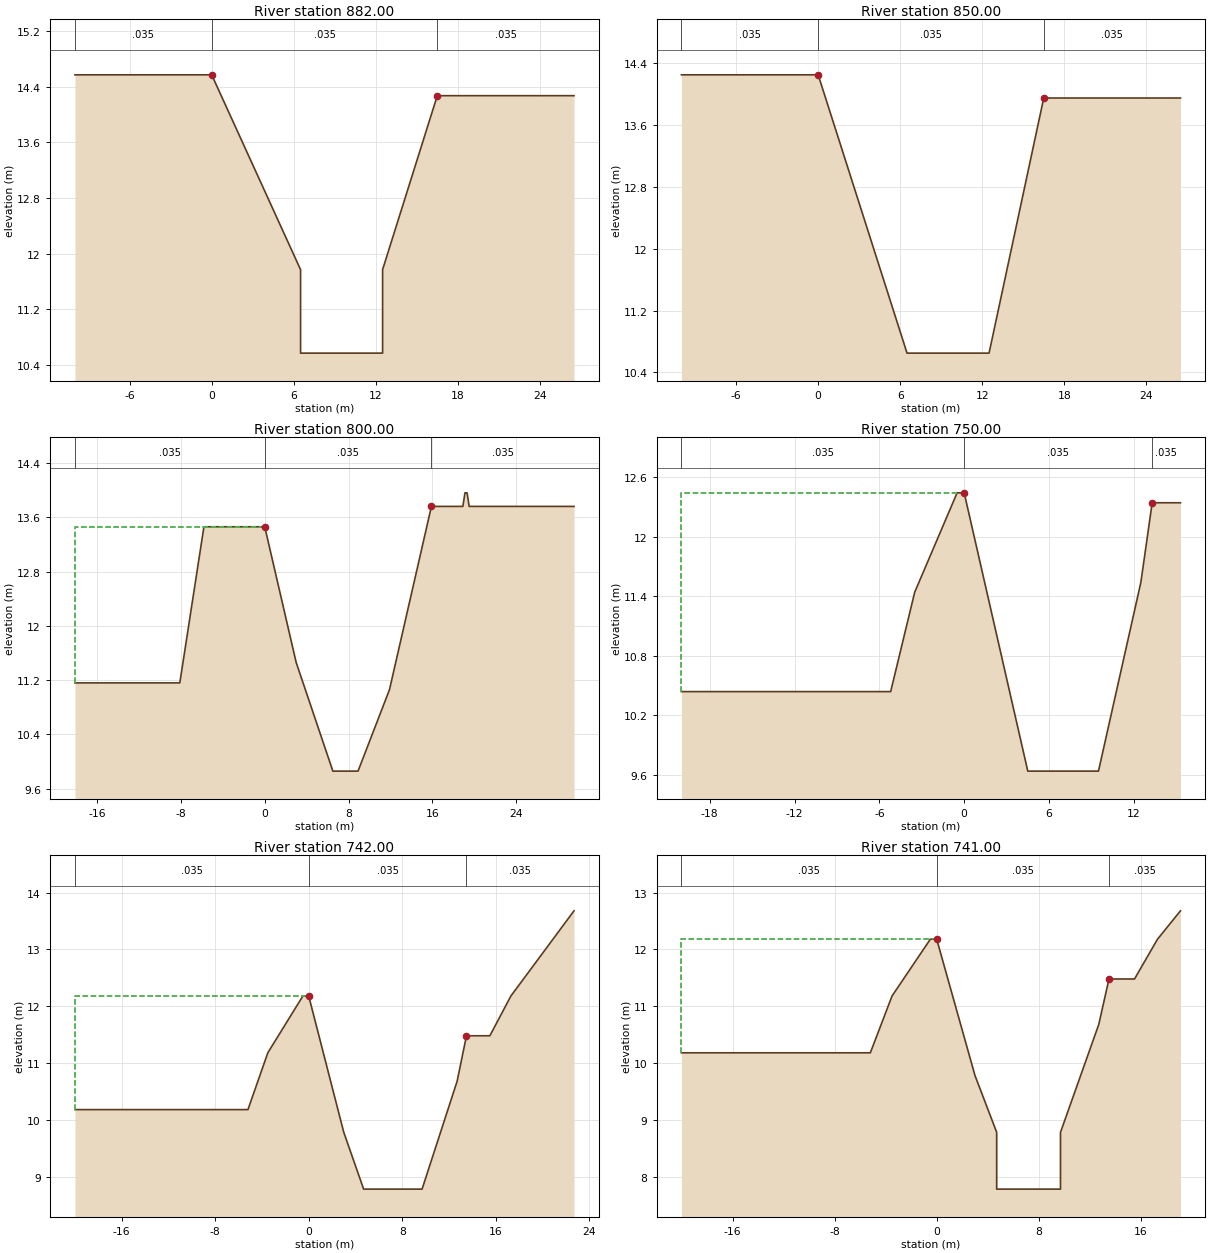
Type RM Length L Ch R = 1 ,882.00  ,32,32,32
BEGIN DESCRIPTION:
17.032
END DESCRIPTION:
#Sta/Elev= 8
     -10   14.57       0   14.57     6.5   11.77     6.5   10.57    12.5   10.57
    12.5   11.77    16.5   14.27    26.5   14.27
#Mann= 3 , 0 , 0
     -10    .035       0       0    .035       0    16.5    .035       0
#XS Ineff= 2 , 0
               0   14.57    16.5           14.27
Permanent Ineff=
       F       F
Bank Sta=0,16.5
XS Rating Curve= 0
Exp/Cntr=.3,.1

Type RM Length L Ch R = 1 ,850.00  ,50,50,50
BEGIN DESCRIPTION:
17
END DESCRIPTION:
#Sta/Elev= 6
     -10   14.25       0   14.25     6.5   10.65    12.5   10.65    16.5   13.95
    26.5   13.95
#Mann= 3 , 0 , 0
     -10    .035       0       0    .035       0    16.5    .035       0
#XS Ineff= 2 , 0
               0   14.25    16.5           13.95
Permanent Ineff=
       F       F
Bank Sta=0,16.5
XS Rating Curve= 0
Exp/Cntr=.3,.1

Type RM Length L Ch R = 1 ,800.00  ,50,50,50
BEGIN DESCRIPTION:
16
END DESCRIPTION:
#Sta/Elev= 16
   -18.1   11.16    -8.1   11.16    -5.8   13.46    -5.3   13.46     -.5   13.46
       0   13.46       3   11.46     6.5    9.86     8.9    9.86    11.9   11.06
    15.9   13.76    18.9   13.76    19.1   13.96    19.3   13.96    19.5   13.76
    29.5   13.76
#Mann= 3 , 0 , 0
   -18.1    .035       0       0    .035       0    15.9    .035       0
#XS Ineff= 2 , 0
               0   13.46    15.9           13.76
Permanent Ineff=
       F       F
Bank Sta=0,15.9
XS Rating Curve= 0
Exp/Cntr=.3,.1

Type RM Length L Ch R = 1 ,750.00  ,8,8,8
BEGIN DESCRIPTION:
15
END DESCRIPTION:
#Sta/Elev= 11
     -20   10.44     -10   10.44    -5.2   10.44    -3.5   11.44     -.5   12.44
       0   12.44     4.5    9.64     9.5    9.64    12.5   11.54    13.3   12.34
    15.3   12.34
#Mann= 3 , 0 , 0
     -20    .035       0       0    .035       0    13.3    .035       0
#XS Ineff= 2 , 0
               0   12.44    13.3           12.34
Permanent Ineff=
       F       F
Bank Sta=0,13.3
XS Rating Curve= 0
Exp/Cntr=.3,.1

Type RM Length L Ch R = 1 ,742.00  ,1,1,1
BEGIN DESCRIPTION:
14.042
END DESCRIPTION:
#Sta/Elev= 16
     -20   10.18     -10   10.18    -5.2   10.18    -3.5   11.18     -.5   12.18
       0   12.18       3    9.78     4.7    8.78     9.7    8.78    12.7   10.68
    13.5   11.48    15.5   11.48    17.3   12.18    19.1   12.68    20.9   13.18
    22.7   13.68
#Mann= 3 , 0 , 0
     -20    .035       0       0    .035       0    13.5    .035       0
#XS Ineff= 2 , 0
               0   12.18    13.5           11.48
Permanent Ineff=
       F       F
Bank Sta=0,13.5
XS Rating Curve= 0
Exp/Cntr=.3,.1

Type RM Length L Ch R = 1 ,741.00  ,41,41,41
BEGIN DESCRIPTION:
14.041
END DESCRIPTION:
#Sta/Elev= 16
     -20   10.18     -10   10.18    -5.2   10.18    -3.5   11.18     -.5   12.18
       0   12.18       3    9.78     4.7    8.78     4.7    7.78     9.7    7.78
     9.7    8.78    12.7   10.68    13.5   11.48    15.5   11.48    17.3   12.18
    19.1   12.68
#Mann= 3 , 0 , 0
     -20    .035       0       0    .035       0    13.5    .035       0
#XS Ineff= 2 , 0
               0   12.18    13.5           11.48
Permanent Ineff=
       F       F
Bank Sta=0,13.5
XS Rating Curve= 0
Exp/Cntr=.3,.1

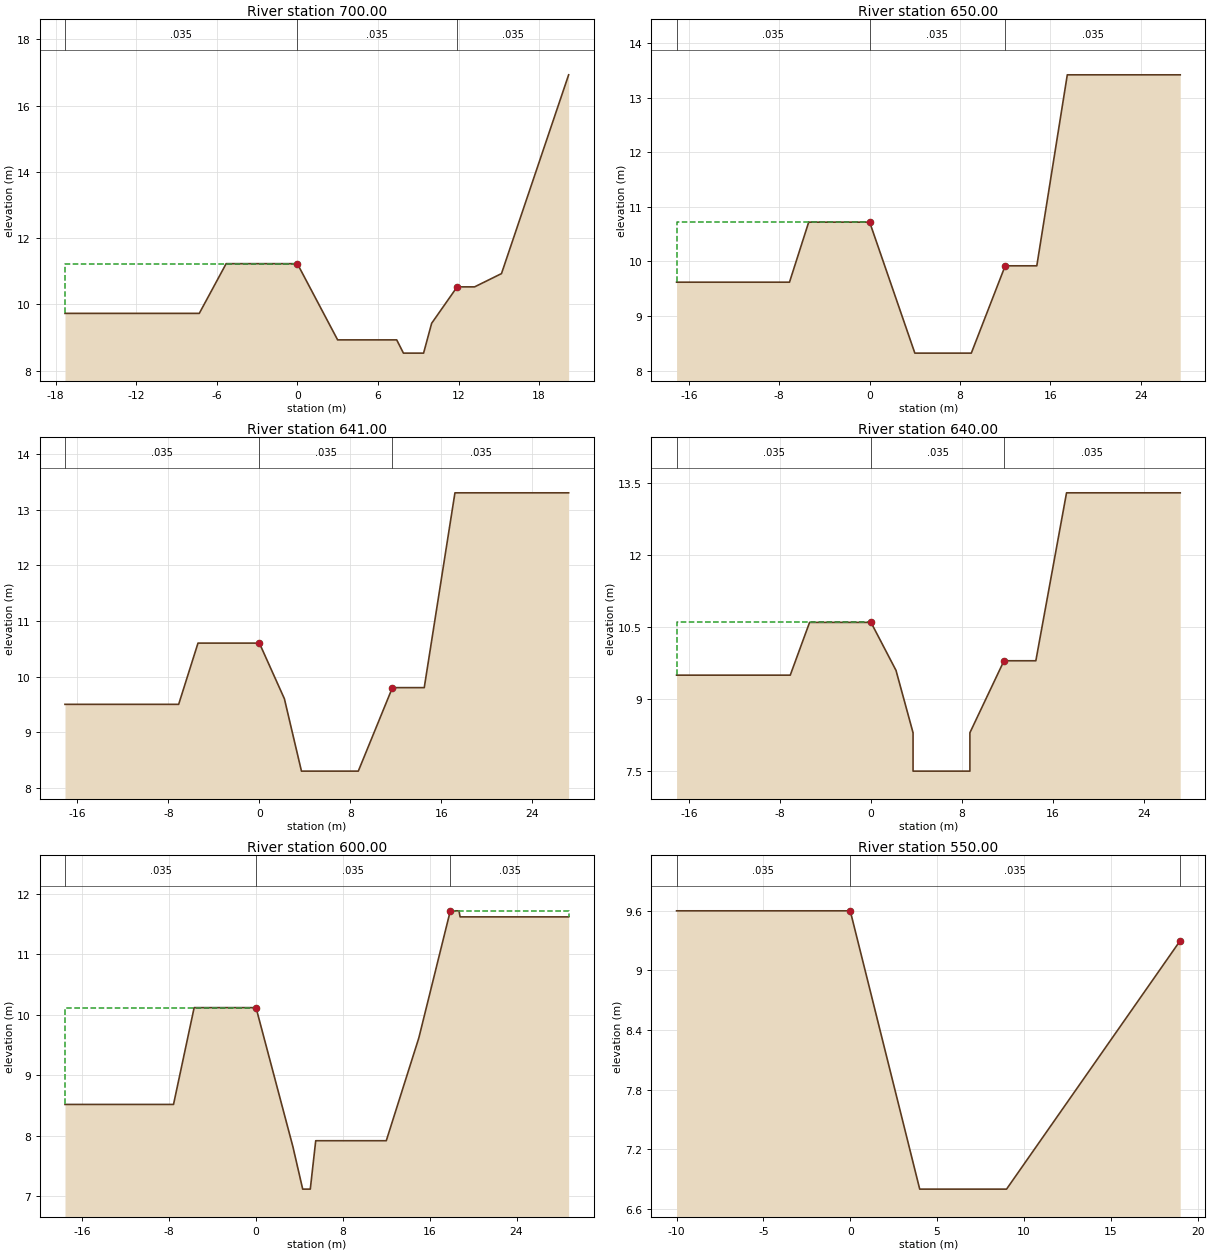
Type RM Length L Ch R = 1 ,700.00  ,50,50,50
BEGIN DESCRIPTION:
14
END DESCRIPTION:
#Sta/Elev= 15
   -17.3    9.73    -7.3    9.73    -5.3   11.23     -.5   11.23       0   11.23
       3    8.93     7.4    8.93     7.9    8.53     9.4    8.53      10    9.43
    11.9   10.53    13.2   10.53    15.2   10.93    17.7   13.93    20.2   16.93
#Mann= 3 , 0 , 0
   -17.3    .035       0       0    .035       0    11.9    .035       0
#XS Ineff= 2 , 0
               0   11.23    11.9           10.53
Permanent Ineff=
       F       F
Bank Sta=0,11.9
XS Rating Curve= 0
Exp/Cntr=.3,.1

Type RM Length L Ch R = 1 ,650.00  ,9,9,9
BEGIN DESCRIPTION:
13
END DESCRIPTION:
#Sta/Elev= 10
   -17.1    9.62    -7.1    9.62    -5.4   10.72       0   10.72       4    8.32
       9    8.32      12    9.92    14.8    9.92    17.5   13.42    27.5   13.42
#Mann= 3 , 0 , 0
   -17.1    .035       0       0    .035       0      12    .035       0
#XS Ineff= 2 , 0
               0   10.72      12            9.92
Permanent Ineff=
       F       F
Bank Sta=0,12
XS Rating Curve= 0
Exp/Cntr=.3,.1

Type RM Length L Ch R = 1 ,641.00  ,1,1,1
BEGIN DESCRIPTION:
12.041
END DESCRIPTION:
#Sta/Elev= 11
   -17.1     9.5    -7.1     9.5    -5.4    10.6       0    10.6     2.2     9.6
     3.7     8.3     8.7     8.3    11.7     9.8    14.5     9.8    17.2    13.3
    27.2    13.3
#Mann= 3 , 0 , 0
   -17.1    .035       0       0    .035       0    11.7    .035       0
#XS Ineff= 2 , 0
       0       0    10.6    11.7       0     9.8
Permanent Ineff=
       F       F
Bank Sta=0,11.7
XS Rating Curve= 0
Exp/Cntr=.3,.1

Type RM Length L Ch R = 1 ,640.00  ,40,40,40
BEGIN DESCRIPTION:
12.04
END DESCRIPTION:
#Sta/Elev= 13
   -17.1     9.5    -7.1     9.5    -5.4    10.6       0    10.6     2.2     9.6
     3.7     8.3     3.7     7.5     8.7     7.5     8.7     8.3    11.7     9.8
    14.5     9.8    17.2    13.3    27.2    13.3
#Mann= 3 , 0 , 0
   -17.1    .035       0       0    .035       0    11.7    .035       0
#XS Ineff= 2 , 0
               0    10.6    11.7             9.8
Permanent Ineff=
       F       F
Bank Sta=0,11.7
XS Rating Curve= 0
Exp/Cntr=.3,.1

Type RM Length L Ch R = 1 ,600.00  ,50,50,50
BEGIN DESCRIPTION:
12
END DESCRIPTION:
#Sta/Elev= 15
   -17.6    8.52    -7.6    8.52    -5.7   10.12     -.6   10.12       0   10.12
     3.4    7.82     4.3    7.12       5    7.12     5.5    7.92      12    7.92
      15    9.62    17.9   11.72    18.7   11.72    18.8   11.62    28.8   11.62
#Mann= 3 , 0 , 0
   -17.6    .035       0       0    .035       0    17.9    .035       0
#XS Ineff= 2 , 0
               0   10.12    17.9           11.72
Permanent Ineff=
       F       F
Bank Sta=0,17.9
XS Rating Curve= 0
Exp/Cntr=.3,.1

Type RM Length L Ch R = 1 ,550.00  ,22,22,22
BEGIN DESCRIPTION:
11
END DESCRIPTION:
#Sta/Elev= 5
     -10     9.6       0     9.6       4     6.8       9     6.8      19     9.3
#Mann= 3 , 0 , 0
     -10    .035       0       0    .035       0      19    .035       0
#XS Ineff= 2 , 0
               0     9.6      19             9.3
Permanent Ineff=
       F       F
Bank Sta=0,19
XS Rating Curve= 0
Exp/Cntr=.3,.1

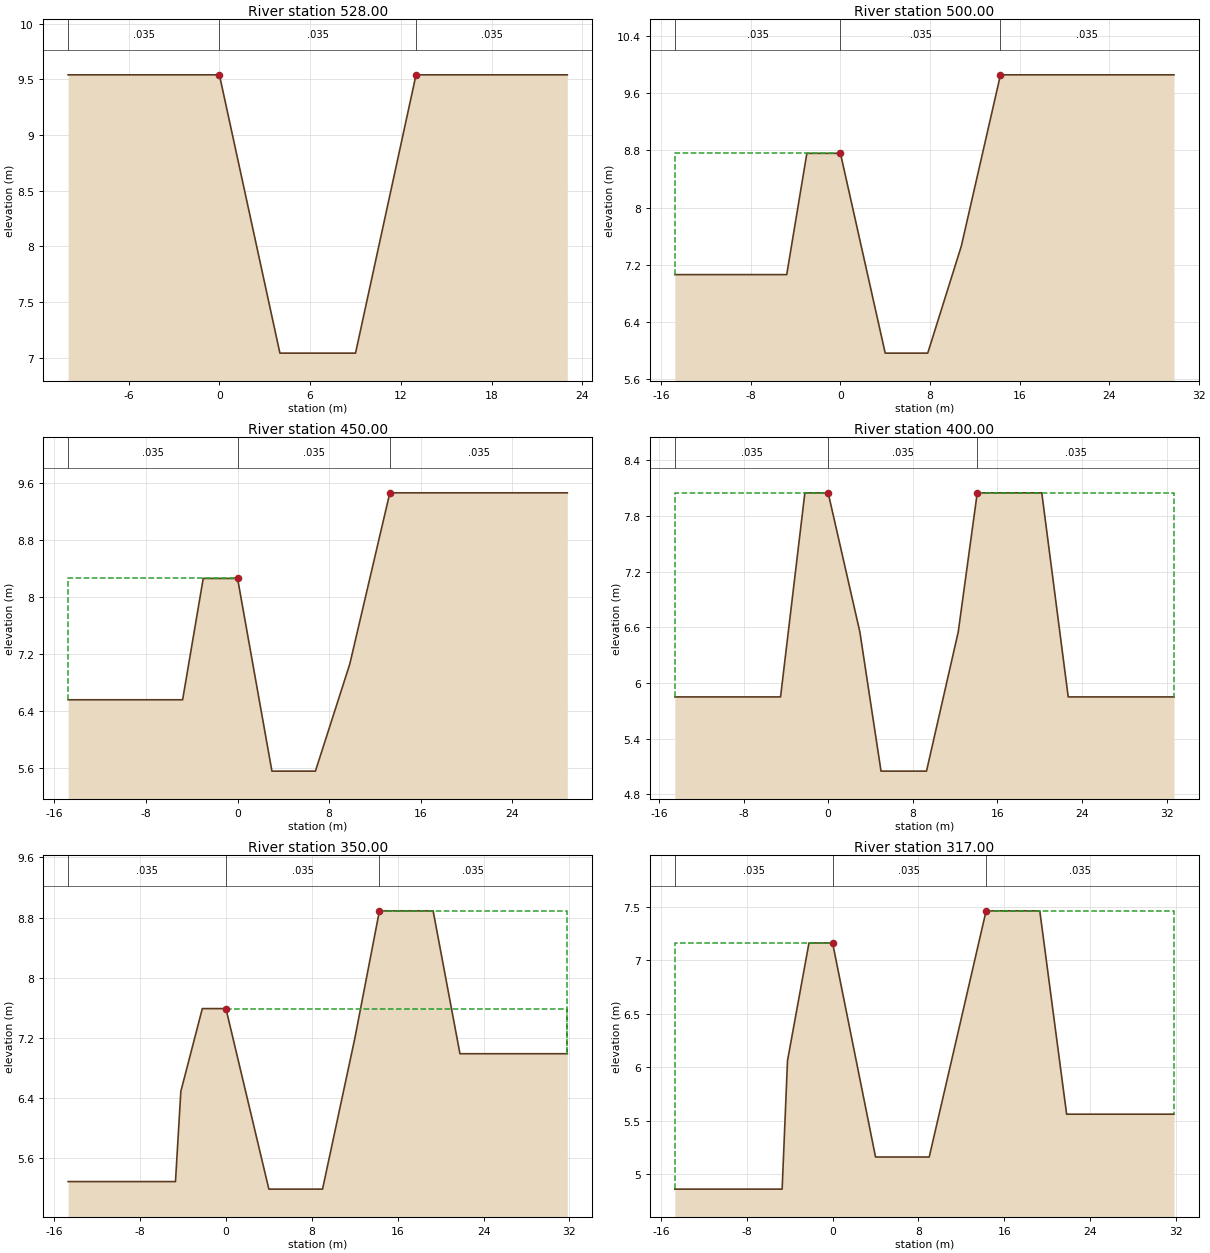
Type RM Length L Ch R = 1 ,528.00  ,28,28,28
BEGIN DESCRIPTION:
10.028
END DESCRIPTION:
#Sta/Elev= 6
     -10    9.54       0    9.54       4    7.04       9    7.04      13    9.54
      23    9.54
#Mann= 3 , 0 , 0
     -10    .035       0       0    .035       0      13    .035       0
#XS Ineff= 2 , 0
               0    9.54      13            9.54
Permanent Ineff=
       F       F
Bank Sta=0,13
XS Rating Curve= 0
Exp/Cntr=.3,.1

Type RM Length L Ch R = 1 ,500.00  ,50,50,50
BEGIN DESCRIPTION:
10
END DESCRIPTION:
#Sta/Elev= 11
   -14.8    7.06    -4.8    7.06      -3    8.76       0    8.76       4    5.96
     7.8    5.96    10.8    7.46    14.3    9.86    14.8    9.86    19.8    9.86
    29.8    9.86
#Mann= 3 , 0 , 0
   -14.8    .035       0       0    .035       0    14.3    .035       0
#XS Ineff= 2 , 0
               0    8.76    14.3            9.86
Permanent Ineff=
       F       F
Bank Sta=0,14.3
XS Rating Curve= 0
Exp/Cntr=.3,.1

Type RM Length L Ch R = 1 ,450.00  ,50,50,50
BEGIN DESCRIPTION:
9
END DESCRIPTION:
#Sta/Elev= 11
   -14.8    6.56    -4.8    6.56      -3    8.26       0    8.26       3    5.56
     6.8    5.56     9.8    7.06    13.3    9.46    13.8    9.46    18.8    9.46
    28.8    9.46
#Mann= 3 , 0 , 0
   -14.8    .035       0       0    .035       0    13.3    .035       0
#XS Ineff= 2 , 0
               0    8.26    13.3            9.46
Permanent Ineff=
       F       F
Bank Sta=0,13.3
XS Rating Curve= 0
Exp/Cntr=.3,.1

Type RM Length L Ch R = 1 ,400.00  ,50,50,50
BEGIN DESCRIPTION:
8
END DESCRIPTION:
#Sta/Elev= 15
   -14.5    5.85    -4.5    5.85    -2.2    8.05       0    8.05       3    6.55
       5    5.05     7.5    5.05     9.3    5.05    12.3    6.55    14.1    8.05
    14.6    8.05    19.6    8.05    20.2    8.05    22.7    5.85    32.7    5.85
#Mann= 3 , 0 , 0
   -14.5    .035       0       0    .035       0    14.1    .035       0
#XS Ineff= 2 , 0
               0    8.05    14.1            8.05
Permanent Ineff=
       F       F
Bank Sta=0,14.1
XS Rating Curve= 0
Exp/Cntr=.3,.1

Type RM Length L Ch R = 1 ,350.00  ,33,33,33
BEGIN DESCRIPTION:
7
END DESCRIPTION:
#Sta/Elev= 12
   -14.7    5.29    -4.7    5.29    -4.2    6.49    -2.2    7.59       0    7.59
       4    5.19       9    5.19      12    7.19    14.3    8.89    19.3    8.89
    21.8    6.99    31.8    6.99
#Mann= 3 , 0 , 0
   -14.7    .035       0       0    .035       0    14.3    .035       0
#XS Ineff= 2 , 0
       0       0    7.59    14.3       0    8.89
Permanent Ineff=
       F       F
Bank Sta=0,14.3
XS Rating Curve= 0
Exp/Cntr=.3,.1

Type RM Length L Ch R = 1 ,317.00  ,1,1,1
BEGIN DESCRIPTION:
6.017
END DESCRIPTION:
#Sta/Elev= 12
   -14.7    4.86    -4.7    4.86    -4.2    6.06    -2.2    7.16       0    7.16
       4    5.16       9    5.16      12    6.46    14.3    7.46    19.3    7.46
    21.8    5.56    31.8    5.56
#Mann= 3 , 0 , 0
   -14.7    .035       0       0    .035       0    14.3    .035       0
#XS Ineff= 2 , 0
               0    7.16    14.3            7.46
Permanent Ineff=
       F       F
Bank Sta=0,14.3
XS Rating Curve= 0
Exp/Cntr=.3,.1

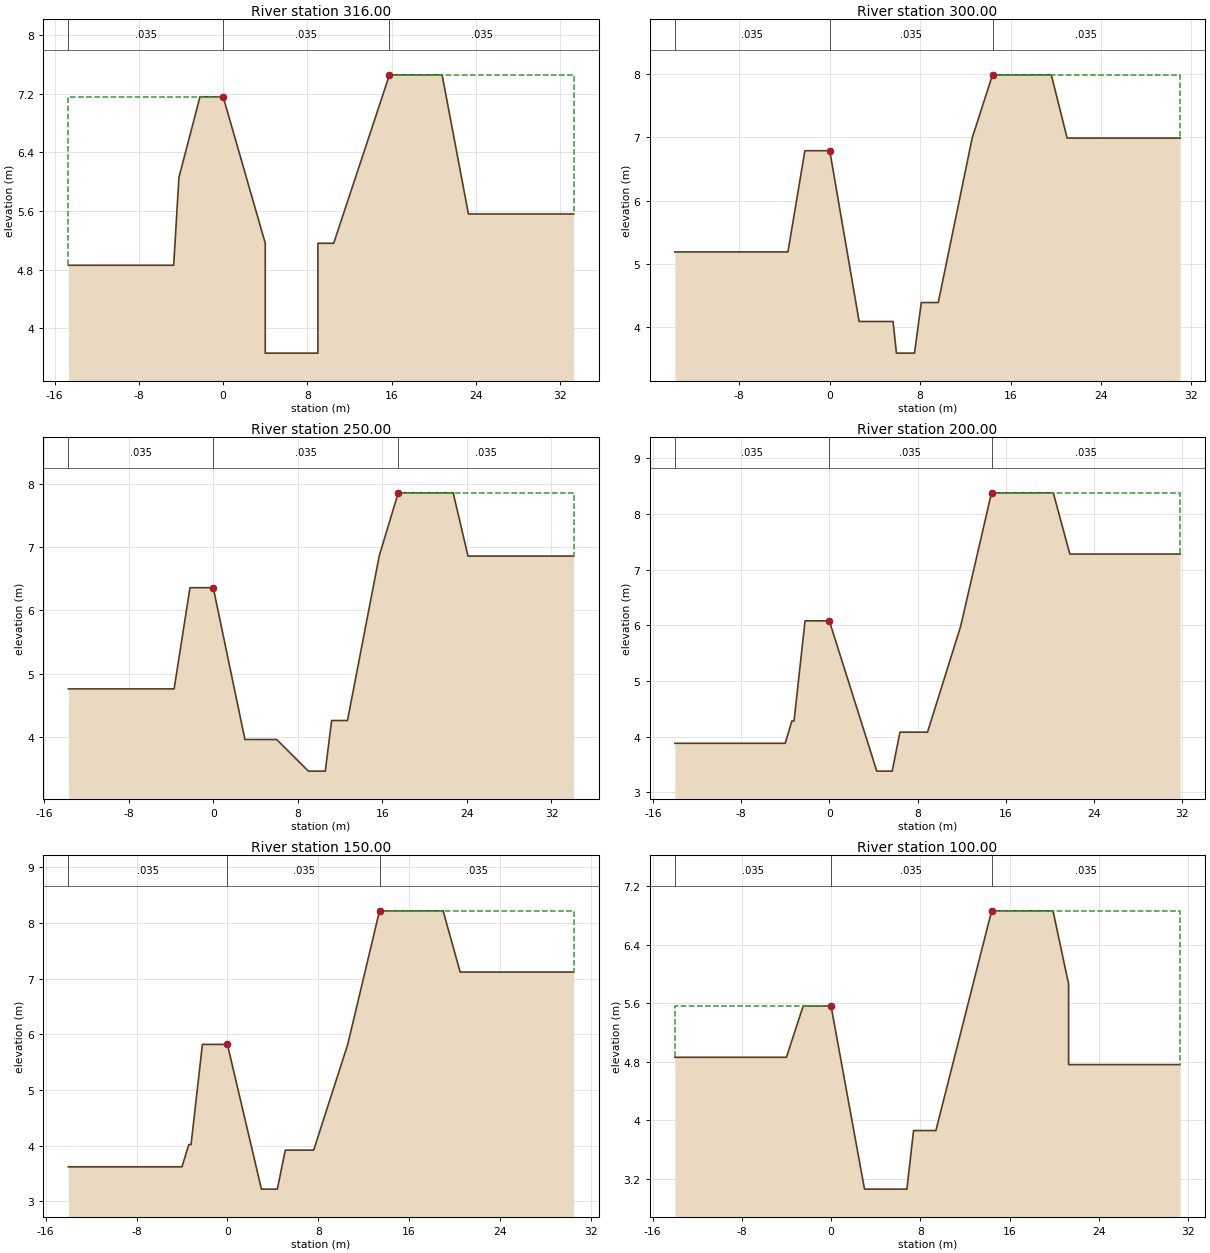
Type RM Length L Ch R = 1 ,316.00  ,16,16,16
BEGIN DESCRIPTION:
6.016
END DESCRIPTION:
#Sta/Elev= 15
   -14.7    4.86    -4.7    4.86    -4.2    6.06    -2.2    7.16       0    7.16
       4    5.16       4    3.66       9    3.66       9    5.16    10.5    5.16
    13.5    6.46    15.8    7.46    20.8    7.46    23.3    5.56    33.3    5.56
#Mann= 3 , 0 , 0
   -14.7    .035       0       0    .035       0    15.8    .035       0
#XS Ineff= 2 , 0
               0    7.16    15.8            7.46
Permanent Ineff=
       F       F
Bank Sta=0,15.8
XS Rating Curve= 0
Exp/Cntr=.3,.1

Type RM Length L Ch R = 1 ,300.00  ,50,50,50
BEGIN DESCRIPTION:
6
END DESCRIPTION:
#Sta/Elev= 16
   -13.7    5.19    -3.7    5.19    -2.2    6.79       0    6.79     2.6    4.09
     5.6    4.09     5.9    3.59     7.5    3.59     8.1    4.39     9.6    4.39
    12.6    6.99    14.4    7.99    14.6    7.99    19.6    7.99      21    6.99
      31    6.99
#Mann= 3 , 0 , 0
   -13.7    .035       0       0    .035       0    14.4    .035       0
#XS Ineff= 2 , 0
       0       0    6.79    14.4       0    7.99
Permanent Ineff=
       F       F
Bank Sta=0,14.4
XS Rating Curve= 0
Exp/Cntr=.3,.1

Type RM Length L Ch R = 1 ,250.00  ,50,50,50
BEGIN DESCRIPTION:
5
END DESCRIPTION:
#Sta/Elev= 16
   -13.7    4.76    -3.7    4.76    -2.2    6.36       0    6.36       3    3.96
       6    3.96       9    3.46    10.6    3.46    11.2    4.26    12.7    4.26
    15.7    6.86    17.5    7.86    17.7    7.86    22.7    7.86    24.1    6.86
    34.1    6.86
#Mann= 3 , 0 , 0
   -13.7    .035       0       0    .035       0    17.5    .035       0
#XS Ineff= 2 , 0
       0       0    6.36    17.5       0    7.86
Permanent Ineff=
       F       F
Bank Sta=0,17.5
XS Rating Curve= 0
Exp/Cntr=.3,.1

Type RM Length L Ch R = 1 ,200.00  ,50,50,50
BEGIN DESCRIPTION:
4
END DESCRIPTION:
#Sta/Elev= 17
     -14    3.88      -4    3.88    -3.4    4.28    -3.2    4.28    -2.2    6.08
       0    6.08     4.3    3.38     5.7    3.38     6.4    4.08     8.9    4.08
    11.9    5.98    14.7    8.38      15    8.38      20    8.38    20.3    8.38
    21.8    7.28    31.8    7.28
#Mann= 3 , 0 , 0
     -14    .035       0       0    .035       0    14.7    .035       0
#XS Ineff= 2 , 0
       0       0    6.08    14.7       0    8.38
Permanent Ineff=
       F       F
Bank Sta=0,14.7
XS Rating Curve= 0
Exp/Cntr=.3,.1

Type RM Length L Ch R = 1 ,150.00  ,50,50,50
BEGIN DESCRIPTION:
3
END DESCRIPTION:
#Sta/Elev= 17
     -14    3.62      -4    3.62    -3.4    4.02    -3.2    4.02    -2.2    5.82
       0    5.82       3    3.22     4.4    3.22     5.1    3.92     7.6    3.92
    10.6    5.82    13.4    8.22    13.7    8.22    18.7    8.22      19    8.22
    20.5    7.12    30.5    7.12
#Mann= 3 , 0 , 0
     -14    .035       0       0    .035       0    13.4    .035       0
#XS Ineff= 2 , 0
       0       0    5.82    13.4       0    8.22
Permanent Ineff=
       F       F
Bank Sta=0,13.4
XS Rating Curve= 0
Exp/Cntr=.3,.1

Type RM Length L Ch R = 1 ,100.00  ,50,50,50
BEGIN DESCRIPTION:
2
END DESCRIPTION:
#Sta/Elev= 15
     -14    4.86      -4    4.86    -2.5    5.56       0    5.56       3    3.06
     6.8    3.06     7.4    3.86     9.4    3.86    14.4    6.86    15.2    6.86
    19.2    6.86    19.9    6.86    21.3    5.86    21.3    4.76    31.3    4.76
#Mann= 3 , 0 , 0
     -14    .035       0       0    .035       0    14.4    .035       0
#XS Ineff= 2 , 0
               0    5.56    14.4            6.86
Permanent Ineff=
       F       F
Bank Sta=0,14.4
XS Rating Curve= 0
Exp/Cntr=.3,.1

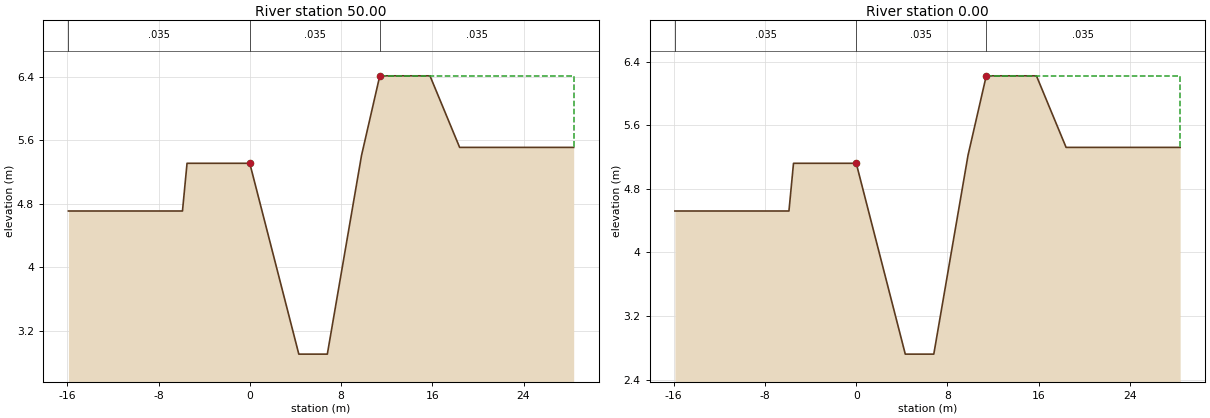
Type RM Length L Ch R = 1 ,50.00   ,50,50,50
BEGIN DESCRIPTION:
1
END DESCRIPTION:
#Sta/Elev= 11
   -15.9    4.71    -5.9    4.71    -5.5    5.31       0    5.31     4.3    2.91
     6.8    2.91     9.8    5.41    11.4    6.41    15.8    6.41    18.4    5.51
    28.4    5.51
#Mann= 3 , 0 , 0
   -15.9    .035       0       0    .035       0    11.4    .035       0
#XS Ineff= 2 , 0
       0       0    5.31    11.4       0    6.41
Permanent Ineff=
       F       F
Bank Sta=0,11.4
XS Rating Curve= 0
Exp/Cntr=.3,.1

Type RM Length L Ch R = 1 ,0.00    ,0,0,0
BEGIN DESCRIPTION:
0
END DESCRIPTION:
#Sta/Elev= 11
   -15.9    4.52    -5.9    4.52    -5.5    5.12       0    5.12     4.3    2.72
     6.8    2.72     9.8    5.22    11.4    6.22    15.8    6.22    18.4    5.32
    28.4    5.32
#Mann= 3 , 0 , 0
   -15.9    .035       0       0    .035       0    11.4    .035       0
#XS Ineff= 2 , 0
       0       0    5.12    11.4       0    6.22
Permanent Ineff=
       F       F
Bank Sta=0,11.4
XS Rating Curve= 0
Exp/Cntr=.3,.1

Chan Stop Cuts=-1