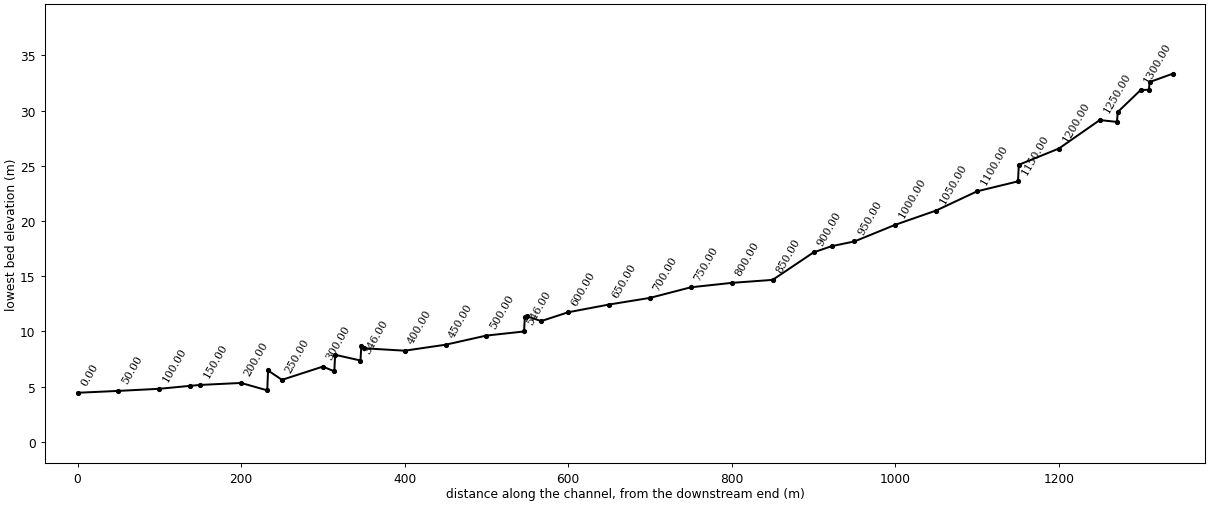
--- BONG.prj (project) ---

Proj Title=dongchon-chun
Current Plan=p01
Default Exp/Contr=.3,.1
SI Units
Geom File=g01
Flow File=f01
Plan File=p01
Y Axis Title=Elevation
X Axis Title(PF)=Main Channel Distance
X Axis Title(XS)=Station
BEGIN DESCRIPTION:
           BACK WATER COMPUTATION
      APPLICATION OF HEC-2 BY Samju Construction Engineering
      dongchon-chun 10,20,30,50,80 yr
END DESCRIPTION:
DSS Export Rating Curves= 0
DSS Export Rating Curve Sorted= 0
DSS Export Volume Flow Curves= 0
DXF OffsetX= 0
DXF OffsetY= 0
DXF ScaleX= 1
DXF ScaleY= 10

--- BONG.p01 (plan) ---

Plan Title=Imported Plan 01
Version=Version 3.0.1  Mar 2001
Short Identifier=Imported Pla
Geom File=g01
Flow File=f01
Subcritical Flow
K Sum by GR= 0
Std Step Tol= 0.003
Critical Tol= 0.003
Num of Std Step Trials= 20
Max Error Tol= 0.1
Flow Tol Ratio= 0.001
Split Flow NTrial= 30
Split Flow Tol= 0.02
Split Flow Ratio= 0.02
Log Output Level= 0
Friction Slope Method= 1
Unsteady Friction Slope Method= 2
Parabolic Critical Depth
Global Vel Dist= 0 , 0 , 0
Global Log Level= 0
CheckData=True
Encroach Param=-1 ,0,0, 0
Computation Interval=1HOUR
Output Interval=1HOUR
Run HTab= 0
Run UNet= 0
Run PostProcess= 0
UNET Theta= 1
UNET ZTol= 0.02
UNET ZSATol= 0.1
UNET MxIter= 20
UNET MaxInSteps= 20
UNET DtIC= 0
UNET DtMin= 0
UNET MaxCRTS= 20
UNET WFStab= 2
UNET SFStab= 1
UNET WFX= 1
UNET SFX= 1
UNET Convert EG Bridges=-1
UNET Use Existing IB Tables=-1
Instantaneous Interval=1HOUR
Write IC File= 0
Write Velocity= 0
Write Detailed= 0

--- BONG.f01 (steady flow) ---

Flow Title=Imported Flow 01
Version=Version 3.0.1  Mar 2001
Number of Profiles= 5
Profile Names=10YR,20YR,30YR,50YR,80YR
River Rch & RM=RIVER-1,Reach-1         ,1339.00
    7.43    8.19    8.63    9.18    9.69
River Rch & RM=RIVER-1,Reach-1         ,850.00
   12.59   13.88   14.62   15.57   16.44
Boundary for River Rch & Prof#=RIVER-1,Reach-1         , 1
Up Type= 0
Dn Type= 3
Dn Slope=.063
Boundary for River Rch & Prof#=RIVER-1,Reach-1         , 2
Up Type= 0
Dn Type= 3
Dn Slope=.063
Boundary for River Rch & Prof#=RIVER-1,Reach-1         , 3
Up Type= 0
Dn Type= 3
Dn Slope=.063
Boundary for River Rch & Prof#=RIVER-1,Reach-1         , 4
Up Type= 0
Dn Type= 3
Dn Slope=.063
Boundary for River Rch & Prof#=RIVER-1,Reach-1         , 5
Up Type= 0
Dn Type= 3
Dn Slope=.063
DSS Import GetInterval= 0
DSS Import GetPeak= 0
DSS Import FillOption= 0

--- BONG.g01 (geometry) ---

Geom Title=Imported Geom 01
Version=Version 3.0.1  Mar 2001

River Reach=RIVER-1         ,Reach-1
Reach XY= 2
              .5             .95              .5             .05

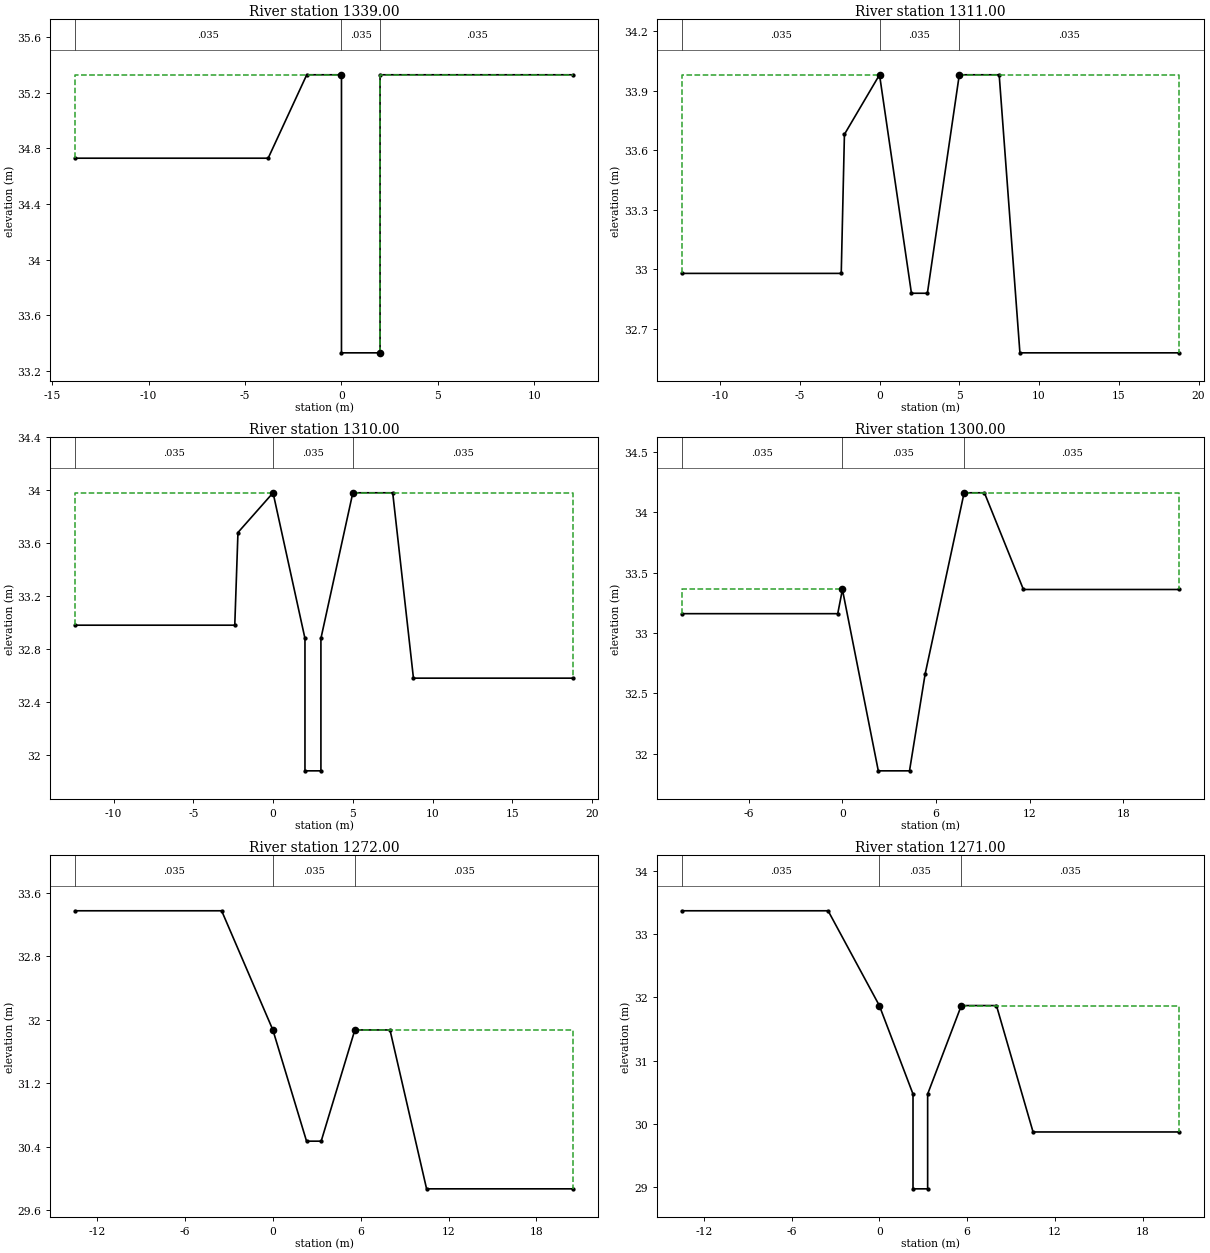
Type RM Length L Ch R = 1 ,1339.00 ,28,28,28
#Sta/Elev= 8
   -13.8   34.73    -3.8   34.73    -1.8   35.33       0   35.33       0   33.33
       2   33.33       2   35.33      12   35.33
#Mann= 3 , 0 , 0
   -13.8    .035       0       0    .035       0       2    .035       0
#XS Ineff= 2 , 0
               0   35.33       2           35.33
Permanent Ineff=
       F       F
Bank Sta=0,2
XS Rating Curve= 0
Exp/Cntr=.3,.1

Type RM Length L Ch R = 1 ,1311.00 ,1,1,1
#Sta/Elev= 10
   -12.4   32.98    -2.4   32.98    -2.2   33.68       0   33.98       2   32.88
       3   32.88       5   33.98     7.5   33.98     8.8   32.58    18.8   32.58
#Mann= 3 , 0 , 0
   -12.4    .035       0       0    .035       0       5    .035       0
#XS Ineff= 2 , 0
               0   33.98       5           33.98
Permanent Ineff=
       F       F
Bank Sta=0,5
XS Rating Curve= 0
Exp/Cntr=.3,.1

Type RM Length L Ch R = 1 ,1310.00 ,10,10,10
#Sta/Elev= 12
   -12.4   32.98    -2.4   32.98    -2.2   33.68       0   33.98       2   32.88
       2   31.88       3   31.88       3   32.88       5   33.98     7.5   33.98
     8.8   32.58    18.8   32.58
#Mann= 3 , 0 , 0
   -12.4    .035       0       0    .035       0       5    .035       0
#XS Ineff= 2 , 0
               0   33.98       5           33.98
Permanent Ineff=
       F       F
Bank Sta=0,5
XS Rating Curve= 0
Exp/Cntr=.3,.1

Type RM Length L Ch R = 1 ,1300.00 ,28,28,28
#Sta/Elev= 10
   -10.3   33.16     -.3   33.16       0   33.36     2.3   31.86     4.3   31.86
     5.3   32.66     7.8   34.16     9.1   34.16    11.6   33.36    21.6   33.36
#Mann= 3 , 0 , 0
   -10.3    .035       0       0    .035       0     7.8    .035       0
#XS Ineff= 2 , 0
               0   33.36     7.8           34.16
Permanent Ineff=
       F       F
Bank Sta=0,7.8
XS Rating Curve= 0
Exp/Cntr=.3,.1

Type RM Length L Ch R = 1 ,1272.00 ,1,1,1
#Sta/Elev= 9
   -13.5   33.37    -3.5   33.37       0   31.87     2.3   30.47     3.3   30.47
     5.6   31.87       8   31.87    10.5   29.87    20.5   29.87
#Mann= 3 , 0 , 0
   -13.5    .035       0       0    .035       0     5.6    .035       0
#XS Ineff= 2 , 0
               0   31.87     5.6           31.87
Permanent Ineff=
       F       F
Bank Sta=0,5.6
XS Rating Curve= 0
Exp/Cntr=.3,.1

Type RM Length L Ch R = 1 ,1271.00 ,21,21,21
#Sta/Elev= 11
   -13.5   33.37    -3.5   33.37       0   31.87     2.3   30.47     2.3   28.97
     3.3   28.97     3.3   30.47     5.6   31.87       8   31.87    10.5   29.87
    20.5   29.87
#Mann= 3 , 0 , 0
   -13.5    .035       0       0    .035       0     5.6    .035       0
#XS Ineff= 2 , 0
               0   31.87     5.6           31.87
Permanent Ineff=
       F       F
Bank Sta=0,5.6
XS Rating Curve= 0
Exp/Cntr=.3,.1

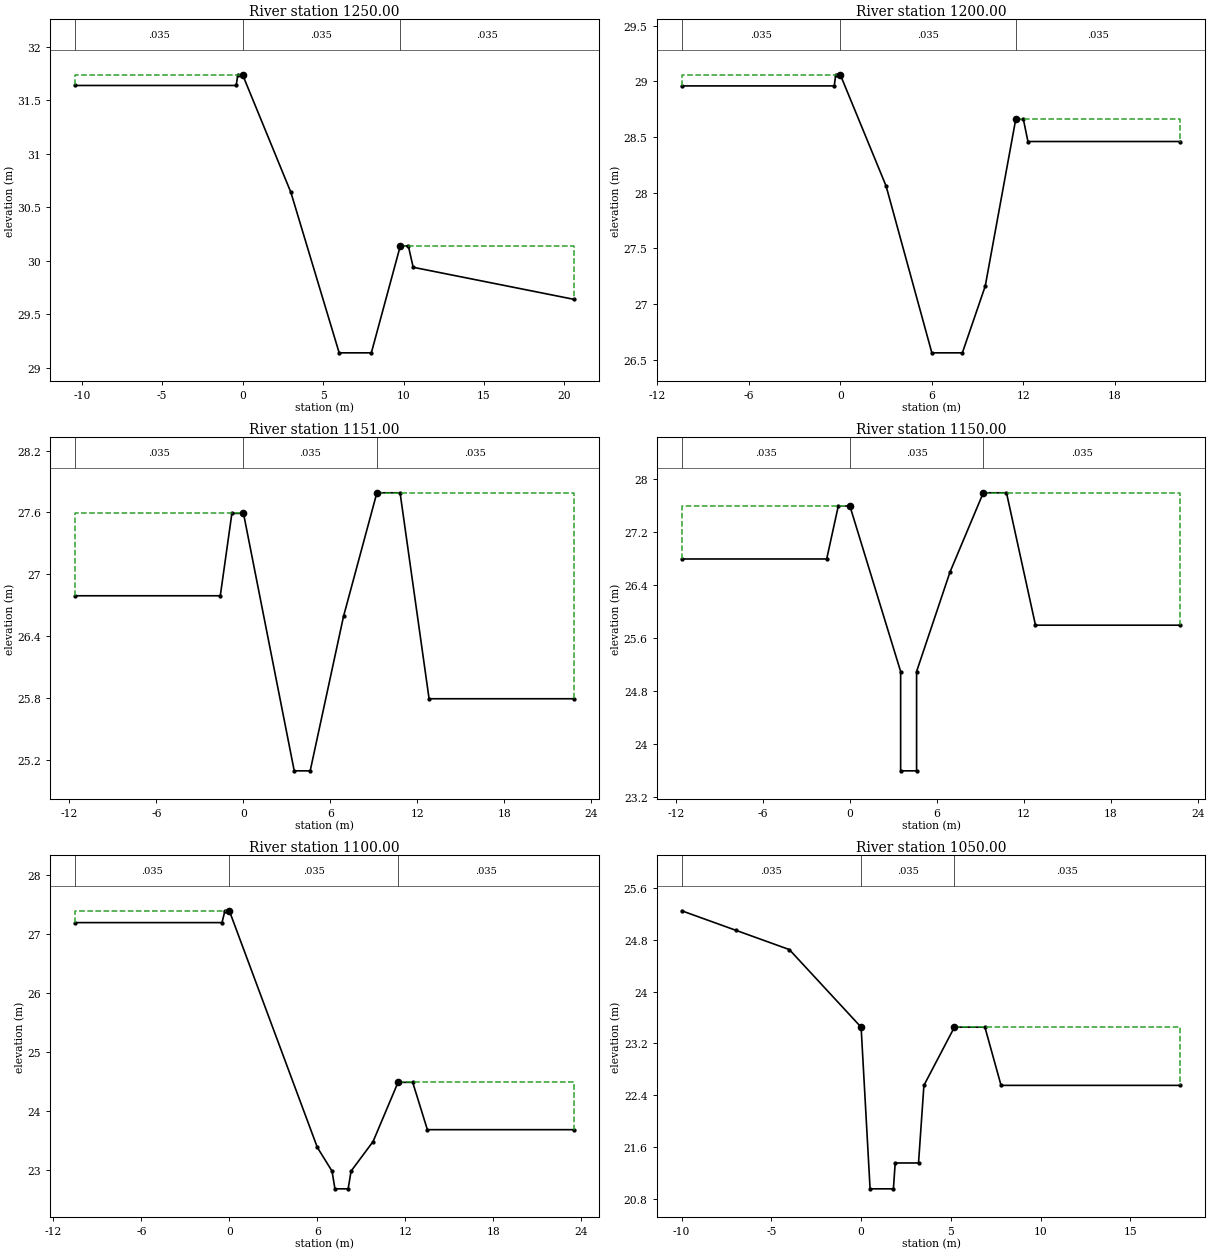
Type RM Length L Ch R = 1 ,1250.00 ,50,50,50
#Sta/Elev= 11
   -10.4   31.64     -.4   31.64     -.3   31.74       0   31.74       3   30.64
       6   29.14       8   29.14     9.8   30.14    10.3   30.14    10.6   29.94
    20.6   29.64
#Mann= 3 , 0 , 0
   -10.4    .035       0       0    .035       0     9.8    .035       0
#XS Ineff= 2 , 0
               0   31.74     9.8           30.14
Permanent Ineff=
       F       F
Bank Sta=0,9.8
XS Rating Curve= 0
Exp/Cntr=.3,.1

Type RM Length L Ch R = 1 ,1200.00 ,49,49,49
#Sta/Elev= 12
   -10.4   28.96     -.4   28.96     -.3   29.06       0   29.06       3   28.06
       6   26.56       8   26.56     9.5   27.16    11.5   28.66      12   28.66
    12.3   28.46    22.3   28.46
#Mann= 3 , 0 , 0
   -10.4    .035       0       0    .035       0    11.5    .035       0
#XS Ineff= 2 , 0
               0   29.06    11.5           28.66
Permanent Ineff=
       F       F
Bank Sta=0,11.5
XS Rating Curve= 0
Exp/Cntr=.3,.1

Type RM Length L Ch R = 1 ,1151.00 ,1,1,1
#Sta/Elev= 11
   -11.6   26.79    -1.6   26.79     -.8   27.59       0   27.59     3.5   25.09
     4.6   25.09     6.9   26.59     9.2   27.79    10.8   27.79    12.8   25.79
    22.8   25.79
#Mann= 3 , 0 , 0
   -11.6    .035       0       0    .035       0     9.2    .035       0
#XS Ineff= 2 , 0
               0   27.59     9.2           27.79
Permanent Ineff=
       F       F
Bank Sta=0,9.2
XS Rating Curve= 0
Exp/Cntr=.3,.1

Type RM Length L Ch R = 1 ,1150.00 ,50,50,50
#Sta/Elev= 13
   -11.6   26.79    -1.6   26.79     -.8   27.59       0   27.59     3.5   25.09
     3.5   23.59     4.6   23.59     4.6   25.09     6.9   26.59     9.2   27.79
    10.8   27.79    12.8   25.79    22.8   25.79
#Mann= 3 , 0 , 0
   -11.6    .035       0       0    .035       0     9.2    .035       0
#XS Ineff= 2 , 0
               0   27.59     9.2           27.79
Permanent Ineff=
       F       F
Bank Sta=0,9.2
XS Rating Curve= 0
Exp/Cntr=.3,.1

Type RM Length L Ch R = 1 ,1100.00 ,50,50,50
#Sta/Elev= 14
   -10.5   27.19     -.5   27.19     -.3   27.39       0   27.39       6   23.39
       7   22.99     7.2   22.69     8.1   22.69     8.3   22.99     9.8   23.49
    11.5   24.49    12.5   24.49    13.5   23.69    23.5   23.69
#Mann= 3 , 0 , 0
   -10.5    .035       0       0    .035       0    11.5    .035       0
#XS Ineff= 2 , 0
               0   27.39    11.5           24.49
Permanent Ineff=
       F       F
Bank Sta=0,11.5
XS Rating Curve= 0
Exp/Cntr=.3,.1

Type RM Length L Ch R = 1 ,1050.00 ,50,50,50
#Sta/Elev= 13
     -10   25.25      -7   24.95      -4   24.65       0   23.45      .5   20.95
     1.8   20.95     1.9   21.35     3.2   21.35     3.5   22.55     5.2   23.45
     6.9   23.45     7.8   22.55    17.8   22.55
#Mann= 3 , 0 , 0
     -10    .035       0       0    .035       0     5.2    .035       0
#XS Ineff= 2 , 0
               0   23.45     5.2           23.45
Permanent Ineff=
       F       F
Bank Sta=0,5.2
XS Rating Curve= 0
Exp/Cntr=.3,.1

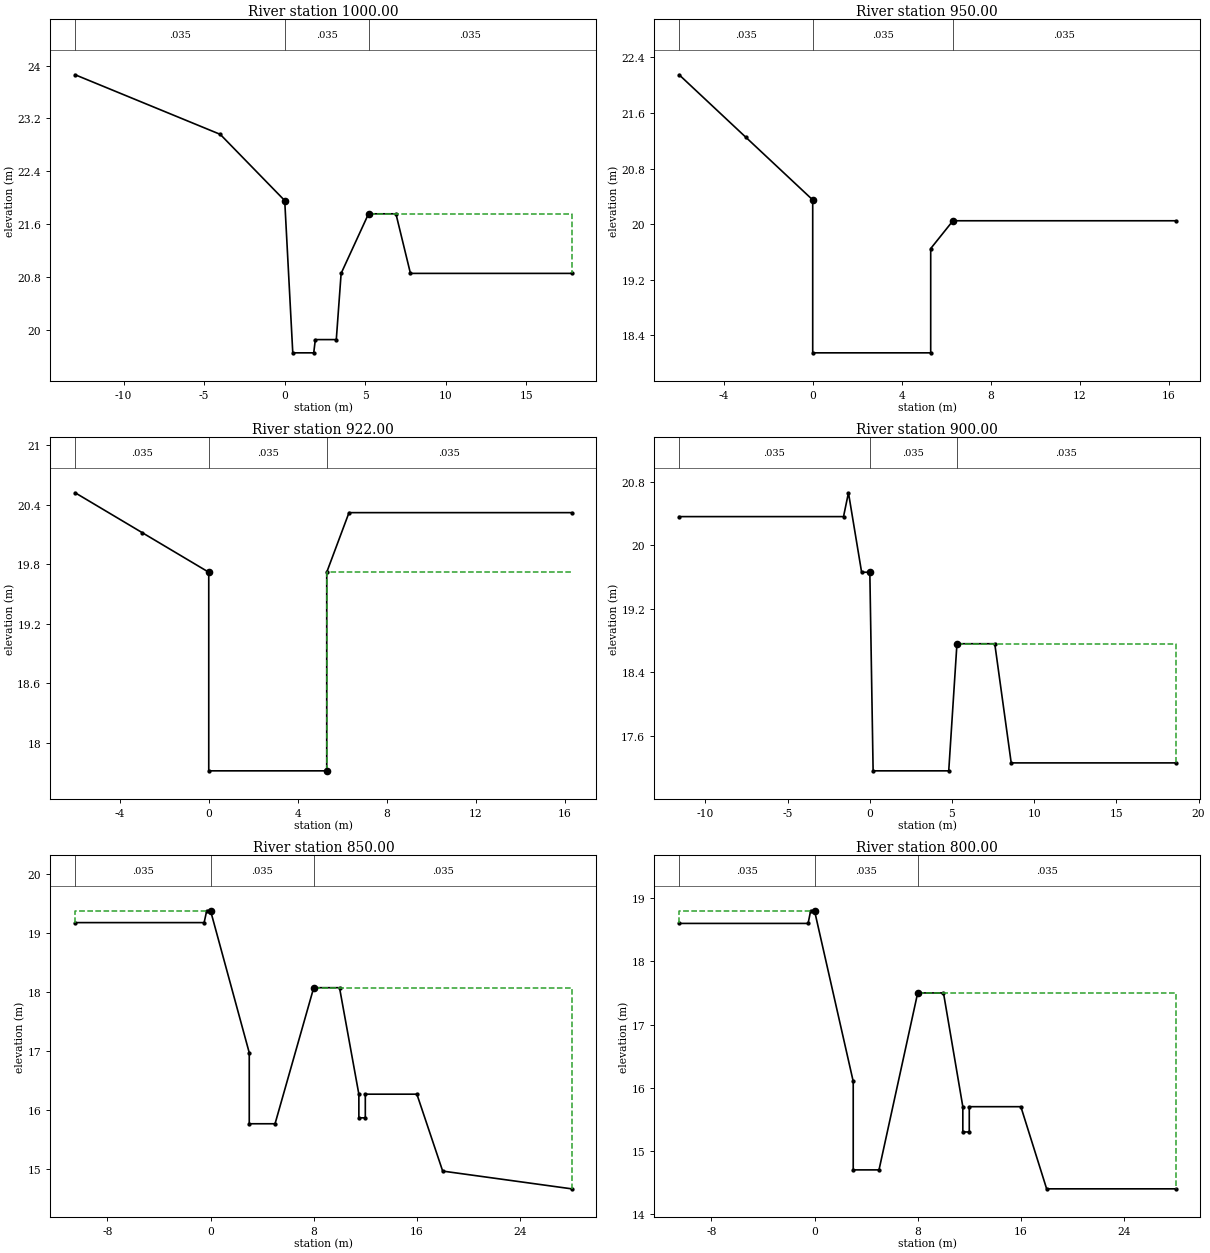
Type RM Length L Ch R = 1 ,1000.00 ,50,50,50
#Sta/Elev= 12
     -13   23.86      -4   22.96       0   21.96      .5   19.66     1.8   19.66
     1.9   19.86     3.2   19.86     3.5   20.86     5.2   21.76     6.9   21.76
     7.8   20.86    17.8   20.86
#Mann= 3 , 0 , 0
     -13    .035       0       0    .035       0     5.2    .035       0
#XS Ineff= 2 , 0
               0   21.96     5.2           21.76
Permanent Ineff=
       F       F
Bank Sta=0,5.2
XS Rating Curve= 0
Exp/Cntr=.3,.1

Type RM Length L Ch R = 1 ,950.00  ,28,28,28
#Sta/Elev= 8
      -6   22.15      -3   21.25       0   20.35       0   18.15     5.3   18.15
     5.3   19.65     6.3   20.05    16.3   20.05
#Mann= 3 , 0 , 0
      -6    .035       0       0    .035       0     6.3    .035       0
#XS Ineff= 2 , 0
               0   20.35     6.3           20.05
Permanent Ineff=
       F       F
Bank Sta=0,6.3
XS Rating Curve= 0
Exp/Cntr=.3,.1

Type RM Length L Ch R = 1 ,922.00  ,22,22,22
#Sta/Elev= 8
      -6   20.52      -3   20.12       0   19.72       0   17.72     5.3   17.72
     5.3   19.72     6.3   20.32    16.3   20.32
#Mann= 3 , 0 , 0
      -6    .035       0       0    .035       0     5.3    .035       0
#XS Ineff= 2 , 0
               0   19.72     5.3           19.72
Permanent Ineff=
       F       F
Bank Sta=0,5.3
XS Rating Curve= 0
Exp/Cntr=.3,.1

Type RM Length L Ch R = 1 ,900.00  ,50,50,50
#Sta/Elev= 11
   -11.6   20.36    -1.6   20.36    -1.3   20.66     -.5   19.66       0   19.66
      .2   17.16     4.8   17.16     5.3   18.76     7.6   18.76     8.6   17.26
    18.6   17.26
#Mann= 3 , 0 , 0
   -11.6    .035       0       0    .035       0     5.3    .035       0
#XS Ineff= 2 , 0
               0   19.66     5.3           18.76
Permanent Ineff=
       F       F
Bank Sta=0,5.3
XS Rating Curve= 0
Exp/Cntr=.3,.1

Type RM Length L Ch R = 1 ,850.00  ,50,50,50
#Sta/Elev= 16
   -10.5   19.17     -.5   19.17     -.3   19.37       0   19.37       3   16.97
       3   15.77       5   15.77       8   18.07      10   18.07    11.5   16.27
    11.5   15.87      12   15.87      12   16.27      16   16.27      18   14.97
      28   14.67
#Mann= 3 , 0 , 0
   -10.5    .035       0       0    .035       0       8    .035       0
#XS Ineff= 2 , 0
               0   19.37       8           18.07
Permanent Ineff=
       F       F
Bank Sta=0,8
XS Rating Curve= 0
Exp/Cntr=.3,.1

Type RM Length L Ch R = 1 ,800.00  ,50,50,50
#Sta/Elev= 16
   -10.5    18.6     -.5    18.6     -.3    18.8       0    18.8       3    16.1
       3    14.7       5    14.7       8    17.5      10    17.5    11.5    15.7
    11.5    15.3      12    15.3      12    15.7      16    15.7      18    14.4
      28    14.4
#Mann= 3 , 0 , 0
   -10.5    .035       0       0    .035       0       8    .035       0
#XS Ineff= 2 , 0
               0    18.8       8            17.5
Permanent Ineff=
       F       F
Bank Sta=0,8
XS Rating Curve= 0
Exp/Cntr=.3,.1

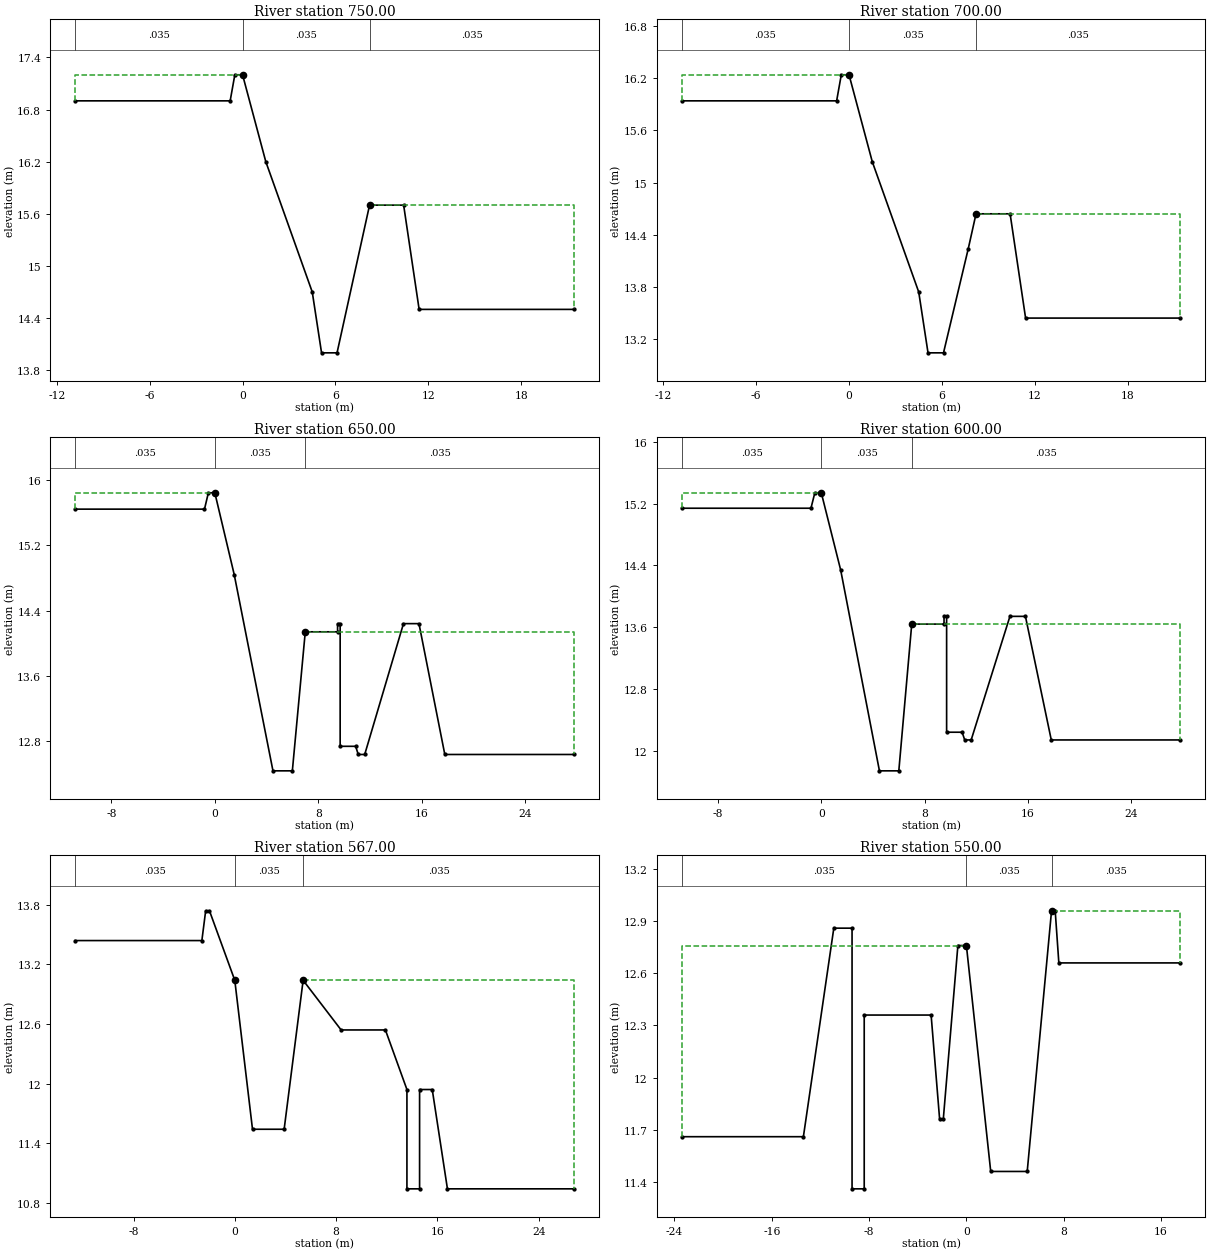
Type RM Length L Ch R = 1 ,750.00  ,50,50,50
#Sta/Elev= 12
   -10.8    16.9     -.8    16.9     -.5    17.2       0    17.2     1.5    16.2
     4.5    14.7     5.1      14     6.1      14     8.2    15.7    10.4    15.7
    11.4    14.5    21.4    14.5
#Mann= 3 , 0 , 0
   -10.8    .035       0       0    .035       0     8.2    .035       0
#XS Ineff= 2 , 0
               0    17.2     8.2            15.7
Permanent Ineff=
       F       F
Bank Sta=0,8.2
XS Rating Curve= 0
Exp/Cntr=.3,.1

Type RM Length L Ch R = 1 ,700.00  ,50,50,50
#Sta/Elev= 13
   -10.8   15.94     -.8   15.94     -.5   16.24       0   16.24     1.5   15.24
     4.5   13.74     5.1   13.04     6.1   13.04     7.7   14.24     8.2   14.64
    10.4   14.64    11.4   13.44    21.4   13.44
#Mann= 3 , 0 , 0
   -10.8    .035       0       0    .035       0     8.2    .035       0
#XS Ineff= 2 , 0
               0   16.24     8.2           14.64
Permanent Ineff=
       F       F
Bank Sta=0,8.2
XS Rating Curve= 0
Exp/Cntr=.3,.1

Type RM Length L Ch R = 1 ,650.00  ,50,50,50
#Sta/Elev= 19
   -10.8   15.64     -.8   15.64     -.5   15.84       0   15.84     1.5   14.84
     4.5   12.44       6   12.44       7   14.14     9.5   14.14     9.5   14.24
     9.7   14.24     9.7   12.74    10.9   12.74    11.1   12.64    11.6   12.64
    14.6   14.24    15.8   14.24    17.8   12.64    27.8   12.64
#Mann= 3 , 0 , 0
   -10.8    .035       0       0    .035       0       7    .035       0
#XS Ineff= 2 , 0
               0   15.84       7           14.14
Permanent Ineff=
       F       F
Bank Sta=0,7
XS Rating Curve= 0
Exp/Cntr=.3,.1

Type RM Length L Ch R = 1 ,600.00  ,33,33,33
#Sta/Elev= 19
   -10.8   15.14     -.8   15.14     -.5   15.34       0   15.34     1.5   14.34
     4.5   11.74       6   11.74       7   13.64     9.5   13.64     9.5   13.74
     9.7   13.74     9.7   12.24    10.9   12.24    11.1   12.14    11.6   12.14
    14.6   13.74    15.8   13.74    17.8   12.14    27.8   12.14
#Mann= 3 , 0 , 0
   -10.8    .035       0       0    .035       0       7    .035       0
#XS Ineff= 2 , 0
               0   15.34       7           13.64
Permanent Ineff=
       F       F
Bank Sta=0,7
XS Rating Curve= 0
Exp/Cntr=.3,.1

Type RM Length L Ch R = 1 ,567.00  ,17,17,17
#Sta/Elev= 17
   -12.6   13.44    -2.6   13.44    -2.3   13.74      -2   13.74       0   13.04
     1.4   11.54     3.9   11.54     5.4   13.04     8.4   12.54    11.9   12.54
    13.6   11.94    13.6   10.94    14.6   10.94    14.6   11.94    15.6   11.94
    16.8   10.94    26.8   10.94
#Mann= 3 , 0 , 0
   -12.6    .035       0       0    .035       0     5.4    .035       0
#XS Ineff= 2 , 0
               0   13.04     5.4           13.04
Permanent Ineff=
       F       F
Bank Sta=0,5.4
XS Rating Curve= 0
Exp/Cntr=.3,.1

Type RM Length L Ch R = 1 ,550.00  ,3,3,3
#Sta/Elev= 18
   -23.4   11.66   -13.4   11.66   -10.9   12.86    -9.4   12.86    -9.4   11.36
    -8.4   11.36    -8.4   12.36    -2.9   12.36    -2.2   11.76    -1.9   11.76
     -.7   12.76       0   12.76       2   11.46       5   11.46       7   12.96
     7.3   12.96     7.6   12.66    17.6   12.66
#Mann= 3 , 0 , 0
   -23.4    .035       0       0    .035       0       7    .035       0
#XS Ineff= 2 , 0
               0   12.76       7           12.96
Permanent Ineff=
       F       F
Bank Sta=0,7
XS Rating Curve= 0
Exp/Cntr=.3,.1

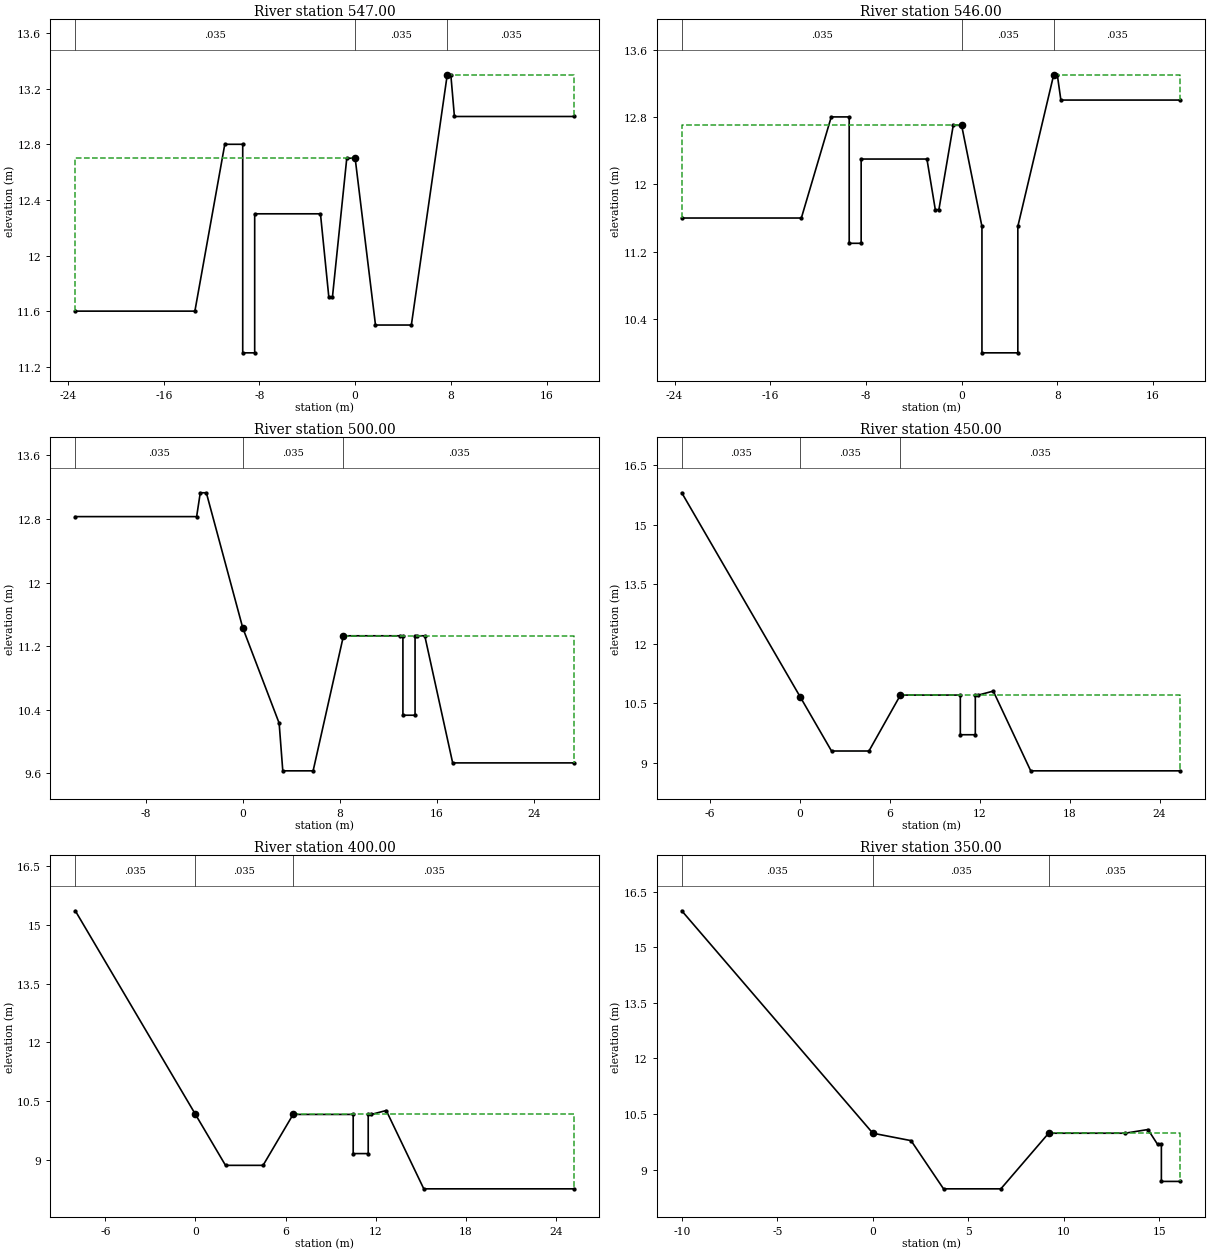
Type RM Length L Ch R = 1 ,547.00  ,1,1,1
#Sta/Elev= 18
   -23.4    11.6   -13.4    11.6   -10.9    12.8    -9.4    12.8    -9.4    11.3
    -8.4    11.3    -8.4    12.3    -2.9    12.3    -2.2    11.7    -1.9    11.7
     -.7    12.7       0    12.7     1.7    11.5     4.7    11.5     7.7    13.3
       8    13.3     8.3      13    18.3      13
#Mann= 3 , 0 , 0
   -23.4    .035       0       0    .035       0     7.7    .035       0
#XS Ineff= 2 , 0
               0    12.7     7.7            13.3
Permanent Ineff=
       F       F
Bank Sta=0,7.7
XS Rating Curve= 0
Exp/Cntr=.3,.1

Type RM Length L Ch R = 1 ,546.00  ,46,46,46
#Sta/Elev= 20
   -23.4    11.6   -13.4    11.6   -10.9    12.8    -9.4    12.8    -9.4    11.3
    -8.4    11.3    -8.4    12.3    -2.9    12.3    -2.2    11.7    -1.9    11.7
     -.7    12.7       0    12.7     1.7    11.5     1.7      10     4.7      10
     4.7    11.5     7.7    13.3       8    13.3     8.3      13    18.3      13
#Mann= 3 , 0 , 0
   -23.4    .035       0       0    .035       0     7.7    .035       0
#XS Ineff= 2 , 0
               0    12.7     7.7            13.3
Permanent Ineff=
       F       F
Bank Sta=0,7.7
XS Rating Curve= 0
Exp/Cntr=.3,.1

Type RM Length L Ch R = 1 ,500.00  ,50,50,50
#Sta/Elev= 18
   -13.8   12.83    -3.8   12.83    -3.5   13.13      -3   13.13       0   11.43
       3   10.23     3.3    9.63     5.8    9.63     8.3   11.33      13   11.33
    13.2   11.33    13.2   10.33    14.2   10.33    14.2   11.33    14.4   11.33
      15   11.33    17.3    9.73    27.3    9.73
#Mann= 3 , 0 , 0
   -13.8    .035       0       0    .035       0     8.3    .035       0
#XS Ineff= 2 , 0
               0   11.43     8.3           11.33
Permanent Ineff=
       F       F
Bank Sta=0,8.3
XS Rating Curve= 0
Exp/Cntr=.3,.1

Type RM Length L Ch R = 1 ,450.00  ,50,50,50
#Sta/Elev= 13
    -7.9   15.81       0   10.67     2.1     9.3     4.6     9.3     6.7   10.71
    10.7   10.71    10.7    9.71    11.7    9.71    11.7   10.71    11.9   10.71
    12.9   10.81    15.4     8.8    25.4     8.8
#Mann= 3 , 0 , 0
    -7.9    .035       0       0    .035       0     6.7    .035       0
#XS Ineff= 2 , 0
               0   10.67     6.7           10.71
Permanent Ineff=
       F       F
Bank Sta=0,6.7
XS Rating Curve= 0
Exp/Cntr=.3,.1

Type RM Length L Ch R = 1 ,400.00  ,50,50,50
#Sta/Elev= 13
      -8   15.36       0   10.16       2    8.86     4.5    8.86     6.5   10.16
    10.5   10.16    10.5    9.16    11.5    9.16    11.5   10.16    11.7   10.16
    12.7   10.26    15.2    8.26    25.2    8.26
#Mann= 3 , 0 , 0
      -8    .035       0       0    .035       0     6.5    .035       0
#XS Ineff= 2 , 0
               0   10.16     6.5           10.16
Permanent Ineff=
       F       F
Bank Sta=0,6.5
XS Rating Curve= 0
Exp/Cntr=.3,.1

Type RM Length L Ch R = 1 ,350.00  ,3,3,3
#Sta/Elev= 12
     -10   15.98       0    9.98       2    9.78     3.7    8.48     6.7    8.48
     9.2    9.98    13.2    9.98    14.4   10.08    14.9    9.68    15.1    9.68
    15.1    8.68    16.1    8.68
#Mann= 3 , 0 , 0
     -10    .035       0       0    .035       0     9.2    .035       0
#XS Ineff= 2 , 0
               0    9.98     9.2            9.98
Permanent Ineff=
       F       F
Bank Sta=0,9.2
XS Rating Curve= 0
Exp/Cntr=.3,.1

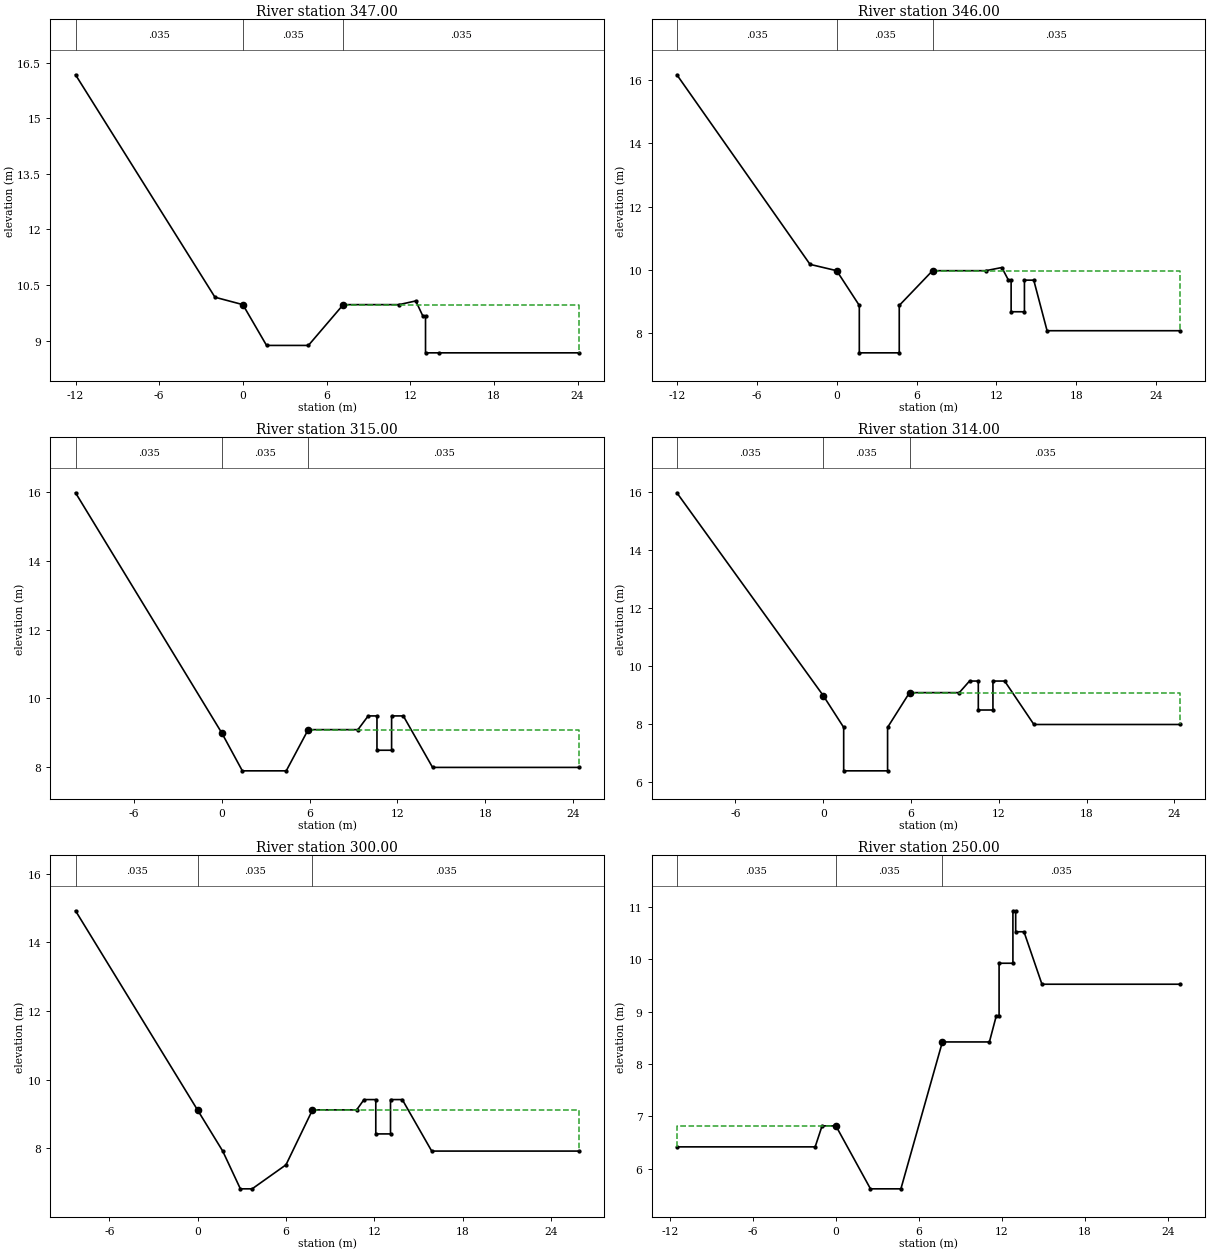
Type RM Length L Ch R = 1 ,347.00  ,1,1,1
#Sta/Elev= 13
     -12   16.17      -2   10.17       0    9.97     1.7    8.87     4.7    8.87
     7.2    9.97    11.2    9.97    12.4   10.07    12.9    9.67    13.1    9.67
    13.1    8.67    14.1    8.67    24.1    8.67
#Mann= 3 , 0 , 0
     -12    .035       0       0    .035       0     7.2    .035       0
#XS Ineff= 2 , 0
               0    9.97     7.2            9.97
Permanent Ineff=
       F       F
Bank Sta=0,7.2
XS Rating Curve= 0
Exp/Cntr=.3,.1

Type RM Length L Ch R = 1 ,346.00  ,31,31,31
#Sta/Elev= 18
     -12   16.17      -2   10.17       0    9.97     1.7    8.87     1.7    7.37
     4.7    7.37     4.7    8.87     7.2    9.97    11.2    9.97    12.4   10.07
    12.9    9.67    13.1    9.67    13.1    8.67    14.1    8.67    14.1    9.67
    14.8    9.67    15.8    8.07    25.8    8.07
#Mann= 3 , 0 , 0
     -12    .035       0       0    .035       0     7.2    .035       0
#XS Ineff= 2 , 0
               0    9.97     7.2            9.97
Permanent Ineff=
       F       F
Bank Sta=0,7.2
XS Rating Curve= 0
Exp/Cntr=.3,.1

Type RM Length L Ch R = 1 ,315.00  ,1,1,1
#Sta/Elev= 14
     -10   15.99       0    8.99     1.4    7.89     4.4    7.89     5.9    9.09
     9.3    9.09      10    9.49    10.6    9.49    10.6    8.49    11.6    8.49
    11.6    9.49    12.4    9.49    14.4    7.99    24.4    7.99
#Mann= 3 , 0 , 0
     -10    .035       0       0    .035       0     5.9    .035       0
#XS Ineff= 2 , 0
               0    8.99     5.9            9.09
Permanent Ineff=
       F       F
Bank Sta=0,5.9
XS Rating Curve= 0
Exp/Cntr=.3,.1

Type RM Length L Ch R = 1 ,314.00  ,14,14,14
#Sta/Elev= 16
     -10   15.99       0    8.99     1.4    7.89     1.4    6.39     4.4    6.39
     4.4    7.89     5.9    9.09     9.3    9.09      10    9.49    10.6    9.49
    10.6    8.49    11.6    8.49    11.6    9.49    12.4    9.49    14.4    7.99
    24.4    7.99
#Mann= 3 , 0 , 0
     -10    .035       0       0    .035       0     5.9    .035       0
#XS Ineff= 2 , 0
               0    8.99     5.9            9.09
Permanent Ineff=
       F       F
Bank Sta=0,5.9
XS Rating Curve= 0
Exp/Cntr=.3,.1

Type RM Length L Ch R = 1 ,300.00  ,50,50,50
#Sta/Elev= 16
    -8.3   14.92       0    9.11     1.7    7.92     2.9    6.82     3.7    6.82
       6    7.52     7.8    9.12    10.8    9.12    11.3    9.42    12.1    9.42
    12.1    8.42    13.1    8.42    13.1    9.42    13.9    9.42    15.9    7.92
    25.9    7.92
#Mann= 3 , 0 , 0
    -8.3    .035       0       0    .035       0     7.8    .035       0
#XS Ineff= 2 , 0
               0    9.11     7.8            9.12
Permanent Ineff=
       F       F
Bank Sta=0,7.8
XS Rating Curve= 0
Exp/Cntr=.3,.1

Type RM Length L Ch R = 1 ,250.00  ,17,17,17
#Sta/Elev= 18
   -11.5    6.42    -1.5    6.42      -1    6.82       0    6.82     2.5    5.62
     4.7    5.62     7.7    8.42    11.1    8.42    11.6    8.92    11.8    8.92
    11.8    9.92    12.8    9.92    12.8   10.92      13   10.92      13   10.52
    13.6   10.52    14.9    9.52    24.9    9.52
#Mann= 3 , 0 , 0
   -11.5    .035       0       0    .035       0     7.7    .035       0
#XS Ineff= 2 , 0
               0    6.82     7.7            8.42
Permanent Ineff=
       F       F
Bank Sta=0,7.7
XS Rating Curve= 0
Exp/Cntr=.3,.1

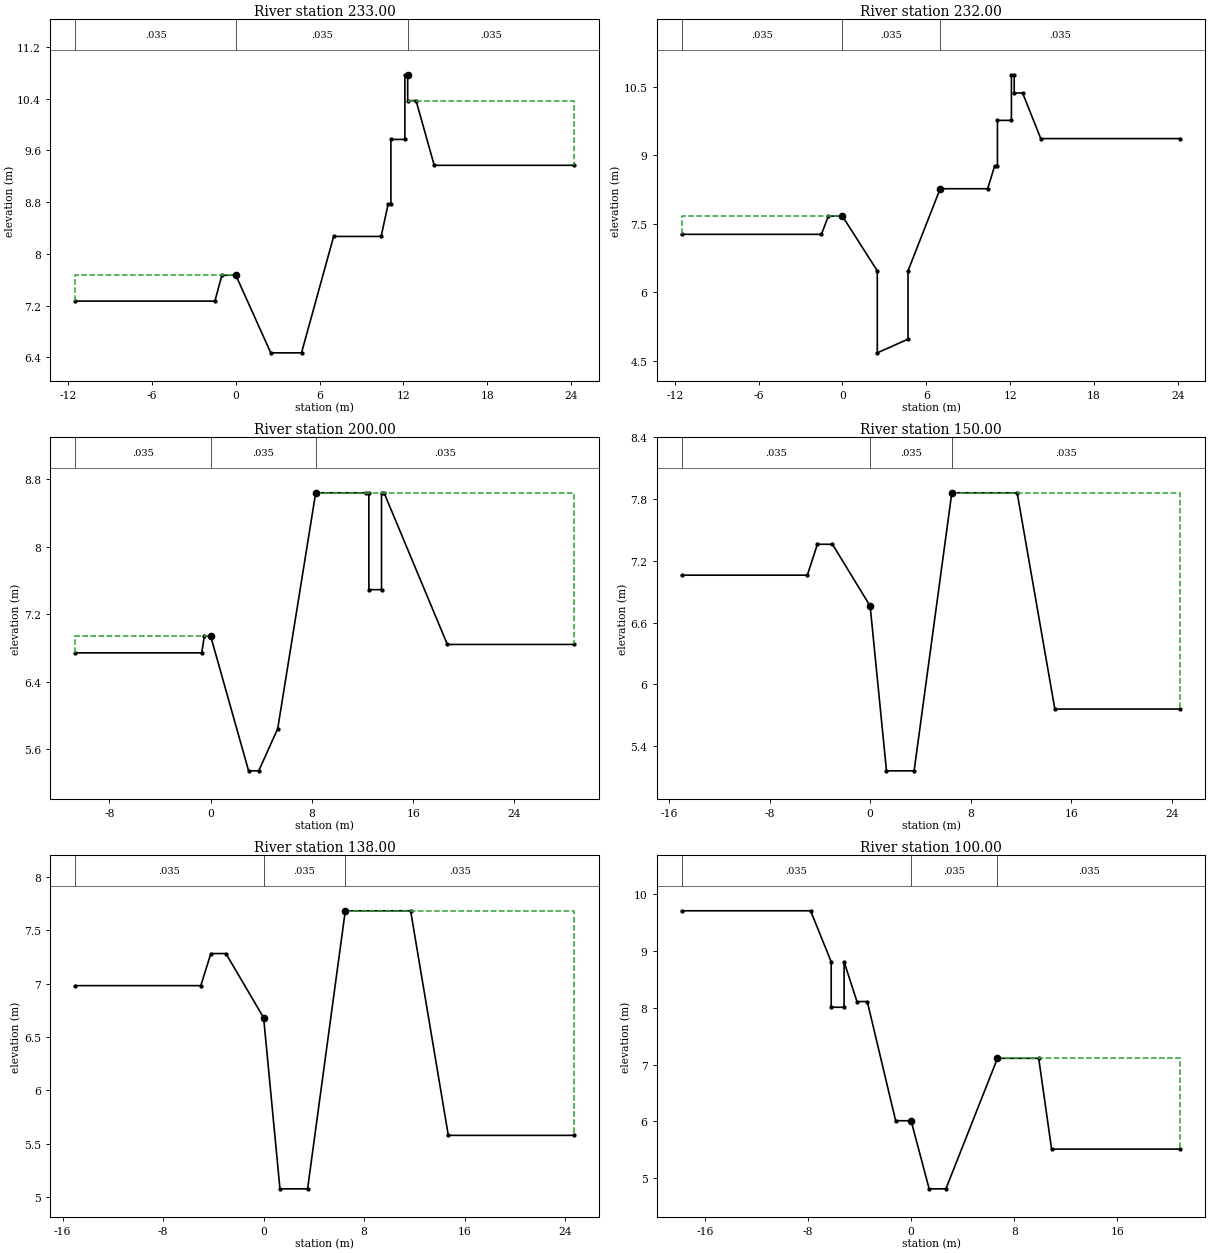
Type RM Length L Ch R = 1 ,233.00  ,1,1,1
#Sta/Elev= 18
   -11.5    7.27    -1.5    7.27      -1    7.67       0    7.67     2.5    6.47
     4.7    6.47       7    8.27    10.4    8.27    10.9    8.77    11.1    8.77
    11.1    9.77    12.1    9.77    12.1   10.77    12.3   10.77    12.3   10.37
    12.9   10.37    14.2    9.37    24.2    9.37
#Mann= 3 , 0 , 0
   -11.5    .035       0       0    .035       0    12.3    .035       0
#XS Ineff= 2 , 0
               0    7.67    12.3           10.37
Permanent Ineff=
       F       F
Bank Sta=0,12.3
XS Rating Curve= 0
Exp/Cntr=.3,.1

Type RM Length L Ch R = 1 ,232.00  ,32,32,32
#Sta/Elev= 20
   -11.5    7.27    -1.5    7.27      -1    7.67       0    7.67     2.5    6.47
     2.5    4.67     4.7    4.97     4.7    6.47       7    8.27    10.4    8.27
    10.9    8.77    11.1    8.77    11.1    9.77    12.1    9.77    12.1   10.77
    12.3   10.77    12.3   10.37    12.9   10.37    14.2    9.37    24.2    9.37
#Mann= 3 , 0 , 0
   -11.5    .035       0       0    .035       0       7    .035       0
#XS Ineff= 2 , 0
               0    7.67       7            8.27
Permanent Ineff=
       F       F
Bank Sta=0,7
XS Rating Curve= 0
Exp/Cntr=.3,.1

Type RM Length L Ch R = 1 ,200.00  ,50,50,50
#Sta/Elev= 16
   -10.7    6.74     -.7    6.74     -.5    6.94       0    6.94       3    5.34
     3.8    5.34     5.3    5.84     8.3    8.64    12.3    8.64    12.5    8.64
    12.5    7.49    13.5    7.49    13.5    8.64    13.7    8.64    18.7    6.84
    28.7    6.84
#Mann= 3 , 0 , 0
   -10.7    .035       0       0    .035       0     8.3    .035       0
#XS Ineff= 2 , 0
               0    6.94     8.3            8.64
Permanent Ineff=
       F       F
Bank Sta=0,8.3
XS Rating Curve= 0
Exp/Cntr=.3,.1

Type RM Length L Ch R = 1 ,150.00  ,12,12,12
#Sta/Elev= 11
     -15    7.06      -5    7.06    -4.2    7.36      -3    7.36       0    6.76
     1.3    5.16     3.5    5.16     6.5    7.86    11.7    7.86    14.7    5.76
    24.7    5.76
#Mann= 3 , 0 , 0
     -15    .035       0       0    .035       0     6.5    .035       0
#XS Ineff= 2 , 0
               0    6.76     6.5            7.86
Permanent Ineff=
       F       F
Bank Sta=0,6.5
XS Rating Curve= 0
Exp/Cntr=.3,.1

Type RM Length L Ch R = 1 ,138.00  ,38,38,38
#Sta/Elev= 11
     -15    6.98      -5    6.98    -4.2    7.28      -3    7.28       0    6.68
     1.3    5.08     3.5    5.08     6.5    7.68    11.7    7.68    14.7    5.58
    24.7    5.58
#Mann= 3 , 0 , 0
     -15    .035       0       0    .035       0     6.5    .035       0
#XS Ineff= 2 , 0
               0    6.68     6.5            7.68
Permanent Ineff=
       F       F
Bank Sta=0,6.5
XS Rating Curve= 0
Exp/Cntr=.3,.1

Type RM Length L Ch R = 1 ,100.00  ,50,50,50
#Sta/Elev= 16
   -17.8    9.71    -7.8    9.71    -6.2    8.81    -6.2    8.01    -5.2    8.01
    -5.2    8.81    -4.2    8.11    -3.4    8.11    -1.2    6.01       0    6.01
     1.4    4.81     2.7    4.81     6.7    7.11     9.9    7.11    10.9    5.51
    20.9    5.51
#Mann= 3 , 0 , 0
   -17.8    .035       0       0    .035       0     6.7    .035       0
#XS Ineff= 2 , 0
               0    6.01     6.7            7.11
Permanent Ineff=
       F       F
Bank Sta=0,6.7
XS Rating Curve= 0
Exp/Cntr=.3,.1

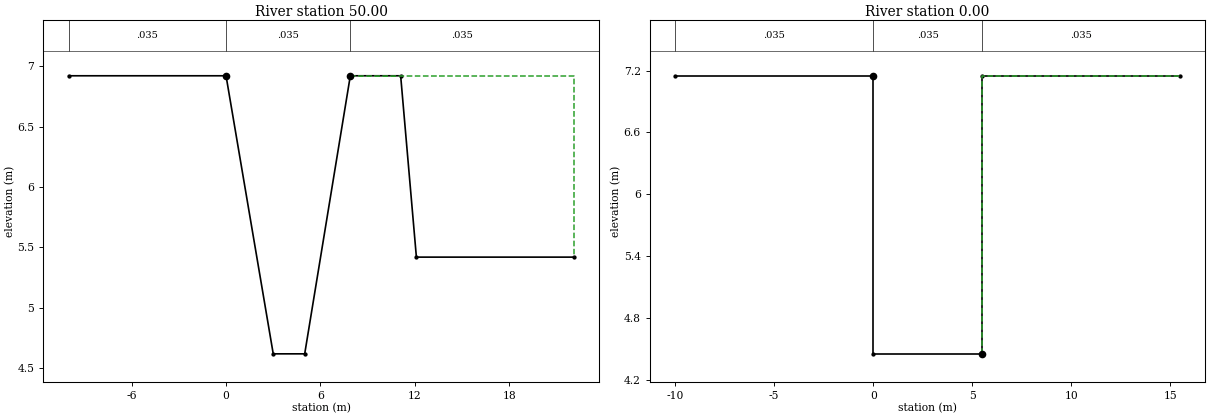
Type RM Length L Ch R = 1 ,50.00   ,50,50,50
#Sta/Elev= 8
     -10    6.92       0    6.92       3    4.62       5    4.62     7.9    6.92
    11.1    6.92    12.1    5.42    22.1    5.42
#Mann= 3 , 0 , 0
     -10    .035       0       0    .035       0     7.9    .035       0
#XS Ineff= 2 , 0
               0    6.92     7.9            6.92
Permanent Ineff=
       F       F
Bank Sta=0,7.9
XS Rating Curve= 0
Exp/Cntr=.3,.1

Type RM Length L Ch R = 1 ,0.00    ,0,0,0
#Sta/Elev= 6
     -10    7.15       0    7.15       0    4.45     5.5    4.45     5.5    7.15
    15.5    7.15
#Mann= 3 , 0 , 0
     -10    .035       0       0    .035       0     5.5    .035       0
#XS Ineff= 2 , 0
               0    7.15     5.5            7.15
Permanent Ineff=
       F       F
Bank Sta=0,5.5
XS Rating Curve= 0
Exp/Cntr=.3,.1

Chan Stop Cuts=-1