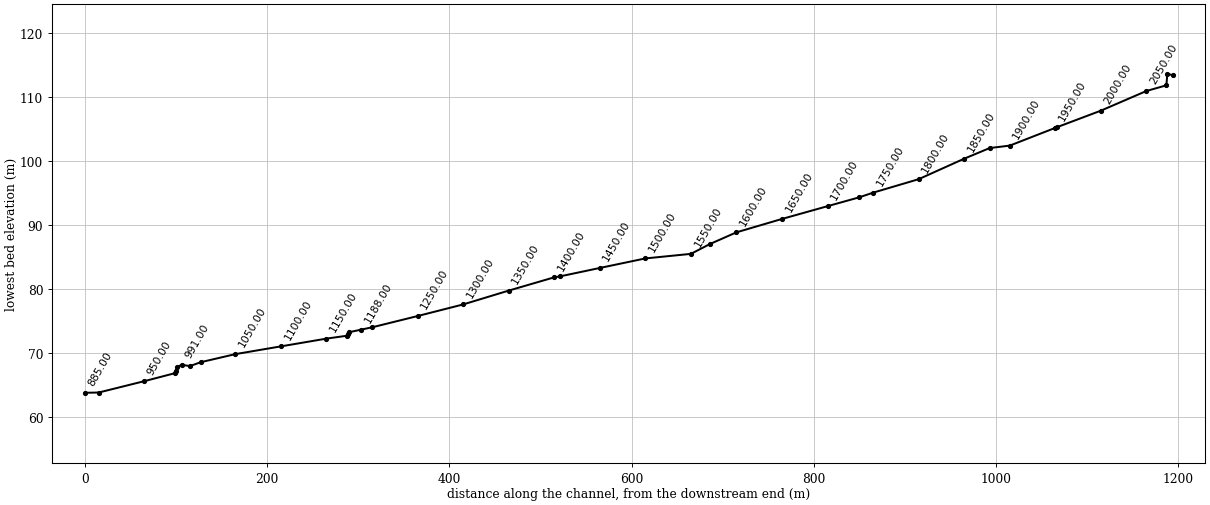
--- CHANG.prj (project) ---

Proj Title=changdong-chu
Current Plan=p01
Default Exp/Contr=.3,.1
SI Units
Geom File=g01
Flow File=f01
Plan File=p01
Y Axis Title=Elevation
X Axis Title(PF)=Main Channel Distance
X Axis Title(XS)=Station
BEGIN DESCRIPTION:
           BACK WATER COMPUTATION
      APPLICATION OF HEC-2 BY Samju Construction Engineering
      changdong-chun: 10,50,30,50,80 yr
END DESCRIPTION:
DSS Export Rating Curves= 0
DSS Export Rating Curve Sorted= 0
DSS Export Volume Flow Curves= 0
DXF OffsetX= 0
DXF OffsetY= 0
DXF ScaleX= 1
DXF ScaleY= 10

--- CHANG.p01 (plan) ---

Plan Title=Imported Plan 01
Version=Version 3.0.1  Mar 2001
Short Identifier=Imported Pla
Geom File=g01
Flow File=f01
Subcritical Flow
K Sum by GR= 0
Std Step Tol= 0.01
Critical Tol= 0.01
Num of Std Step Trials= 20
Max Error Tol= 0.3
Flow Tol Ratio= 0.001
Split Flow NTrial= 30
Split Flow Tol= 0.02
Split Flow Ratio= 0.02
Log Output Level= 0
Friction Slope Method= 1
Unsteady Friction Slope Method= 2
Parabolic Critical Depth
Global Vel Dist= 0 , 0 , 0
Global Log Level= 0
CheckData=True
Encroach Param=-1 ,0,0, 0
Computation Interval=1HOUR
Output Interval=1HOUR
Run HTab= 0
Run UNet= 0
Run PostProcess= 0
UNET Theta= 1
UNET ZTol= 0.02
UNET ZSATol= 0.1
UNET MxIter= 20
UNET MaxInSteps= 20
UNET DtIC= 0
UNET DtMin= 0
UNET MaxCRTS= 20
UNET WFStab= 2
UNET SFStab= 1
UNET WFX= 1
UNET SFX= 1
UNET Convert EG Bridges=-1
UNET Use Existing IB Tables=-1
Instantaneous Interval=1HOUR
Write IC File= 0
Write Velocity= 0
Write Detailed= 0

--- CHANG.f01 (steady flow) ---

Flow Title=Imported Flow 01
Version=Version 3.0.1  Mar 2001
Number of Profiles= 5
Profile Names=10YR,20YR,30YR,50YR,80YR
River Rch & RM=RIVER-1,Reach-1         ,2079.00
   23.58   25.98   27.39   29.16   30.79
River Rch & RM=RIVER-1,Reach-1         ,850.00
   30.19   33.28   35.09   37.36   39.45
Boundary for River Rch & Prof#=RIVER-1,Reach-1         , 1
Up Type= 0
Dn Type= 3
Dn Slope=.028
Boundary for River Rch & Prof#=RIVER-1,Reach-1         , 2
Up Type= 0
Dn Type= 3
Dn Slope=.028
Boundary for River Rch & Prof#=RIVER-1,Reach-1         , 3
Up Type= 0
Dn Type= 3
Dn Slope=.028
Boundary for River Rch & Prof#=RIVER-1,Reach-1         , 4
Up Type= 0
Dn Type= 3
Dn Slope=.028
Boundary for River Rch & Prof#=RIVER-1,Reach-1         , 5
Up Type= 0
Dn Type= 3
Dn Slope=.028
DSS Import GetInterval= 0
DSS Import GetPeak= 0
DSS Import FillOption= 0

--- CHANG.g01 (geometry) ---

Geom Title=Imported Geom 01
Version=Version 3.0.1  Mar 2001

River Reach=RIVER-1         ,Reach-1
Reach XY= 2
              .5             .95              .5             .05

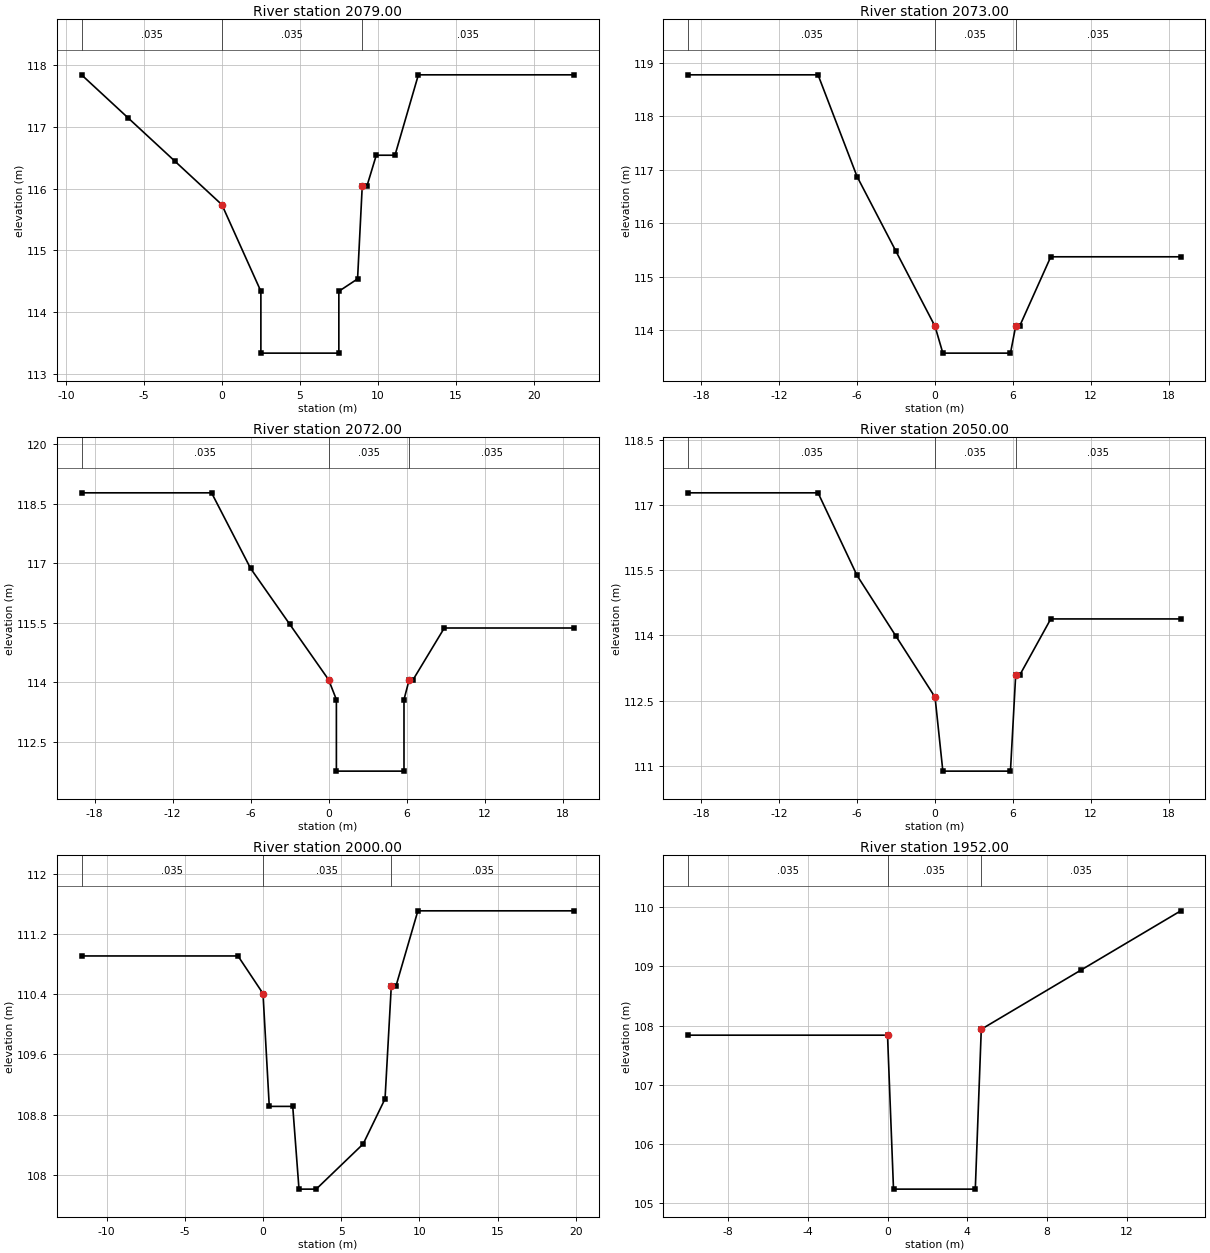
Type RM Length L Ch R = 1 ,2079.00 ,6,6,6
BEGIN DESCRIPTION:
41.029
END DESCRIPTION:
#Sta/Elev= 15
      -9  117.84      -6  117.14      -3  116.44       0  115.74     2.5  114.34
     2.5  113.34     7.5  113.34     7.5  114.34     8.7  114.54       9  116.04
     9.3  116.04     9.9  116.54    11.1  116.54    12.6  117.84    22.6  117.84
#Mann= 3 , 0 , 0
      -9    .035       0       0    .035       0       9    .035       0
#XS Ineff= 2 , 0
               0  115.74       9          116.04
Permanent Ineff=
       F       F
Bank Sta=0,9
XS Rating Curve= 0
Exp/Cntr=.3,.1

Type RM Length L Ch R = 1 ,2073.00 ,1,1,1
BEGIN DESCRIPTION:
41.023
END DESCRIPTION:
#Sta/Elev= 11
     -19  118.77      -9  118.77      -6  116.87      -3  115.47       0  114.07
      .6  113.57     5.8  113.57     6.2  114.07     6.5  114.07     8.9  115.37
    18.9  115.37
#Mann= 3 , 0 , 0
     -19    .035       0       0    .035       0     6.2    .035       0
#XS Ineff= 2 , 0
               0  114.07     6.2          114.07
Permanent Ineff=
       F       F
Bank Sta=0,6.2
XS Rating Curve= 0
Exp/Cntr=.3,.1

Type RM Length L Ch R = 1 ,2072.00 ,22,22,22
BEGIN DESCRIPTION:
41.022
END DESCRIPTION:
#Sta/Elev= 13
     -19  118.77      -9  118.77      -6  116.87      -3  115.47       0  114.07
      .6  113.57      .6  111.77     5.8  111.77     5.8  113.57     6.2  114.07
     6.5  114.07     8.9  115.37    18.9  115.37
#Mann= 3 , 0 , 0
     -19    .035       0       0    .035       0     6.2    .035       0
#XS Ineff= 2 , 0
               0  114.07     6.2          114.07
Permanent Ineff=
       F       F
Bank Sta=0,6.2
XS Rating Curve= 0
Exp/Cntr=.3,.1

Type RM Length L Ch R = 1 ,2050.00 ,50,50,50
BEGIN DESCRIPTION:
41
END DESCRIPTION:
#Sta/Elev= 11
     -19  117.28      -9  117.28      -6  115.38      -3  113.98       0  112.58
      .6  110.88     5.8  110.88     6.2  113.08     6.5  113.08     8.9  114.38
    18.9  114.38
#Mann= 3 , 0 , 0
     -19    .035       0       0    .035       0     6.2    .035       0
#XS Ineff= 2 , 0
               0  112.58     6.2          113.08
Permanent Ineff=
       F       F
Bank Sta=0,6.2
XS Rating Curve= 0
Exp/Cntr=.3,.1

Type RM Length L Ch R = 1 ,2000.00 ,48,48,48
BEGIN DESCRIPTION:
40
END DESCRIPTION:
#Sta/Elev= 13
   -11.6  110.91    -1.6  110.91       0  110.41      .4  108.91     1.9  108.91
     2.3  107.81     3.4  107.81     6.4  108.41     7.8  109.01     8.2  110.51
     8.5  110.51     9.9  111.51    19.9  111.51
#Mann= 3 , 0 , 0
   -11.6    .035       0       0    .035       0     8.2    .035       0
#XS Ineff= 2 , 0
               0  110.41     8.2          110.51
Permanent Ineff=
       F       F
Bank Sta=0,8.2
XS Rating Curve= 0
Exp/Cntr=.3,.1

Type RM Length L Ch R = 1 ,1952.00 ,2,2,2
BEGIN DESCRIPTION:
39.002
END DESCRIPTION:
#Sta/Elev= 7
     -10  107.84       0  107.84      .3  105.24     4.4  105.24     4.7  107.94
     9.7  108.94    14.7  109.94
#Mann= 3 , 0 , 0
     -10    .035       0       0    .035       0     4.7    .035       0
#XS Ineff= 2 , 0
               0  107.84     4.7          107.94
Permanent Ineff=
       F       F
Bank Sta=0,4.7
XS Rating Curve= 0
Exp/Cntr=.3,.1

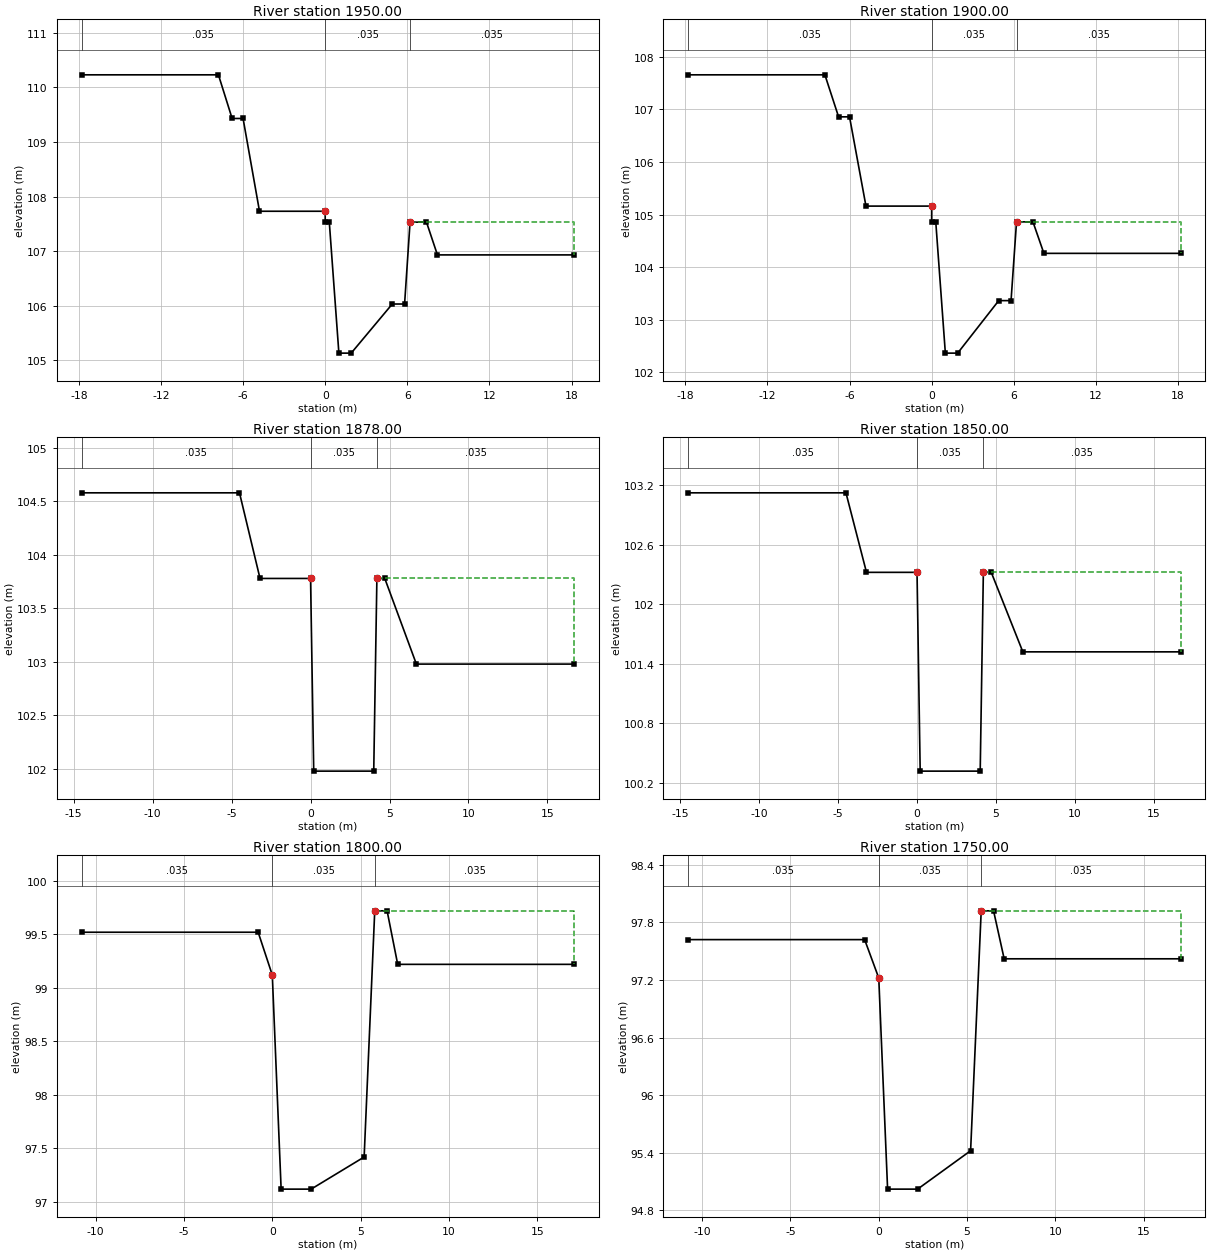
Type RM Length L Ch R = 1 ,1950.00 ,50,50,50
BEGIN DESCRIPTION:
39
END DESCRIPTION:
#Sta/Elev= 16
   -17.8  110.23    -7.8  110.23    -6.8  109.43      -6  109.43    -4.8  107.73
       0  107.73       0  107.53      .3  107.53       1  105.13     1.9  105.13
     4.9  106.03     5.8  106.03     6.2  107.53     7.4  107.53     8.2  106.93
    18.2  106.93
#Mann= 3 , 0 , 0
   -17.8    .035       0       0    .035       0     6.2    .035       0
#XS Ineff= 2 , 0
               0  107.73     6.2          107.53
Permanent Ineff=
       F       F
Bank Sta=0,6.2
XS Rating Curve= 0
Exp/Cntr=.3,.1

Type RM Length L Ch R = 1 ,1900.00 ,22,22,22
BEGIN DESCRIPTION:
38
END DESCRIPTION:
#Sta/Elev= 16
   -17.8  107.66    -7.8  107.66    -6.8  106.86      -6  106.86    -4.8  105.16
       0  105.16       0  104.86      .3  104.86       1  102.36     1.9  102.36
     4.9  103.36     5.8  103.36     6.2  104.86     7.4  104.86     8.2  104.26
    18.2  104.26
#Mann= 3 , 0 , 0
   -17.8    .035       0       0    .035       0     6.2    .035       0
#XS Ineff= 2 , 0
               0  105.16     6.2          104.86
Permanent Ineff=
       F       F
Bank Sta=0,6.2
XS Rating Curve= 0
Exp/Cntr=.3,.1

Type RM Length L Ch R = 1 ,1878.00 ,28,28,28
BEGIN DESCRIPTION:
37.028
END DESCRIPTION:
#Sta/Elev= 10
   -14.5  104.58    -4.5  104.58    -3.2  103.78       0  103.78      .2  101.98
       4  101.98     4.2  103.78     4.7  103.78     6.7  102.98    16.7  102.98
#Mann= 3 , 0 , 0
   -14.5    .035       0       0    .035       0     4.2    .035       0
#XS Ineff= 2 , 0
               0  103.78     4.2          103.78
Permanent Ineff=
       F       F
Bank Sta=0,4.2
XS Rating Curve= 0
Exp/Cntr=.3,.1

Type RM Length L Ch R = 1 ,1850.00 ,50,50,50
BEGIN DESCRIPTION:
37
END DESCRIPTION:
#Sta/Elev= 10
   -14.5  103.12    -4.5  103.12    -3.2  102.32       0  102.32      .2  100.32
       4  100.32     4.2  102.32     4.7  102.32     6.7  101.52    16.7  101.52
#Mann= 3 , 0 , 0
   -14.5    .035       0       0    .035       0     4.2    .035       0
#XS Ineff= 2 , 0
               0  102.32     4.2          102.32
Permanent Ineff=
       F       F
Bank Sta=0,4.2
XS Rating Curve= 0
Exp/Cntr=.3,.1

Type RM Length L Ch R = 1 ,1800.00 ,50,50,50
BEGIN DESCRIPTION:
36
END DESCRIPTION:
#Sta/Elev= 10
   -10.8   99.52     -.8   99.52       0   99.12      .5   97.12     2.2   97.12
     5.2   97.42     5.8   99.72     6.5   99.72     7.1   99.22    17.1   99.22
#Mann= 3 , 0 , 0
   -10.8    .035       0       0    .035       0     5.8    .035       0
#XS Ineff= 2 , 0
               0   99.12     5.8           99.72
Permanent Ineff=
       F       F
Bank Sta=0,5.8
XS Rating Curve= 0
Exp/Cntr=.3,.1

Type RM Length L Ch R = 1 ,1750.00 ,15,15,15
BEGIN DESCRIPTION:
35
END DESCRIPTION:
#Sta/Elev= 10
   -10.8   97.62     -.8   97.62       0   97.22      .5   95.02     2.2   95.02
     5.2   95.42     5.8   97.92     6.5   97.92     7.1   97.42    17.1   97.42
#Mann= 3 , 0 , 0
   -10.8    .035       0       0    .035       0     5.8    .035       0
#XS Ineff= 2 , 0
               0   97.22     5.8           97.92
Permanent Ineff=
       F       F
Bank Sta=0,5.8
XS Rating Curve= 0
Exp/Cntr=.3,.1

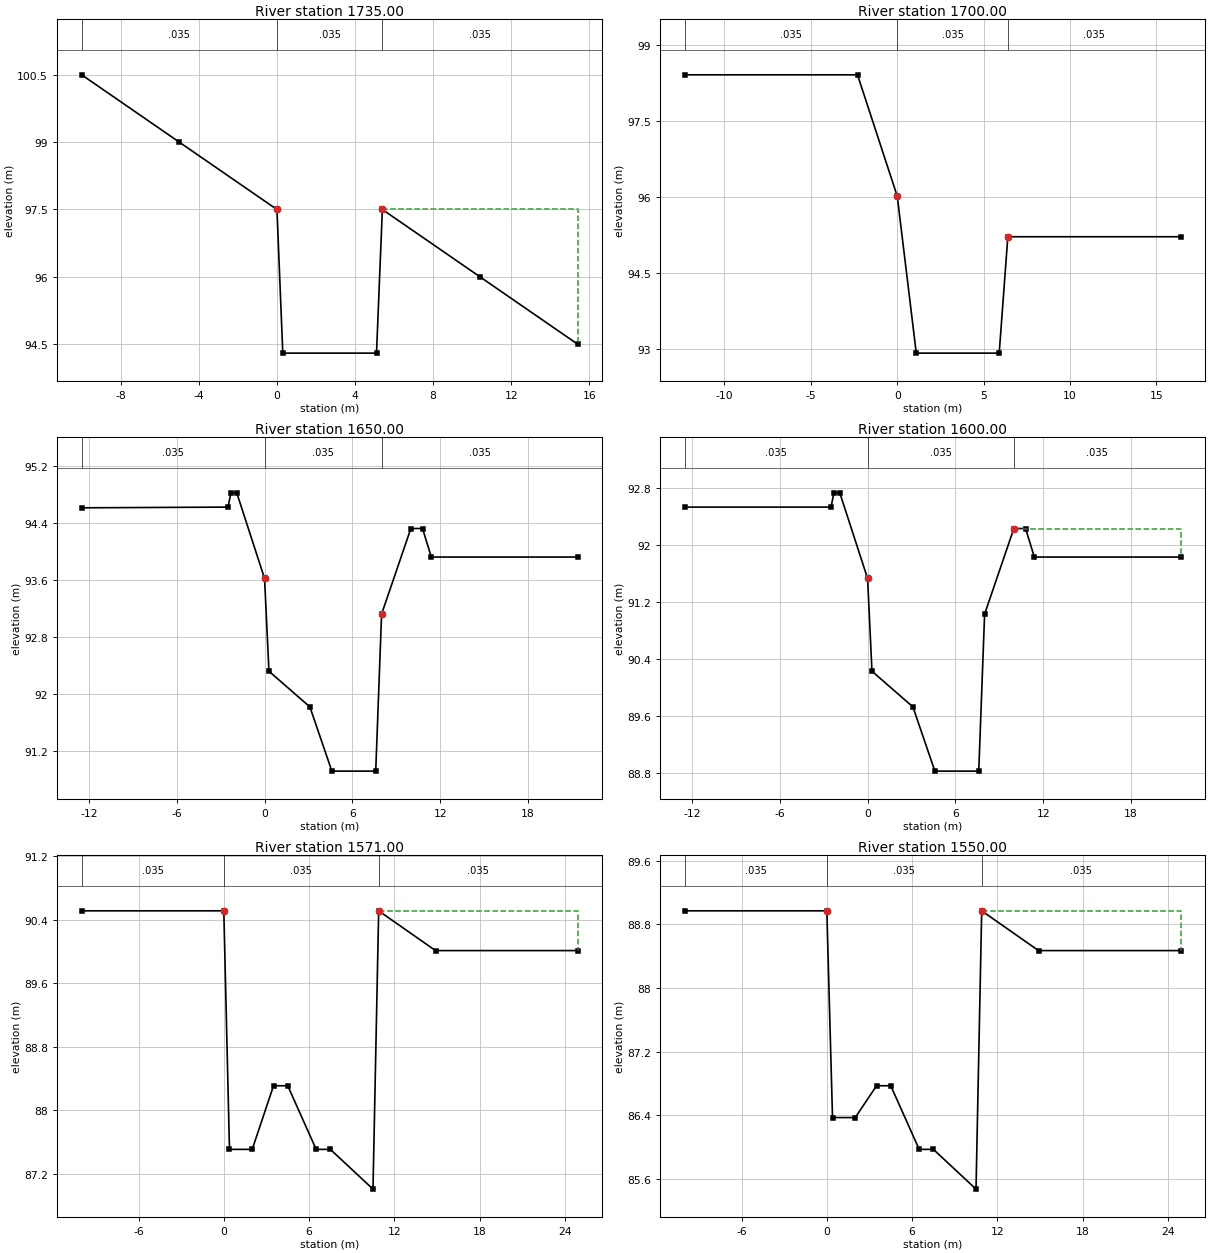
Type RM Length L Ch R = 1 ,1735.00 ,35,35,35
BEGIN DESCRIPTION:
34.035
END DESCRIPTION:
#Sta/Elev= 8
     -10   100.5      -5      99       0    97.5      .3    94.3     5.1    94.3
     5.4    97.5    10.4      96    15.4    94.5
#Mann= 3 , 0 , 0
     -10    .035       0       0    .035       0     5.4    .035       0
#XS Ineff= 2 , 0
               0    97.5     5.4            97.5
Permanent Ineff=
       F       F
Bank Sta=0,5.4
XS Rating Curve= 0
Exp/Cntr=.3,.1

Type RM Length L Ch R = 1 ,1700.00 ,50,50,50
BEGIN DESCRIPTION:
34
END DESCRIPTION:
#Sta/Elev= 7
   -12.3   98.41    -2.3   98.41       0   96.01     1.1   92.91     5.9   92.91
     6.4   95.21    16.4   95.21
#Mann= 3 , 0 , 0
   -12.3    .035       0       0    .035       0     6.4    .035       0
#XS Ineff= 2 , 0
               0   96.01     6.4           95.21
Permanent Ineff=
       F       F
Bank Sta=0,6.4
XS Rating Curve= 0
Exp/Cntr=.3,.1

Type RM Length L Ch R = 1 ,1650.00 ,50,50,50
BEGIN DESCRIPTION:
33
END DESCRIPTION:
#Sta/Elev= 14
   -12.5   94.61    -2.5   94.62    -2.3   94.82    -1.9   94.82       0   93.62
      .3   92.32     3.1   91.82     4.6   90.92     7.6   90.92       8   93.12
      10   94.32    10.8   94.32    11.4   93.92    21.4   93.92
#Mann= 3 , 0 , 0
   -12.5    .035       0       0    .035       0       8    .035       0
#XS Ineff= 2 , 0
               0   93.62       8           93.12
Permanent Ineff=
       F       F
Bank Sta=0,8
XS Rating Curve= 0
Exp/Cntr=.3,.1

Type RM Length L Ch R = 1 ,1600.00 ,29,29,29
BEGIN DESCRIPTION:
32
END DESCRIPTION:
#Sta/Elev= 14
   -12.5   92.53    -2.5   92.53    -2.3   92.73    -1.9   92.73       0   91.53
      .3   90.23     3.1   89.73     4.6   88.83     7.6   88.83       8   91.03
      10   92.23    10.8   92.23    11.4   91.83    21.4   91.83
#Mann= 3 , 0 , 0
   -12.5    .035       0       0    .035       0      10    .035       0
#XS Ineff= 2 , 0
               0   91.53      10           92.23
Permanent Ineff=
       F       F
Bank Sta=0,10
XS Rating Curve= 0
Exp/Cntr=.3,.1

Type RM Length L Ch R = 1 ,1571.00 ,21,21,21
BEGIN DESCRIPTION:
31.021
END DESCRIPTION:
#Sta/Elev= 12
     -10   90.51       0   90.51      .4   87.51       2   87.51     3.5   88.31
     4.5   88.31     6.5   87.51     7.5   87.51    10.5   87.01    10.9   90.51
    14.9   90.01    24.9   90.01
#Mann= 3 , 0 , 0
     -10    .035       0       0    .035       0    10.9    .035       0
#XS Ineff= 2 , 0
               0   90.51    10.9           90.51
Permanent Ineff=
       F       F
Bank Sta=0,10.9
XS Rating Curve= 0
Exp/Cntr=.3,.1

Type RM Length L Ch R = 1 ,1550.00 ,50,50,50
BEGIN DESCRIPTION:
31
END DESCRIPTION:
#Sta/Elev= 12
     -10   88.97       0   88.97      .4   86.37       2   86.37     3.5   86.77
     4.5   86.77     6.5   85.97     7.5   85.97    10.5   85.47    10.9   88.97
    14.9   88.47    24.9   88.47
#Mann= 3 , 0 , 0
     -10    .035       0       0    .035       0    10.9    .035       0
#XS Ineff= 2 , 0
               0   88.97    10.9           88.97
Permanent Ineff=
       F       F
Bank Sta=0,10.9
XS Rating Curve= 0
Exp/Cntr=.3,.1

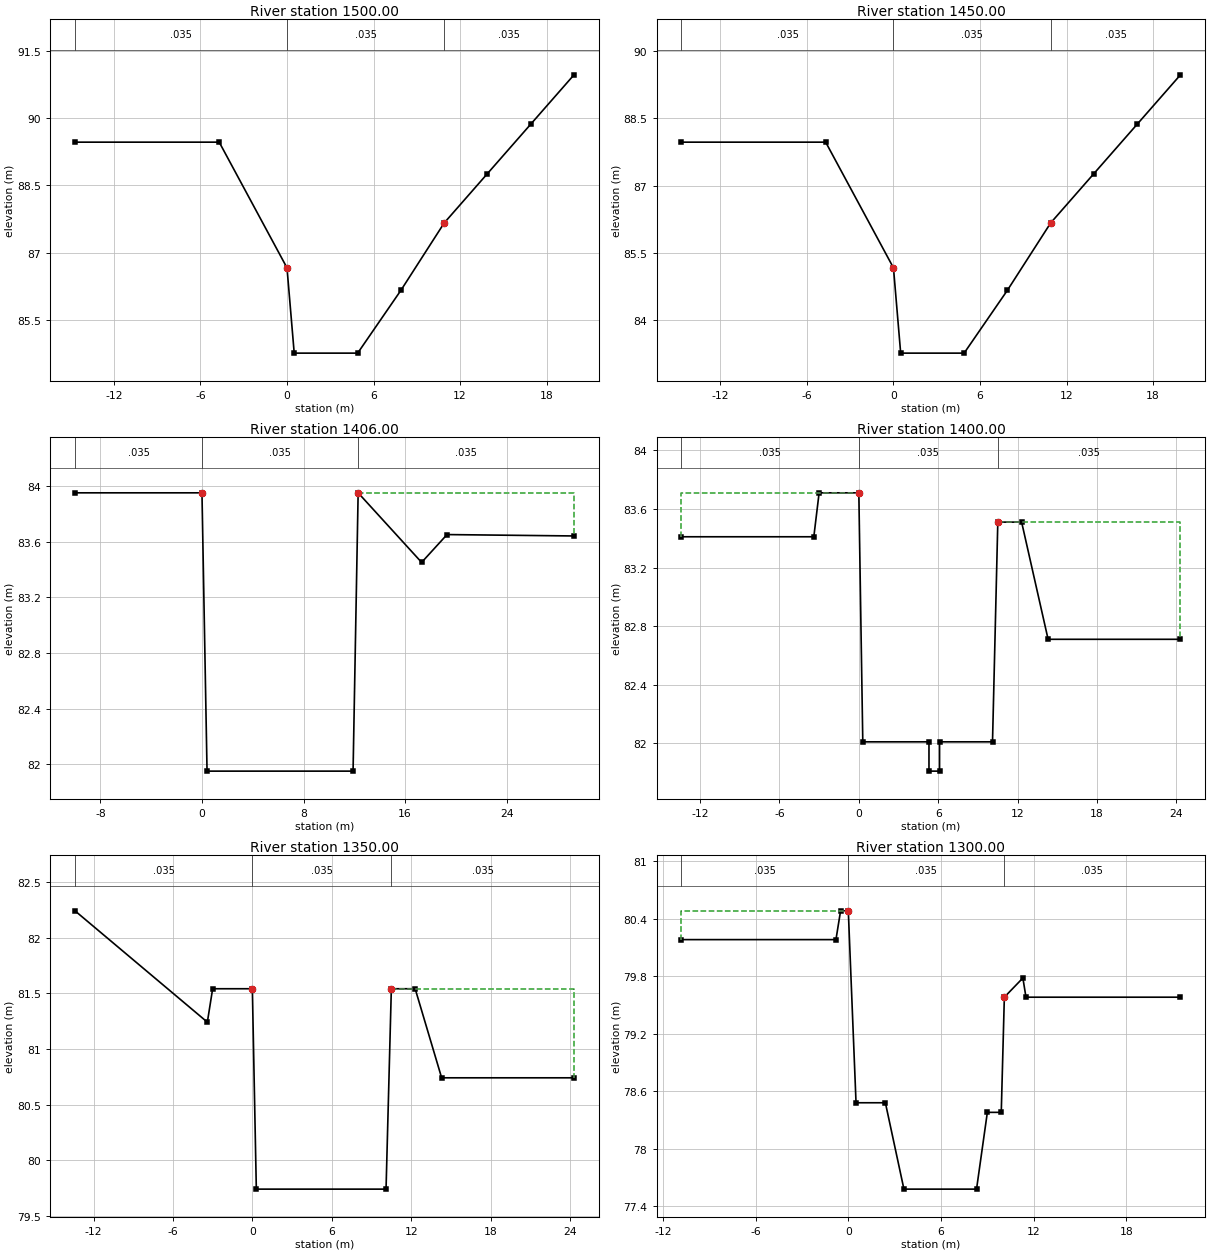
Type RM Length L Ch R = 1 ,1500.00 ,50,50,50
BEGIN DESCRIPTION:
30
END DESCRIPTION:
#Sta/Elev= 10
   -14.7   89.46    -4.7   89.46       0   86.66      .5   84.76     4.9   84.76
     7.9   86.16    10.9   87.66    13.9   88.76    16.9   89.86    19.9   90.96
#Mann= 3 , 0 , 0
   -14.7    .035       0       0    .035       0    10.9    .035       0
#XS Ineff= 2 , 0
               0   86.66    10.9           87.66
Permanent Ineff=
       F       F
Bank Sta=0,10.9
XS Rating Curve= 0
Exp/Cntr=.3,.1

Type RM Length L Ch R = 1 ,1450.00 ,44,44,44
BEGIN DESCRIPTION:
29
END DESCRIPTION:
#Sta/Elev= 10
   -14.7   87.97    -4.7   87.97       0   85.17      .5   83.27     4.9   83.27
     7.9   84.67    10.9   86.17    13.9   87.27    16.9   88.37    19.9   89.47
#Mann= 3 , 0 , 0
   -14.7    .035       0       0    .035       0    10.9    .035       0
#XS Ineff= 2 , 0
               0   85.17    10.9           86.17
Permanent Ineff=
       F       F
Bank Sta=0,10.9
XS Rating Curve= 0
Exp/Cntr=.3,.1

Type RM Length L Ch R = 1 ,1406.00 ,6,6,6
BEGIN DESCRIPTION:
28.006
END DESCRIPTION:
#Sta/Elev= 8
     -10   83.95       0   83.95      .4   81.95    11.9   81.95    12.3   83.95
    17.3   83.45    19.3   83.65    29.3   83.64
#Mann= 3 , 0 , 0
     -10    .035       0       0    .035       0    12.3    .035       0
#XS Ineff= 2 , 0
               0   83.95    12.3           83.95
Permanent Ineff=
       F       F
Bank Sta=0,12.3
XS Rating Curve= 0
Exp/Cntr=.3,.1

Type RM Length L Ch R = 1 ,1400.00 ,50,50,50
BEGIN DESCRIPTION:
28
END DESCRIPTION:
#Sta/Elev= 14
   -13.4   83.41    -3.4   83.41      -3   83.71       0   83.71      .3   82.01
     5.3   82.01     5.3   81.81     6.1   81.81     6.1   82.01    10.1   82.01
    10.5   83.51    12.3   83.51    14.3   82.71    24.3   82.71
#Mann= 3 , 0 , 0
   -13.4    .035       0       0    .035       0    10.5    .035       0
#XS Ineff= 2 , 0
               0   83.71    10.5           83.51
Permanent Ineff=
       F       F
Bank Sta=0,10.5
XS Rating Curve= 0
Exp/Cntr=.3,.1

Type RM Length L Ch R = 1 ,1350.00 ,50,50,50
BEGIN DESCRIPTION:
27
END DESCRIPTION:
#Sta/Elev= 10
   -13.4   82.24    -3.4   81.24      -3   81.54       0   81.54      .3   79.74
    10.1   79.74    10.5   81.54    12.3   81.54    14.3   80.74    24.3   80.74
#Mann= 3 , 0 , 0
   -13.4    .035       0       0    .035       0    10.5    .035       0
#XS Ineff= 2 , 0
               0   81.54    10.5           81.54
Permanent Ineff=
       F       F
Bank Sta=0,10.5
XS Rating Curve= 0
Exp/Cntr=.3,.1

Type RM Length L Ch R = 1 ,1300.00 ,50,50,50
BEGIN DESCRIPTION:
26
END DESCRIPTION:
#Sta/Elev= 14
   -10.8   80.18     -.8   80.18     -.5   80.48       0   80.48      .5   78.48
     2.4   78.48     3.6   77.58     8.3   77.58       9   78.38     9.9   78.38
    10.1   79.58    11.3   79.78    11.5   79.58    21.5   79.58
#Mann= 3 , 0 , 0
   -10.8    .035       0       0    .035       0    10.1    .035       0
#XS Ineff= 2 , 0
               0   80.48    10.1           79.58
Permanent Ineff=
       F       F
Bank Sta=0,10.1
XS Rating Curve= 0
Exp/Cntr=.3,.1

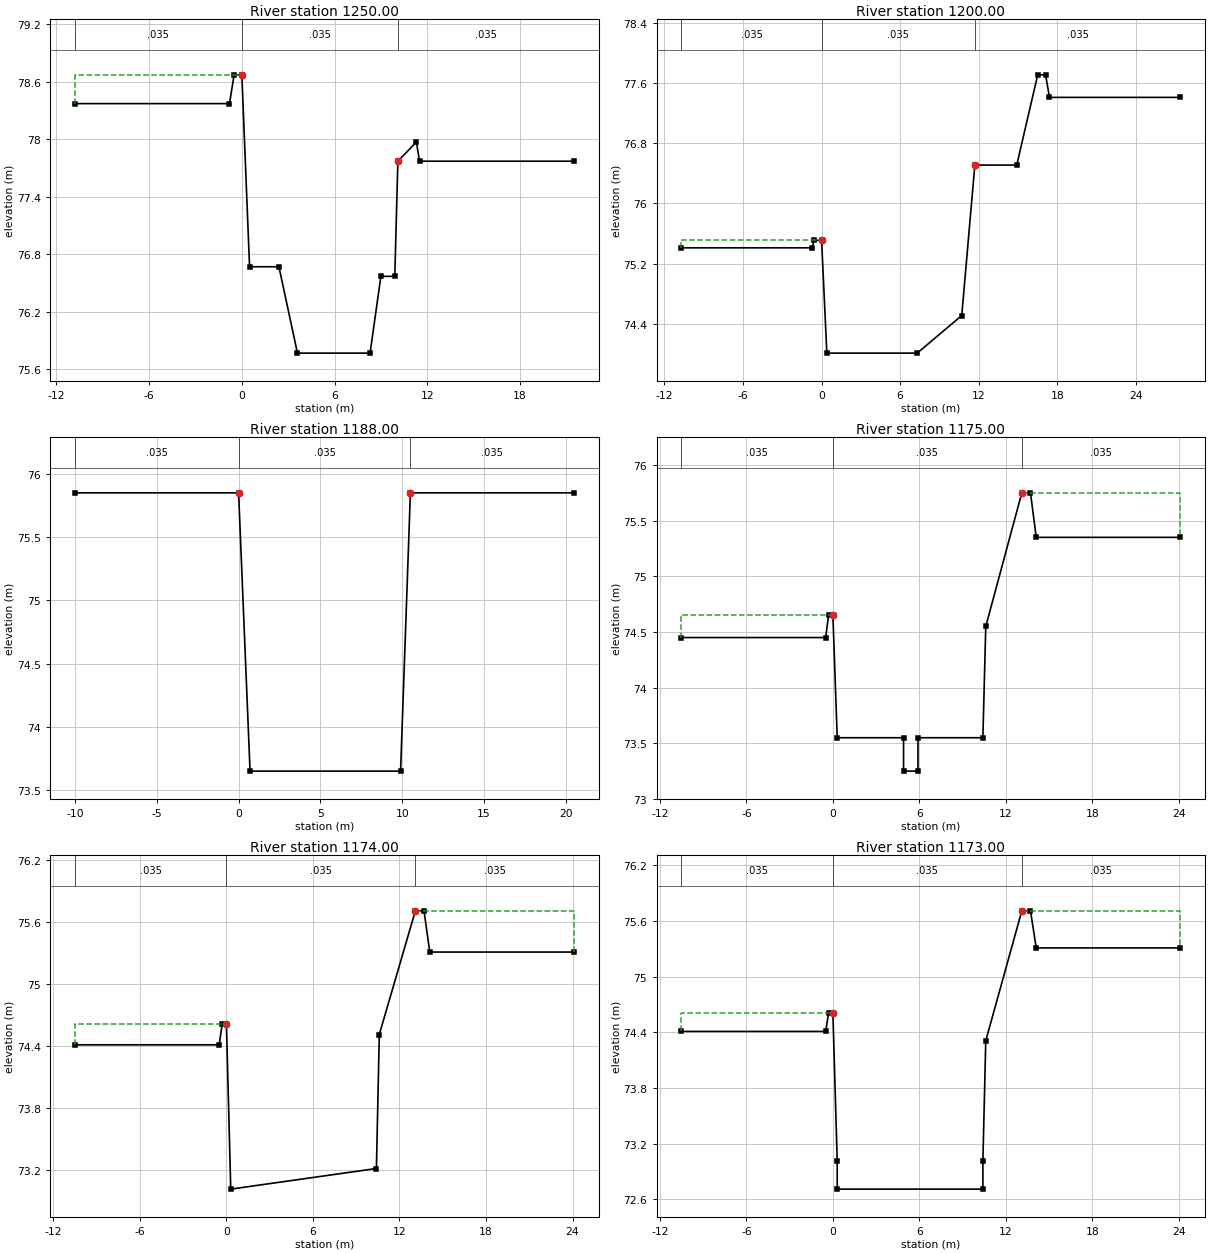
Type RM Length L Ch R = 1 ,1250.00 ,50,50,50
BEGIN DESCRIPTION:
25
END DESCRIPTION:
#Sta/Elev= 14
   -10.8   78.37     -.8   78.37     -.5   78.67       0   78.67      .5   76.67
     2.4   76.67     3.6   75.77     8.3   75.77       9   76.57     9.9   76.57
    10.1   77.77    11.3   77.97    11.5   77.77    21.5   77.77
#Mann= 3 , 0 , 0
   -10.8    .035       0       0    .035       0    10.1    .035       0
#XS Ineff= 2 , 0
               0   78.67    10.1           77.77
Permanent Ineff=
       F       F
Bank Sta=0,10.1
XS Rating Curve= 0
Exp/Cntr=.3,.1

Type RM Length L Ch R = 1 ,1200.00 ,12,12,12
BEGIN DESCRIPTION:
24
END DESCRIPTION:
#Sta/Elev= 13
   -10.7   75.41     -.7   75.41     -.6   75.51       0   75.51      .4   74.01
     7.3   74.01    10.7   74.51    11.7   76.51    14.9   76.51    16.5   77.71
    17.1   77.71    17.4   77.41    27.4   77.41
#Mann= 3 , 0 , 0
   -10.7    .035       0       0    .035       0    11.7    .035       0
#XS Ineff= 2 , 0
               0   75.51    11.7           76.51
Permanent Ineff=
       F       F
Bank Sta=0,11.7
XS Rating Curve= 0
Exp/Cntr=.3,.1

Type RM Length L Ch R = 1 ,1188.00 ,13,13,13
BEGIN DESCRIPTION:
23.038
END DESCRIPTION:
#Sta/Elev= 6
     -10   75.85       0   75.85      .7   73.65     9.9   73.65    10.5   75.85
    20.5   75.85
#Mann= 3 , 0 , 0
     -10    .035       0       0    .035       0    10.5    .035       0
#XS Ineff= 2 , 0
               0   75.85    10.5           75.85
Permanent Ineff=
       F       F
Bank Sta=0,10.5
XS Rating Curve= 0
Exp/Cntr=.3,.1

Type RM Length L Ch R = 1 ,1175.00 ,1,1,1
BEGIN DESCRIPTION:
23.025
END DESCRIPTION:
#Sta/Elev= 15
   -10.5   74.45     -.5   74.45     -.3   74.65       0   74.65      .3   73.55
     4.9   73.55     4.9   73.25     5.9   73.25     5.9   73.55    10.4   73.55
    10.6   74.55    13.1   75.75    13.7   75.75    14.1   75.35    24.1   75.35
#Mann= 3 , 0 , 0
   -10.5    .035       0       0    .035       0    13.1    .035       0
#XS Ineff= 2 , 0
               0   74.65    13.1           75.75
Permanent Ineff=
       F       F
Bank Sta=0,13.1
XS Rating Curve= 0
Exp/Cntr=.3,.1

Type RM Length L Ch R = 1 ,1174.00 ,1,1,1
BEGIN DESCRIPTION:
23.024
END DESCRIPTION:
#Sta/Elev= 11
   -10.5   74.41     -.5   74.41     -.3   74.61       0   74.61      .3   73.01
    10.4   73.21    10.6   74.51    13.1   75.71    13.7   75.71    14.1   75.31
    24.1   75.31
#Mann= 3 , 0 , 0
   -10.5    .035       0       0    .035       0    13.1    .035       0
#XS Ineff= 2 , 0
               0   74.61    13.1           75.71
Permanent Ineff=
       F       F
Bank Sta=0,13.1
XS Rating Curve= 0
Exp/Cntr=.3,.1

Type RM Length L Ch R = 1 ,1173.00 ,23,23,23
BEGIN DESCRIPTION:
23.023
END DESCRIPTION:
#Sta/Elev= 13
   -10.5   74.41     -.5   74.41     -.3   74.61       0   74.61      .3   73.01
      .3   72.71    10.4   72.71    10.4   73.01    10.6   74.31    13.1   75.71
    13.7   75.71    14.1   75.31    24.1   75.31
#Mann= 3 , 0 , 0
   -10.5    .035       0       0    .035       0    13.1    .035       0
#XS Ineff= 2 , 0
               0   74.61    13.1           75.71
Permanent Ineff=
       F       F
Bank Sta=0,13.1
XS Rating Curve= 0
Exp/Cntr=.3,.1

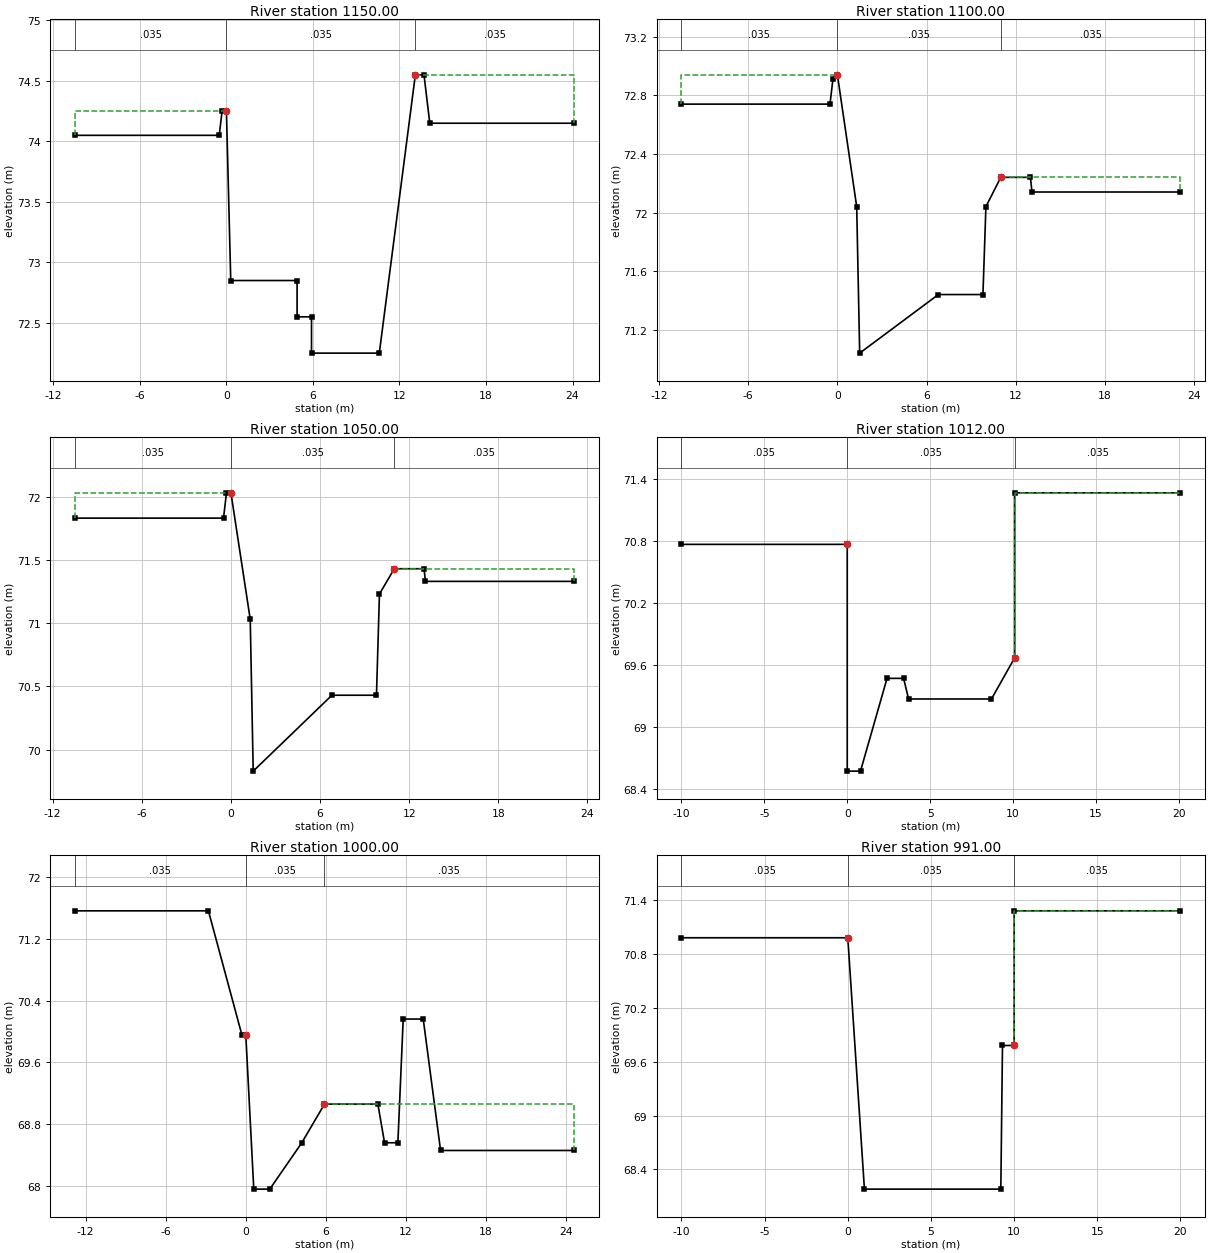
Type RM Length L Ch R = 1 ,1150.00 ,50,50,50
BEGIN DESCRIPTION:
23
END DESCRIPTION:
#Sta/Elev= 14
   -10.5   74.05     -.5   74.05     -.3   74.25       0   74.25      .3   72.85
     4.9   72.85     4.9   72.55     5.9   72.55     5.9   72.25    10.6   72.25
    13.1   74.55    13.7   74.55    14.1   74.15    24.1   74.15
#Mann= 3 , 0 , 0
   -10.5    .035       0       0    .035       0    13.1    .035       0
#XS Ineff= 2 , 0
               0   74.25    13.1           74.55
Permanent Ineff=
       F       F
Bank Sta=0,13.1
XS Rating Curve= 0
Exp/Cntr=.3,.1

Type RM Length L Ch R = 1 ,1100.00 ,50,50,50
BEGIN DESCRIPTION:
22
END DESCRIPTION:
#Sta/Elev= 13
   -10.5   72.74     -.5   72.74     -.3   72.91       0   72.94     1.3   72.04
     1.5   71.04     6.8   71.44     9.8   71.44      10   72.04      11   72.24
      13   72.24    13.1   72.14    23.1   72.14
#Mann= 3 , 0 , 0
   -10.5    .035       0       0    .035       0      11    .035       0
#XS Ineff= 2 , 0
               0   72.94      11           72.24
Permanent Ineff=
       F       F
Bank Sta=0,11
XS Rating Curve= 0
Exp/Cntr=.3,.1

Type RM Length L Ch R = 1 ,1050.00 ,38,38,38
BEGIN DESCRIPTION:
21
END DESCRIPTION:
#Sta/Elev= 13
   -10.5   71.83     -.5   71.83     -.3   72.03       0   72.03     1.3   71.03
     1.5   69.83     6.8   70.43     9.8   70.43      10   71.23      11   71.43
      13   71.43    13.1   71.33    23.1   71.33
#Mann= 3 , 0 , 0
   -10.5    .035       0       0    .035       0      11    .035       0
#XS Ineff= 2 , 0
               0   72.03      11           71.43
Permanent Ineff=
       F       F
Bank Sta=0,11
XS Rating Curve= 0
Exp/Cntr=.3,.1

Type RM Length L Ch R = 1 ,1012.00 ,12,12,12
BEGIN DESCRIPTION:
20.012
END DESCRIPTION:
#Sta/Elev= 11
     -10   70.77       0   70.77       0   68.57      .8   68.57     2.4   69.47
     3.4   69.47     3.7   69.27     8.7   69.27    10.1   69.67    10.1   71.27
    20.1   71.27
#Mann= 3 , 0 , 0
     -10    .035       0       0    .035       0    10.1    .035       0
#XS Ineff= 2 , 0
               0   70.77    10.1           71.27
Permanent Ineff=
       F       F
Bank Sta=0,10.1
XS Rating Curve= 0
Exp/Cntr=.3,.1

Type RM Length L Ch R = 1 ,1000.00 ,9,9,9
BEGIN DESCRIPTION:
20
END DESCRIPTION:
#Sta/Elev= 15
   -12.8   71.56    -2.8   71.56     -.3   69.96       0   69.96      .6   67.96
     1.8   67.96     4.2   68.56     5.9   69.06     9.9   69.06    10.4   68.56
    11.4   68.56    11.8   70.16    13.3   70.16    14.6   68.46    24.6   68.46
#Mann= 3 , 0 , 0
   -12.8    .035       0       0    .035       0     5.9    .035       0
#XS Ineff= 2 , 0
               0   69.96     5.9           69.06
Permanent Ineff=
       F       F
Bank Sta=0,5.9
XS Rating Curve= 0
Exp/Cntr=.3,.1

Type RM Length L Ch R = 1 ,991.00  ,5,5,5
BEGIN DESCRIPTION:
19.041
END DESCRIPTION:
#Sta/Elev= 8
     -10   70.98       0   70.98       1   68.18     9.2   68.18     9.3   69.78
      10   69.78      10   71.28      20   71.28
#Mann= 3 , 0 , 0
     -10    .035       0       0    .035       0      10    .035       0
#XS Ineff= 2 , 0
               0   70.98      10           71.28
Permanent Ineff=
       F       F
Bank Sta=0,10
XS Rating Curve= 0
Exp/Cntr=.3,.1

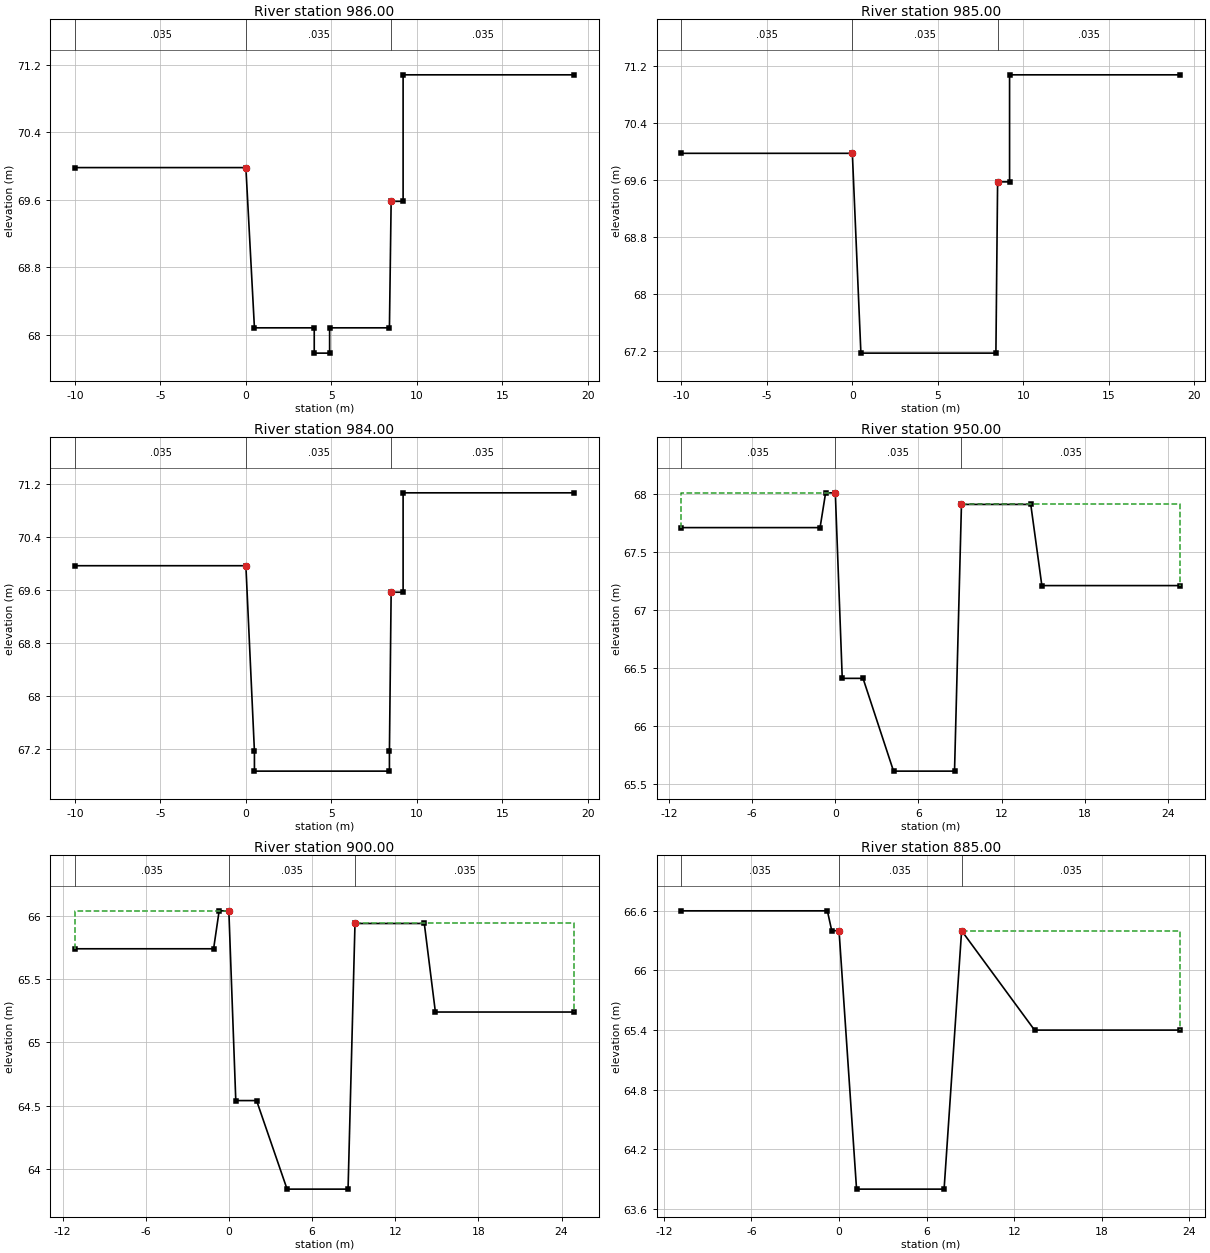
Type RM Length L Ch R = 1 ,986.00  ,1,1,1
BEGIN DESCRIPTION:
19.036
END DESCRIPTION:
#Sta/Elev= 12
     -10   69.98       0   69.98      .5   68.08       4   68.08       4   67.78
     4.9   67.78     4.9   68.08     8.4   68.08     8.5   69.58     9.2   69.58
     9.2   71.08    19.2   71.08
#Mann= 3 , 0 , 0
     -10    .035       0       0    .035       0     8.5    .035       0
#XS Ineff= 2 , 0
               0   69.98     8.5           69.58
Permanent Ineff=
       F       F
Bank Sta=0,8.5
XS Rating Curve= 0
Exp/Cntr=.3,.1

Type RM Length L Ch R = 1 ,985.00  ,1,1,1
BEGIN DESCRIPTION:
19.035
END DESCRIPTION:
#Sta/Elev= 8
     -10   69.97       0   69.97      .5   67.17     8.4   67.17     8.5   69.57
     9.2   69.57     9.2   71.07    19.2   71.07
#Mann= 3 , 0 , 0
     -10    .035       0       0    .035       0     8.5    .035       0
#XS Ineff= 2 , 0
               0   69.97     8.5           69.57
Permanent Ineff=
       F       F
Bank Sta=0,8.5
XS Rating Curve= 0
Exp/Cntr=.3,.1

Type RM Length L Ch R = 1 ,984.00  ,34,34,34
BEGIN DESCRIPTION:
19.034
END DESCRIPTION:
#Sta/Elev= 10
     -10   69.97       0   69.97      .5   67.17      .5   66.87     8.4   66.87
     8.4   67.17     8.5   69.57     9.2   69.57     9.2   71.07    19.2   71.07
#Mann= 3 , 0 , 0
     -10    .035       0       0    .035       0     8.5    .035       0
#XS Ineff= 2 , 0
               0   69.97     8.5           69.57
Permanent Ineff=
       F       F
Bank Sta=0,8.5
XS Rating Curve= 0
Exp/Cntr=.3,.1

Type RM Length L Ch R = 1 ,950.00  ,50,50,50
BEGIN DESCRIPTION:
19
END DESCRIPTION:
#Sta/Elev= 12
   -11.1   67.71    -1.1   67.71     -.7   68.01       0   68.01      .5   66.41
       2   66.41     4.2   65.61     8.6   65.61     9.1   67.91    14.1   67.91
    14.9   67.21    24.9   67.21
#Mann= 3 , 0 , 0
   -11.1    .035       0       0    .035       0     9.1    .035       0
#XS Ineff= 2 , 0
               0   68.01     9.1           67.91
Permanent Ineff=
       F       F
Bank Sta=0,9.1
XS Rating Curve= 0
Exp/Cntr=.3,.1

Type RM Length L Ch R = 1 ,900.00  ,15,15,15
BEGIN DESCRIPTION:
18
END DESCRIPTION:
#Sta/Elev= 12
   -11.1   65.74    -1.1   65.74     -.7   66.04       0   66.04      .5   64.54
       2   64.54     4.2   63.84     8.6   63.84     9.1   65.94    14.1   65.94
    14.9   65.24    24.9   65.24
#Mann= 3 , 0 , 0
   -11.1    .035       0       0    .035       0     9.1    .035       0
#XS Ineff= 2 , 0
               0   66.04     9.1           65.94
Permanent Ineff=
       F       F
Bank Sta=0,9.1
XS Rating Curve= 0
Exp/Cntr=.3,.1

Type RM Length L Ch R = 1 ,885.00  ,35,35,35
BEGIN DESCRIPTION:
17.035
END DESCRIPTION:
#Sta/Elev= 9
   -10.8    66.6     -.8    66.6     -.5    66.4       0    66.4     1.2    63.8
     7.2    63.8     8.4    66.4    13.4    65.4    23.4    65.4
#Mann= 3 , 0 , 0
   -10.8    .035       0       0    .035       0     8.4    .035       0
#XS Ineff= 2 , 0
               0    66.4     8.4            66.4
Permanent Ineff=
       F       F
Bank Sta=0,8.4
XS Rating Curve= 0
Exp/Cntr=.3,.1