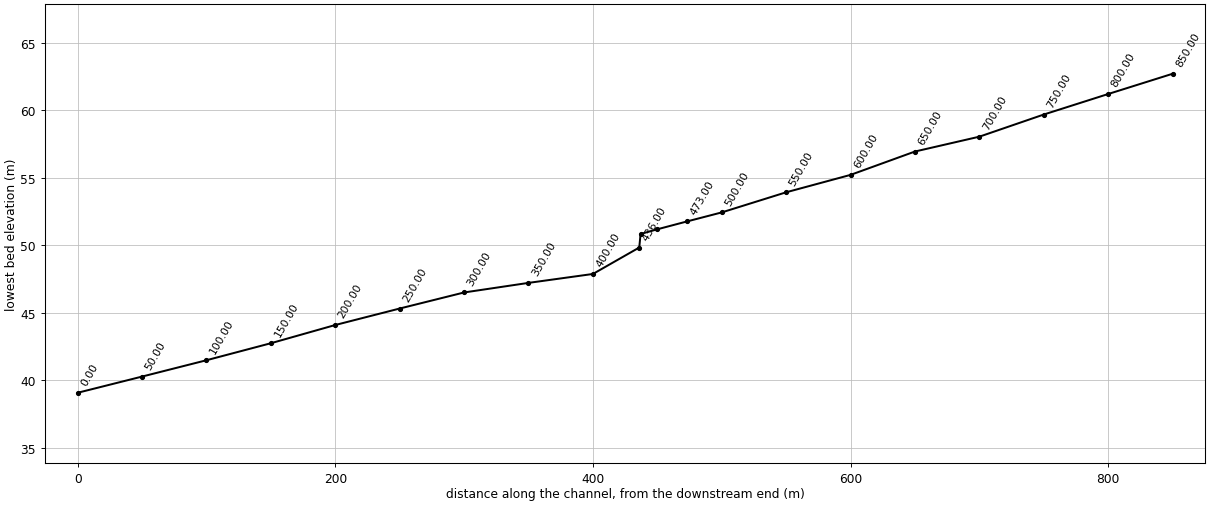
HEC-RAS study CHANG.prj: changdong-chu

--- CHANG.g01 (geometry) --- (continued)

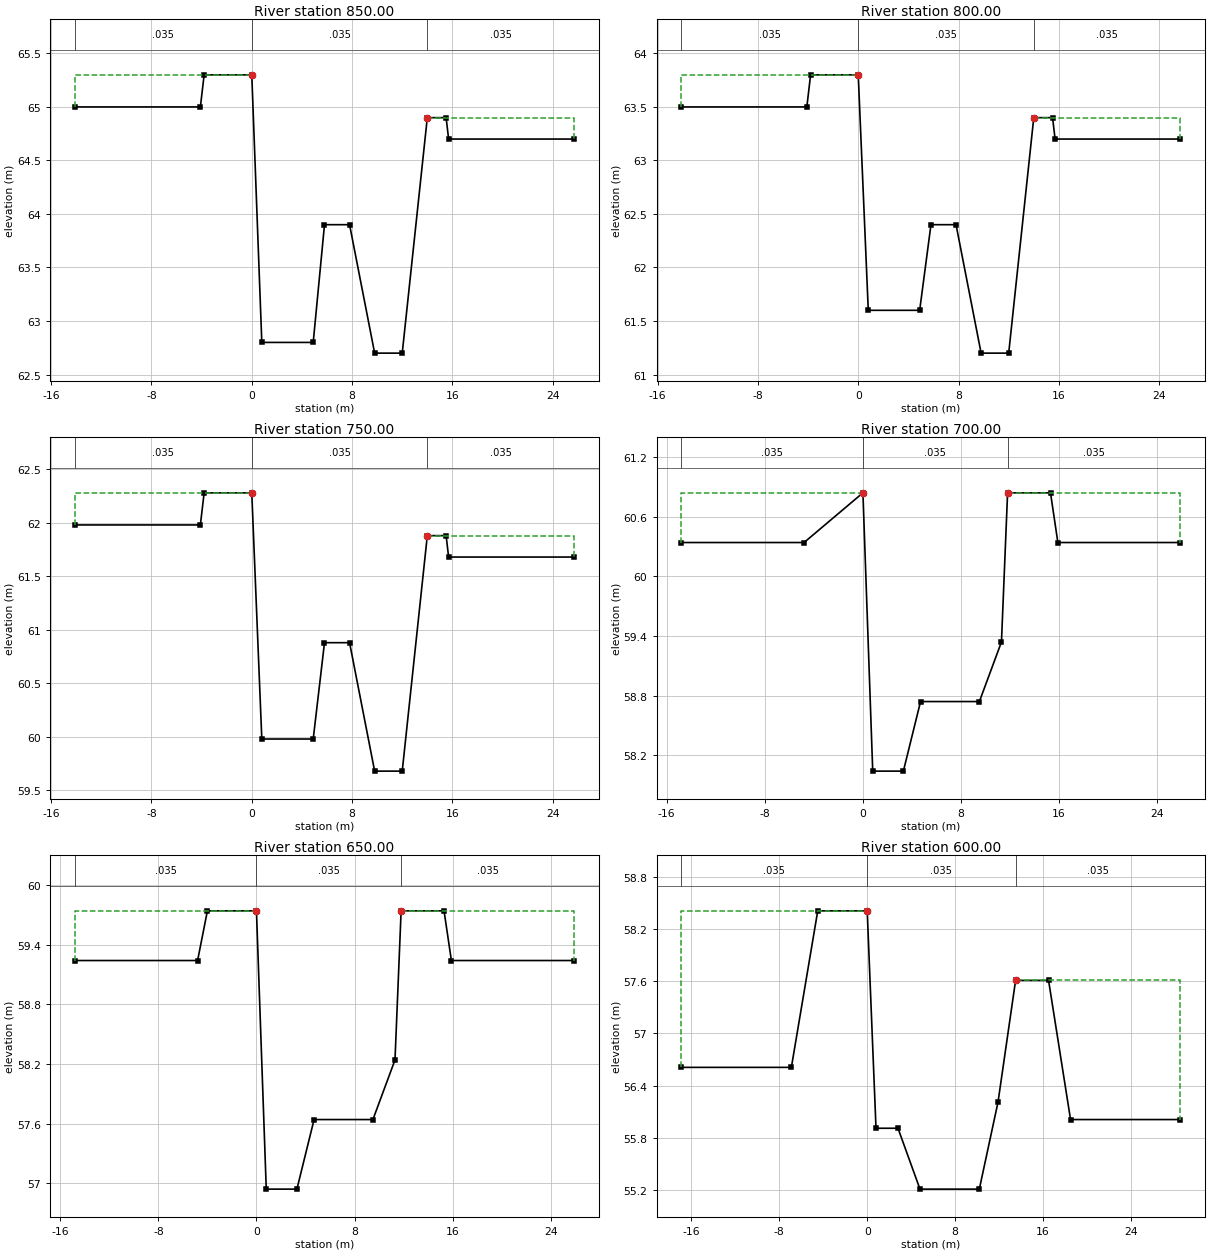
Type RM Length L Ch R = 1 ,850.00  ,50,50,50
BEGIN DESCRIPTION:
17
END DESCRIPTION:
#Sta/Elev= 14
   -14.1      65    -4.1      65    -3.8    65.3       0    65.3      .8    62.8
     4.9    62.8     5.8    63.9     7.8    63.9     9.8    62.7      12    62.7
      14    64.9    15.5    64.9    15.7    64.7    25.7    64.7
#Mann= 3 , 0 , 0
   -14.1    .035       0       0    .035       0      14    .035       0
#XS Ineff= 2 , 0
               0    65.3      14            64.9
Permanent Ineff=
       F       F
Bank Sta=0,14
XS Rating Curve= 0
Exp/Cntr=.3,.1

Type RM Length L Ch R = 1 ,800.00  ,50,50,50
BEGIN DESCRIPTION:
16
END DESCRIPTION:
#Sta/Elev= 14
   -14.1    63.5    -4.1    63.5    -3.8    63.8       0    63.8      .8    61.6
     4.9    61.6     5.8    62.4     7.8    62.4     9.8    61.2      12    61.2
      14    63.4    15.5    63.4    15.7    63.2    25.7    63.2
#Mann= 3 , 0 , 0
   -14.1    .035       0       0    .035       0      14    .035       0
#XS Ineff= 2 , 0
               0    63.8      14            63.4
Permanent Ineff=
       F       F
Bank Sta=0,14
XS Rating Curve= 0
Exp/Cntr=.3,.1

Type RM Length L Ch R = 1 ,750.00  ,50,50,50
BEGIN DESCRIPTION:
15
END DESCRIPTION:
#Sta/Elev= 14
   -14.1   61.98    -4.1   61.98    -3.8   62.28       0   62.28      .8   59.98
     4.9   59.98     5.8   60.88     7.8   60.88     9.8   59.68      12   59.68
      14   61.88    15.5   61.88    15.7   61.68    25.7   61.68
#Mann= 3 , 0 , 0
   -14.1    .035       0       0    .035       0      14    .035       0
#XS Ineff= 2 , 0
               0   62.28      14           61.88
Permanent Ineff=
       F       F
Bank Sta=0,14
XS Rating Curve= 0
Exp/Cntr=.3,.1

Type RM Length L Ch R = 1 ,700.00  ,50,50,50
BEGIN DESCRIPTION:
14
END DESCRIPTION:
#Sta/Elev= 12
   -14.8   60.34    -4.8   60.34       0   60.84      .8   58.04     3.3   58.04
     4.7   58.74     9.5   58.74    11.3   59.34    11.8   60.84    15.3   60.84
    15.9   60.34    25.9   60.34
#Mann= 3 , 0 , 0
   -14.8    .035       0       0    .035       0    11.8    .035       0
#XS Ineff= 2 , 0
               0   60.84    11.8           60.84
Permanent Ineff=
       F       F
Bank Sta=0,11.8
XS Rating Curve= 0
Exp/Cntr=.3,.1

Type RM Length L Ch R = 1 ,650.00  ,50,50,50
BEGIN DESCRIPTION:
13
END DESCRIPTION:
#Sta/Elev= 13
   -14.8   59.24    -4.8   59.24      -4   59.74       0   59.74      .8   56.94
     3.3   56.94     4.7   57.64     9.5   57.64    11.3   58.24    11.8   59.74
    15.3   59.74    15.9   59.24    25.9   59.24
#Mann= 3 , 0 , 0
   -14.8    .035       0       0    .035       0    11.8    .035       0
#XS Ineff= 2 , 0
               0   59.74    11.8           59.74
Permanent Ineff=
       F       F
Bank Sta=0,11.8
XS Rating Curve= 0
Exp/Cntr=.3,.1

Type RM Length L Ch R = 1 ,600.00  ,50,50,50
BEGIN DESCRIPTION:
12
END DESCRIPTION:
#Sta/Elev= 13
   -16.9   56.61    -6.9   56.61    -4.5   58.41       0   58.41      .8   55.91
     2.8   55.91     4.8   55.21    10.2   55.21    11.9   56.21    13.5   57.61
    16.5   57.61    18.5   56.01    28.5   56.01
#Mann= 3 , 0 , 0
   -16.9    .035       0       0    .035       0    13.5    .035       0
#XS Ineff= 2 , 0
               0   58.41    13.5           57.61
Permanent Ineff=
       F       F
Bank Sta=0,13.5
XS Rating Curve= 0
Exp/Cntr=.3,.1

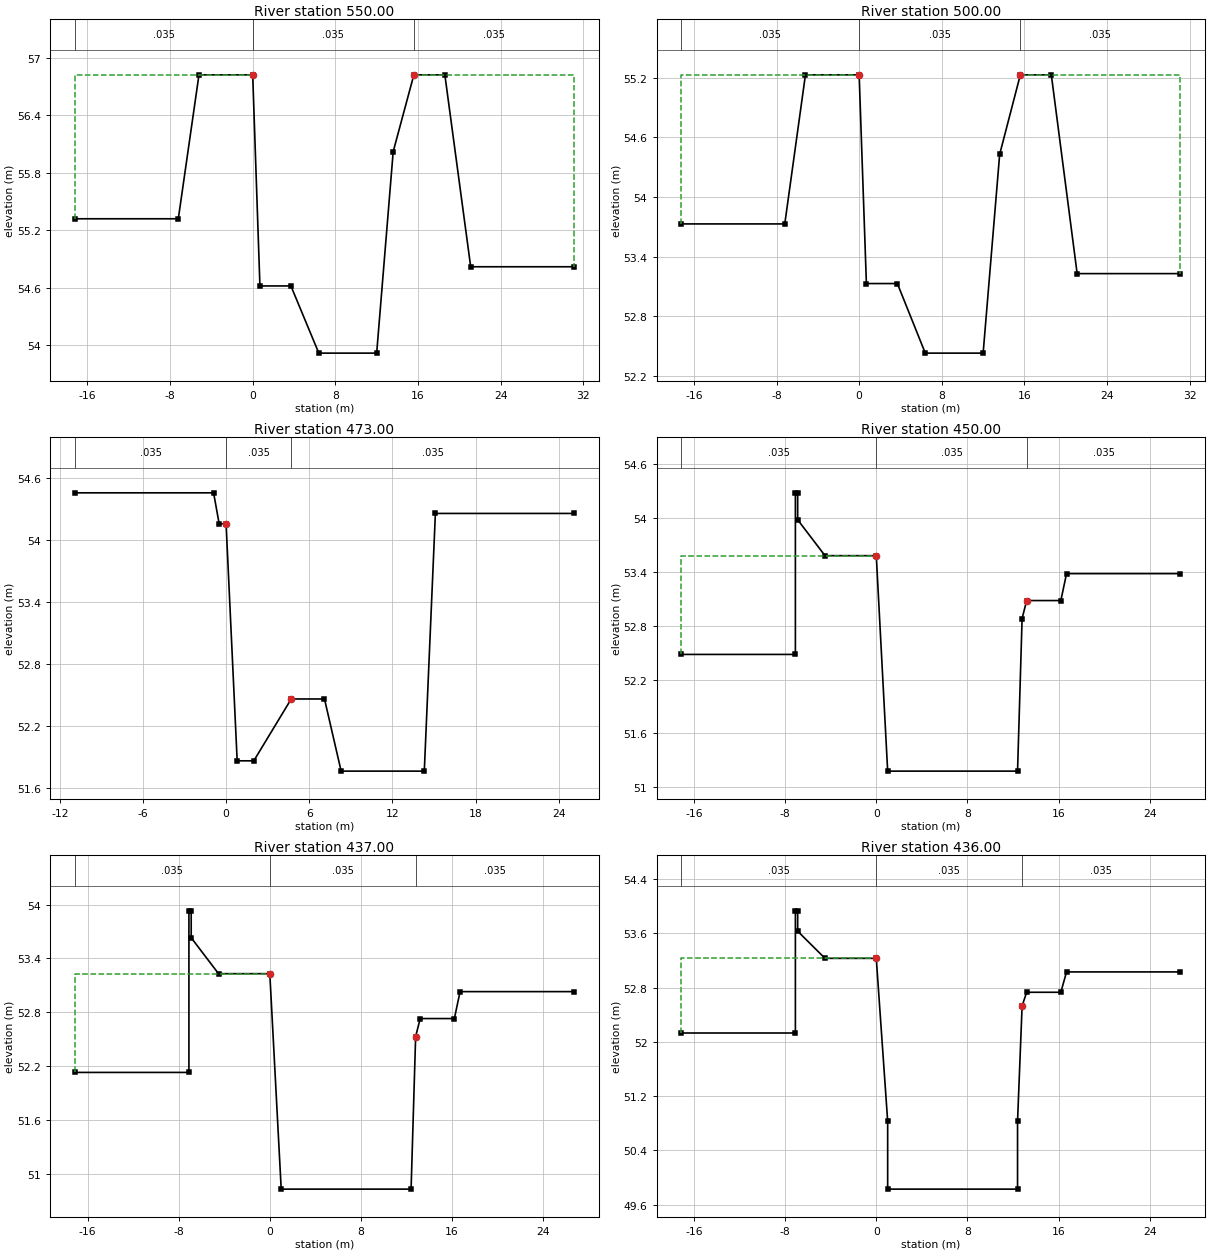
Type RM Length L Ch R = 1 ,550.00  ,50,50,50
BEGIN DESCRIPTION:
11
END DESCRIPTION:
#Sta/Elev= 13
   -17.2   55.32    -7.2   55.32    -5.2   56.82       0   56.82      .7   54.62
     3.7   54.62     6.4   53.92      12   53.92    13.6   56.02    15.6   56.82
    18.6   56.82    21.1   54.82    31.1   54.82
#Mann= 3 , 0 , 0
   -17.2    .035       0       0    .035       0    15.6    .035       0
#XS Ineff= 2 , 0
               0   56.82    15.6           56.82
Permanent Ineff=
       F       F
Bank Sta=0,15.6
XS Rating Curve= 0
Exp/Cntr=.3,.1

Type RM Length L Ch R = 1 ,500.00  ,27,27,27
BEGIN DESCRIPTION:
10
END DESCRIPTION:
#Sta/Elev= 13
   -17.2   53.73    -7.2   53.73    -5.2   55.23       0   55.23      .7   53.13
     3.7   53.13     6.4   52.43      12   52.43    13.6   54.43    15.6   55.23
    18.6   55.23    21.1   53.23    31.1   53.23
#Mann= 3 , 0 , 0
   -17.2    .035       0       0    .035       0    15.6    .035       0
#XS Ineff= 2 , 0
               0   55.23    15.6           55.23
Permanent Ineff=
       F       F
Bank Sta=0,15.6
XS Rating Curve= 0
Exp/Cntr=.3,.1

Type RM Length L Ch R = 1 ,473.00  ,23,23,23
BEGIN DESCRIPTION:
9.023
END DESCRIPTION:
#Sta/Elev= 12
   -10.9   54.46     -.9   54.46     -.5   54.16       0   54.16      .8   51.86
       2   51.86     4.7   52.46     7.1   52.46     8.3   51.76    14.3   51.76
    15.1   54.26    25.1   54.26
#Mann= 3 , 0 , 0
   -10.9    .035       0       0    .035       0     4.7    .035       0
#XS Ineff= 2 , 0
               0   54.16     4.7           52.46
Permanent Ineff=
       F       F
Bank Sta=0,4.7
XS Rating Curve= 0
Exp/Cntr=.3,.1

Type RM Length L Ch R = 1 ,450.00  ,13,13,13
BEGIN DESCRIPTION:
9
END DESCRIPTION:
#Sta/Elev= 14
   -17.1   52.48    -7.1   52.48    -7.1   54.28    -6.9   54.28    -6.9   53.98
    -4.5   53.58       0   53.58       1   51.18    12.4   51.18    12.8   52.88
    13.2   53.08    16.2   53.08    16.7   53.38    26.7   53.38
#Mann= 3 , 0 , 0
   -17.1    .035       0       0    .035       0    13.2    .035       0
#XS Ineff= 2 , 0
               0   53.58    13.2           53.08
Permanent Ineff=
       F       F
Bank Sta=0,13.2
XS Rating Curve= 0
Exp/Cntr=.3,.1

Type RM Length L Ch R = 1 ,437.00  ,1,1,1
BEGIN DESCRIPTION:
8.037
END DESCRIPTION:
#Sta/Elev= 14
   -17.1   52.13    -7.1   52.13    -7.1   53.93    -6.9   53.93    -6.9   53.63
    -4.5   53.23       0   53.23       1   50.83    12.4   50.83    12.8   52.53
    13.2   52.73    16.2   52.73    16.7   53.03    26.7   53.03
#Mann= 3 , 0 , 0
   -17.1    .035       0       0    .035       0    12.8    .035       0
#XS Ineff= 2 , 0
               0   53.23    12.8           52.53
Permanent Ineff=
       F       F
Bank Sta=0,12.8
XS Rating Curve= 0
Exp/Cntr=.3,.1

Type RM Length L Ch R = 1 ,436.00  ,36,36,36
BEGIN DESCRIPTION:
8.036
END DESCRIPTION:
#Sta/Elev= 16
   -17.1   52.13    -7.1   52.13    -7.1   53.93    -6.9   53.93    -6.9   53.63
    -4.5   53.23       0   53.23       1   50.83       1   49.83    12.4   49.83
    12.4   50.83    12.8   52.53    13.2   52.73    16.2   52.73    16.7   53.03
    26.7   53.03
#Mann= 3 , 0 , 0
   -17.1    .035       0       0    .035       0    12.8    .035       0
#XS Ineff= 2 , 0
               0   53.23    12.8           52.53
Permanent Ineff=
       F       F
Bank Sta=0,12.8
XS Rating Curve= 0
Exp/Cntr=.3,.1

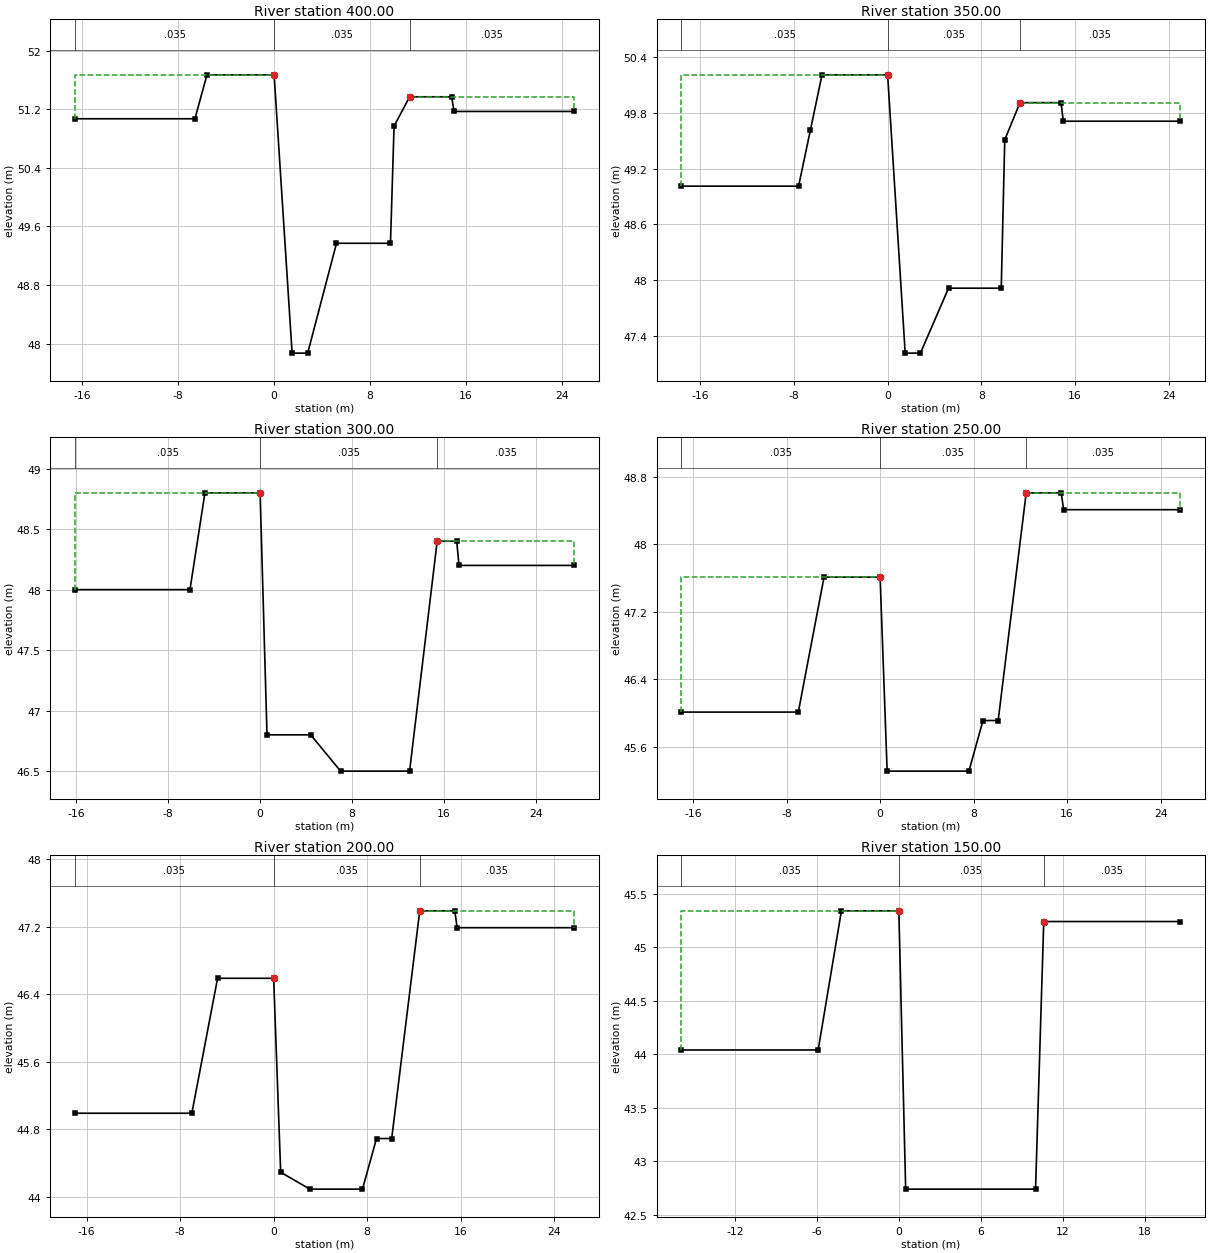
Type RM Length L Ch R = 1 ,400.00  ,50,50,50
BEGIN DESCRIPTION:
8
END DESCRIPTION:
#Sta/Elev= 13
   -16.6   51.07    -6.6   51.07    -5.6   51.67       0   51.67     1.5   47.87
     2.8   47.87     5.2   49.37     9.7   49.37      10   50.97    11.3   51.37
    14.8   51.37      15   51.17      25   51.17
#Mann= 3 , 0 , 0
   -16.6    .035       0       0    .035       0    11.3    .035       0
#XS Ineff= 2 , 0
               0   51.67    11.3           51.37
Permanent Ineff=
       F       F
Bank Sta=0,11.3
XS Rating Curve= 0
Exp/Cntr=.3,.1

Type RM Length L Ch R = 1 ,350.00  ,50,50,50
BEGIN DESCRIPTION:
7
END DESCRIPTION:
#Sta/Elev= 14
   -17.6   49.01    -7.6   49.01    -6.6   49.61    -5.6   50.21       0   50.21
     1.5   47.21     2.8   47.21     5.2   47.91     9.7   47.91      10   49.51
    11.3   49.91    14.8   49.91      15   49.71      25   49.71
#Mann= 3 , 0 , 0
   -17.6    .035       0       0    .035       0    11.3    .035       0
#XS Ineff= 2 , 0
               0   50.21    11.3           49.91
Permanent Ineff=
       F       F
Bank Sta=0,11.3
XS Rating Curve= 0
Exp/Cntr=.3,.1

Type RM Length L Ch R = 1 ,300.00  ,50,50,50
BEGIN DESCRIPTION:
6
END DESCRIPTION:
#Sta/Elev= 12
   -16.1      48    -6.1      48    -4.8    48.8       0    48.8      .6    46.8
     4.4    46.8       7    46.5      13    46.5    15.4    48.4    17.1    48.4
    17.3    48.2    27.3    48.2
#Mann= 3 , 0 , 0
   -16.1    .035       0       0    .035       0    15.4    .035       0
#XS Ineff= 2 , 0
               0    48.8    15.4            48.4
Permanent Ineff=
       F       F
Bank Sta=0,15.4
XS Rating Curve= 0
Exp/Cntr=.3,.1

Type RM Length L Ch R = 1 ,250.00  ,50,50,50
BEGIN DESCRIPTION:
5
END DESCRIPTION:
#Sta/Elev= 12
     -17   46.01      -7   46.01    -4.8   47.61       0   47.61      .6   45.31
     7.6   45.31     8.8   45.91    10.1   45.91    12.5   48.61    15.5   48.61
    15.7   48.41    25.7   48.41
#Mann= 3 , 0 , 0
     -17    .035       0       0    .035       0    12.5    .035       0
#XS Ineff= 2 , 0
               0   47.61    12.5           48.61
Permanent Ineff=
       F       F
Bank Sta=0,12.5
XS Rating Curve= 0
Exp/Cntr=.3,.1

Type RM Length L Ch R = 1 ,200.00  ,50,50,50
BEGIN DESCRIPTION:
4
END DESCRIPTION:
#Sta/Elev= 13
     -17   44.99      -7   44.99    -4.8   46.59       0   46.59      .6   44.29
     3.1   44.09     7.6   44.09     8.8   44.69    10.1   44.69    12.5   47.39
    15.5   47.39    15.7   47.19    25.7   47.19
#Mann= 3 , 0 , 0
     -17    .035       0       0    .035       0    12.5    .035       0
#XS Ineff= 2 , 0
       0       0   46.59    12.5       0   47.39
Permanent Ineff=
       F       F
Bank Sta=0,12.5
XS Rating Curve= 0
Exp/Cntr=.3,.1

Type RM Length L Ch R = 1 ,150.00  ,50,50,50
BEGIN DESCRIPTION:
3
END DESCRIPTION:
#Sta/Elev= 8
   -15.9   44.04    -5.9   44.04    -4.2   45.34       0   45.34      .5   42.74
      10   42.74    10.6   45.24    20.6   45.24
#Mann= 3 , 0 , 0
   -15.9    .035       0       0    .035       0    10.6    .035       0
#XS Ineff= 2 , 0
               0   45.34    10.6           45.24
Permanent Ineff=
       F       F
Bank Sta=0,10.6
XS Rating Curve= 0
Exp/Cntr=.3,.1

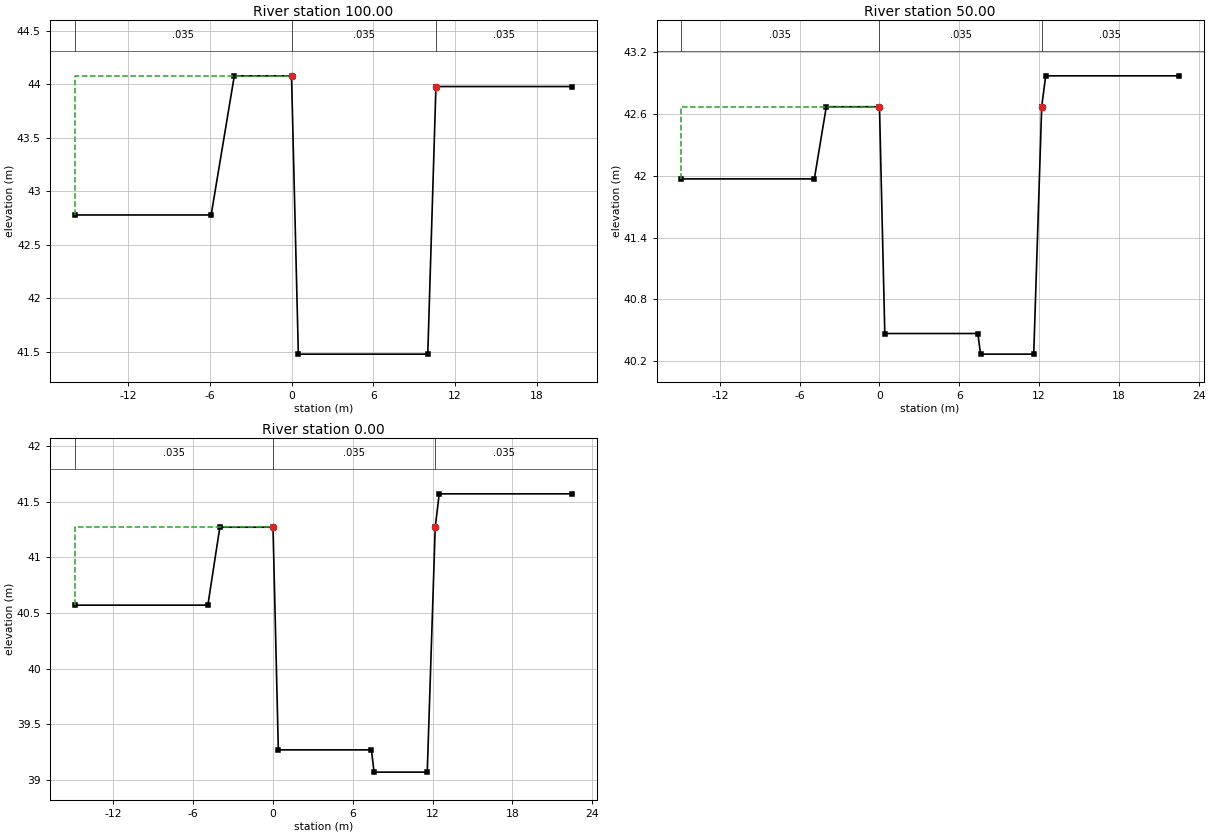
Type RM Length L Ch R = 1 ,100.00  ,50,50,50
BEGIN DESCRIPTION:
2
END DESCRIPTION:
#Sta/Elev= 8
   -15.9   42.78    -5.9   42.78    -4.2   44.08       0   44.08      .5   41.48
      10   41.48    10.6   43.98    20.6   43.98
#Mann= 3 , 0 , 0
   -15.9    .035       0       0    .035       0    10.6    .035       0
#XS Ineff= 2 , 0
               0   44.08    10.6           43.98
Permanent Ineff=
       F       F
Bank Sta=0,10.6
XS Rating Curve= 0
Exp/Cntr=.3,.1

Type RM Length L Ch R = 1 ,50.00   ,50,50,50
BEGIN DESCRIPTION:
1
END DESCRIPTION:
#Sta/Elev= 11
   -14.9   41.97    -4.9   41.97      -4   42.67       0   42.67      .4   40.47
     7.4   40.47     7.6   40.27    11.6   40.27    12.2   42.67    12.5   42.97
    22.5   42.97
#Mann= 3 , 0 , 0
   -14.9    .035       0       0    .035       0    12.2    .035       0
#XS Ineff= 2 , 0
               0   42.67    12.2           42.67
Permanent Ineff=
       F       F
Bank Sta=0,12.2
XS Rating Curve= 0
Exp/Cntr=.3,.1

Type RM Length L Ch R = 1 ,0.00    ,0,0,0
BEGIN DESCRIPTION:
0
END DESCRIPTION:
#Sta/Elev= 11
   -14.9   40.57    -4.9   40.57      -4   41.27       0   41.27      .4   39.27
     7.4   39.27     7.6   39.07    11.6   39.07    12.2   41.27    12.5   41.57
    22.5   41.57
#Mann= 3 , 0 , 0
   -14.9    .035       0       0    .035       0    12.2    .035       0
#XS Ineff= 2 , 0
               0   41.27    12.2           41.27
Permanent Ineff=
       F       F
Bank Sta=0,12.2
XS Rating Curve= 0
Exp/Cntr=.3,.1

Chan Stop Cuts=-1