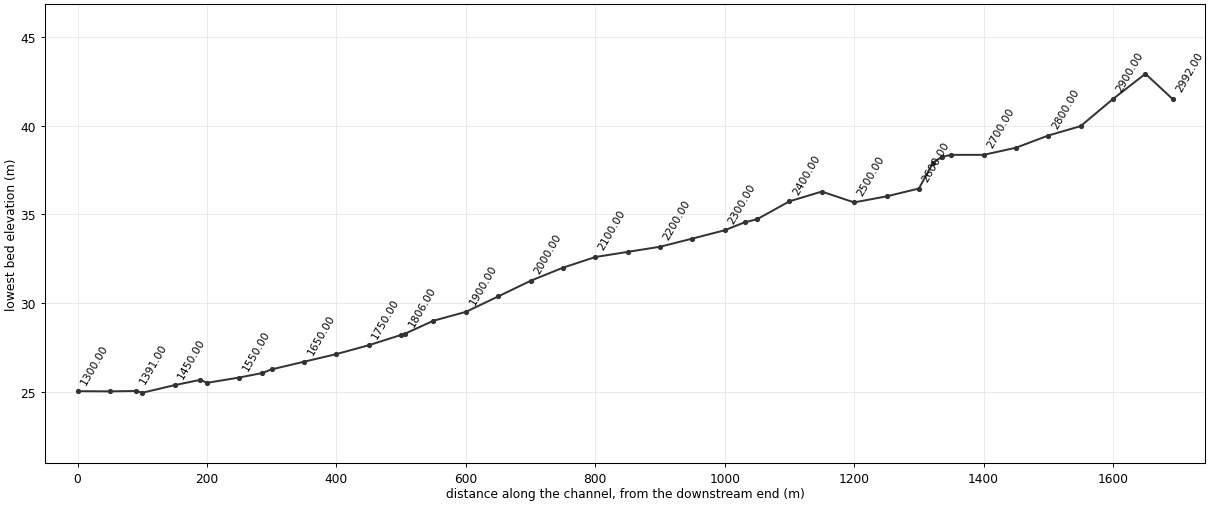
--- BONG.prj (project) ---

Proj Title=dongduk-chon
Current Plan=p01
Default Exp/Contr=.3,.1
SI Units
Geom File=g01
Flow File=f01
Plan File=p01
Y Axis Title=Elevation
X Axis Title(PF)=Main Channel Distance
X Axis Title(XS)=Station
BEGIN DESCRIPTION:
           BACK WATER COMPUTATION
      APPLICATION OF HEC-2 BY Samju Construction Engineering
      dongduk-chon: 10,20,30,50,80 yr
END DESCRIPTION:
DSS Export Rating Curves= 0
DSS Export Rating Curve Sorted= 0
DSS Export Volume Flow Curves= 0
DXF OffsetX= 0
DXF OffsetY= 0
DXF ScaleX= 1
DXF ScaleY= 10

--- BONG.p01 (plan) ---

Plan Title=Imported Plan 01
Version=Version 3.0.1  Mar 2001
Short Identifier=Imported Pla
Geom File=g01
Flow File=f01
Subcritical Flow
K Sum by GR= 0
Std Step Tol= 0.01
Critical Tol= 0.01
Num of Std Step Trials= 20
Max Error Tol= 0.3
Flow Tol Ratio= 0.001
Split Flow NTrial= 30
Split Flow Tol= 0.02
Split Flow Ratio= 0.02
Log Output Level= 0
Friction Slope Method= 1
Unsteady Friction Slope Method= 2
Parabolic Critical Depth
Global Vel Dist= 0 , 0 , 0
Global Log Level= 0
CheckData=True
Encroach Param=-1 ,0,0, 0
Computation Interval=1HOUR
Output Interval=1HOUR
Run HTab= 0
Run UNet= 0
Run PostProcess= 0
UNET Theta= 1
UNET ZTol= 0.02
UNET ZSATol= 0.1
UNET MxIter= 20
UNET MaxInSteps= 20
UNET DtIC= 0
UNET DtMin= 0
UNET MaxCRTS= 20
UNET WFStab= 2
UNET SFStab= 1
UNET WFX= 1
UNET SFX= 1
UNET Convert EG Bridges=-1
UNET Use Existing IB Tables=-1
Instantaneous Interval=1HOUR
Write IC File= 0
Write Velocity= 0
Write Detailed= 0

--- BONG.f01 (steady flow) ---

Flow Title=Imported Flow 01
Version=Version 3.0.1  Mar 2001
Number of Profiles= 5
Profile Names=10YR,20YR,30YR,50YR,80YR
River Rch & RM=RIVER-1,Reach-1         ,59.042
   28.99   31.95   33.69   35.87   37.88
River Rch & RM=RIVER-1,Reach-1         ,17
   35.41   39.04   41.17   43.84   46.31
River Rch & RM=BONGDUCK,BONGDUCK        ,2992.00
   28.99   31.95   33.69   35.87   37.88
River Rch & RM=BONGDUCK,BONGDUCK        ,850.00
   35.41   39.04   41.17   43.84   46.31
Boundary for River Rch & Prof#=BONGDUCK,BONGDUCK        , 1
Up Type= 0
Dn Type= 3
Dn Slope=.012
Boundary for River Rch & Prof#=BONGDUCK,BONGDUCK        , 2
Up Type= 0
Dn Type= 3
Dn Slope=.012
Boundary for River Rch & Prof#=BONGDUCK,BONGDUCK        , 3
Up Type= 0
Dn Type= 3
Dn Slope=.012
Boundary for River Rch & Prof#=BONGDUCK,BONGDUCK        , 4
Up Type= 0
Dn Type= 3
Dn Slope=.012
Boundary for River Rch & Prof#=BONGDUCK,BONGDUCK        , 5
Up Type= 0
Dn Type= 3
Dn Slope=.012
DSS Import GetInterval= 0
DSS Import GetPeak= 0
DSS Import FillOption= 0

--- BONG.g01 (geometry) ---

Geom Title=Imported Geom 01
Version=Version 3.0.1  Mar 2001

River Reach=BONGDUCK        ,BONGDUCK
Reach XY= 2
              .5             .95              .5             .05

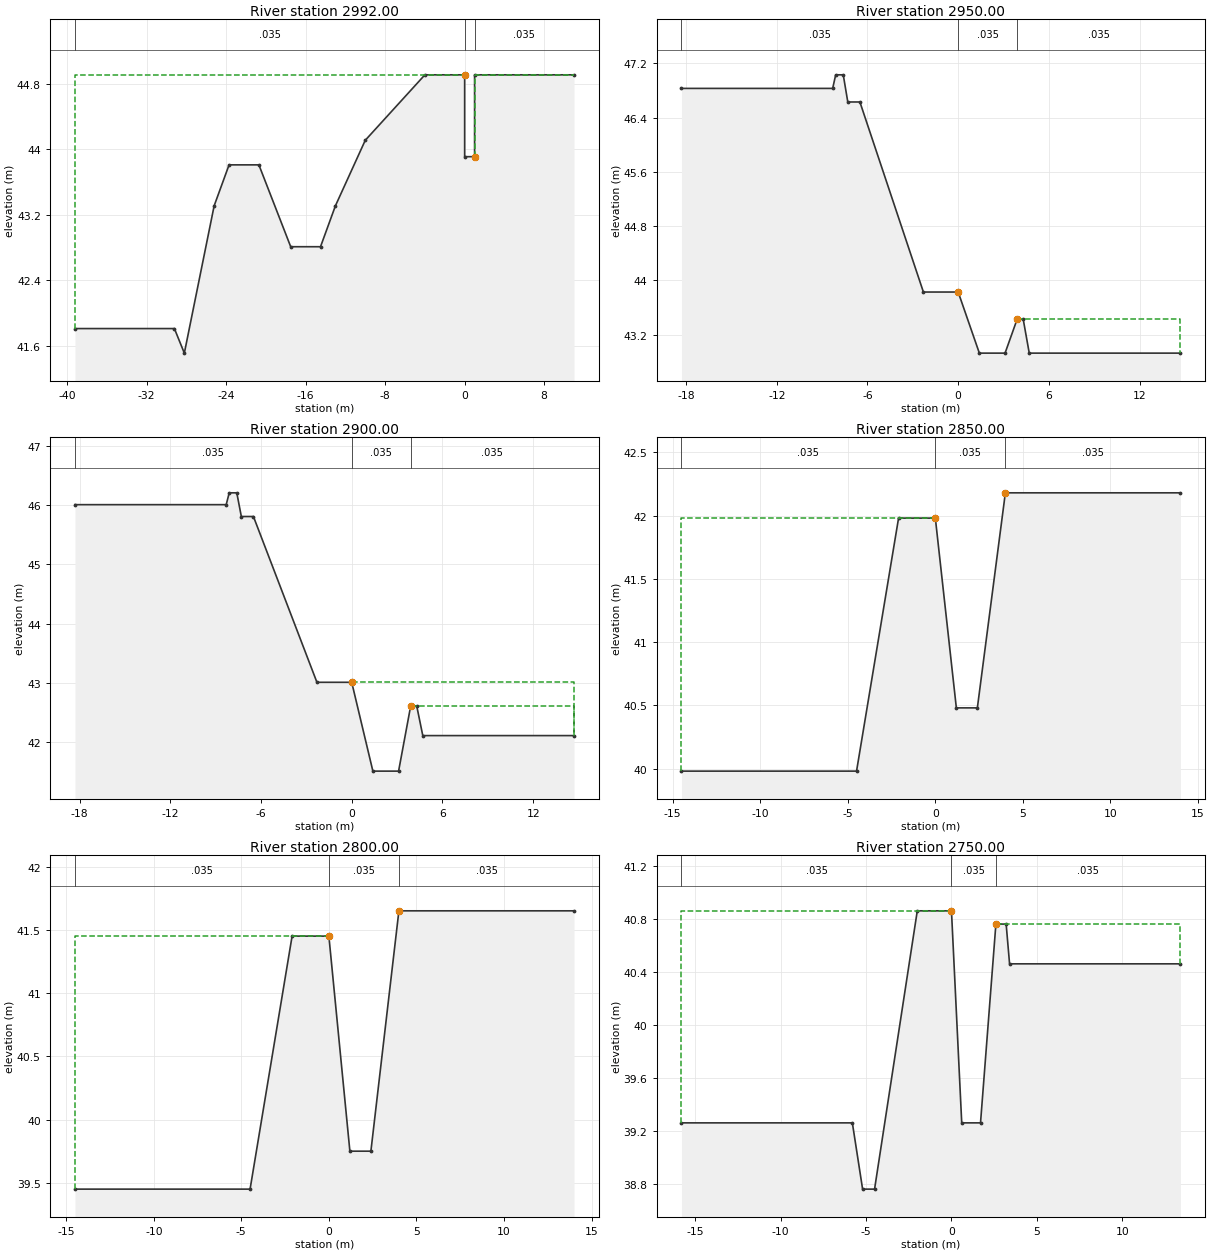
Type RM Length L Ch R = 1 ,2992.00 ,42,42,42
BEGIN DESCRIPTION:
59.042
END DESCRIPTION:
#Sta/Elev= 16
   -39.2   41.81   -29.2   41.81   -28.2   41.51   -25.2   43.31   -23.7   43.81
   -20.7   43.81   -17.5   42.81   -14.5   42.81     -13   43.31     -10   44.11
      -4   44.91       0   44.91       0   43.91       1   43.91       1   44.91
      11   44.91
#Mann= 3 , 0 , 0
   -39.2    .035       0       0    .035       0       1    .035       0
#XS Ineff= 2 , 0
               0   44.91       1           44.91
Permanent Ineff=
       F       F
Bank Sta=0,1
XS Rating Curve= 0
Exp/Cntr=.3,.1

Type RM Length L Ch R = 1 ,2950.00 ,50,50,50
BEGIN DESCRIPTION:
59
END DESCRIPTION:
#Sta/Elev= 14
   -18.3   46.83    -8.3   46.83    -8.1   47.03    -7.6   47.03    -7.3   46.63
    -6.5   46.63    -2.3   43.83       0   43.83     1.4   42.93     3.1   42.93
     3.9   43.43     4.3   43.43     4.7   42.93    14.7   42.93
#Mann= 3 , 0 , 0
   -18.3    .035       0       0    .035       0     3.9    .035       0
#XS Ineff= 2 , 0
               0   43.83     3.9           43.43
Permanent Ineff=
       F       F
Bank Sta=0,3.9
XS Rating Curve= 0
Exp/Cntr=.3,.1

Type RM Length L Ch R = 1 ,2900.00 ,50,50,50
BEGIN DESCRIPTION:
58
END DESCRIPTION:
#Sta/Elev= 14
   -18.3   46.01    -8.3   46.01    -8.1   46.21    -7.6   46.21    -7.3   45.81
    -6.5   45.81    -2.3   43.01       0   43.01     1.4   41.51     3.1   41.51
     3.9   42.61     4.3   42.61     4.7   42.11    14.7   42.11
#Mann= 3 , 0 , 0
   -18.3    .035       0       0    .035       0     3.9    .035       0
#XS Ineff= 2 , 0
       0       0   43.01     3.9       0   42.61
Permanent Ineff=
       F       F
Bank Sta=0,3.9
XS Rating Curve= 0
Exp/Cntr=.3,.1

Type RM Length L Ch R = 1 ,2850.00 ,50,50,50
BEGIN DESCRIPTION:
57
END DESCRIPTION:
#Sta/Elev= 8
   -14.5   39.98    -4.5   39.98    -2.1   41.98       0   41.98     1.2   40.48
     2.4   40.48       4   42.18      14   42.18
#Mann= 3 , 0 , 0
   -14.5    .035       0       0    .035       0       4    .035       0
#XS Ineff= 2 , 0
               0   41.98       4           42.18
Permanent Ineff=
       F       F
Bank Sta=0,4
XS Rating Curve= 0
Exp/Cntr=.3,.1

Type RM Length L Ch R = 1 ,2800.00 ,50,50,50
BEGIN DESCRIPTION:
56
END DESCRIPTION:
#Sta/Elev= 8
   -14.5   39.45    -4.5   39.45    -2.1   41.45       0   41.45     1.2   39.75
     2.4   39.75       4   41.65      14   41.65
#Mann= 3 , 0 , 0
   -14.5    .035       0       0    .035       0       4    .035       0
#XS Ineff= 2 , 0
               0   41.45       4           41.65
Permanent Ineff=
       F       F
Bank Sta=0,4
XS Rating Curve= 0
Exp/Cntr=.3,.1

Type RM Length L Ch R = 1 ,2750.00 ,50,50,50
BEGIN DESCRIPTION:
55
END DESCRIPTION:
#Sta/Elev= 12
   -15.8   39.26    -5.8   39.26    -5.2   38.76    -4.5   38.76      -2   40.86
       0   40.86      .6   39.26     1.7   39.26     2.6   40.76     3.2   40.76
     3.4   40.46    13.4   40.46
#Mann= 3 , 0 , 0
   -15.8    .035       0       0    .035       0     2.6    .035       0
#XS Ineff= 2 , 0
               0   40.86     2.6           40.76
Permanent Ineff=
       F       F
Bank Sta=0,2.6
XS Rating Curve= 0
Exp/Cntr=.3,.1

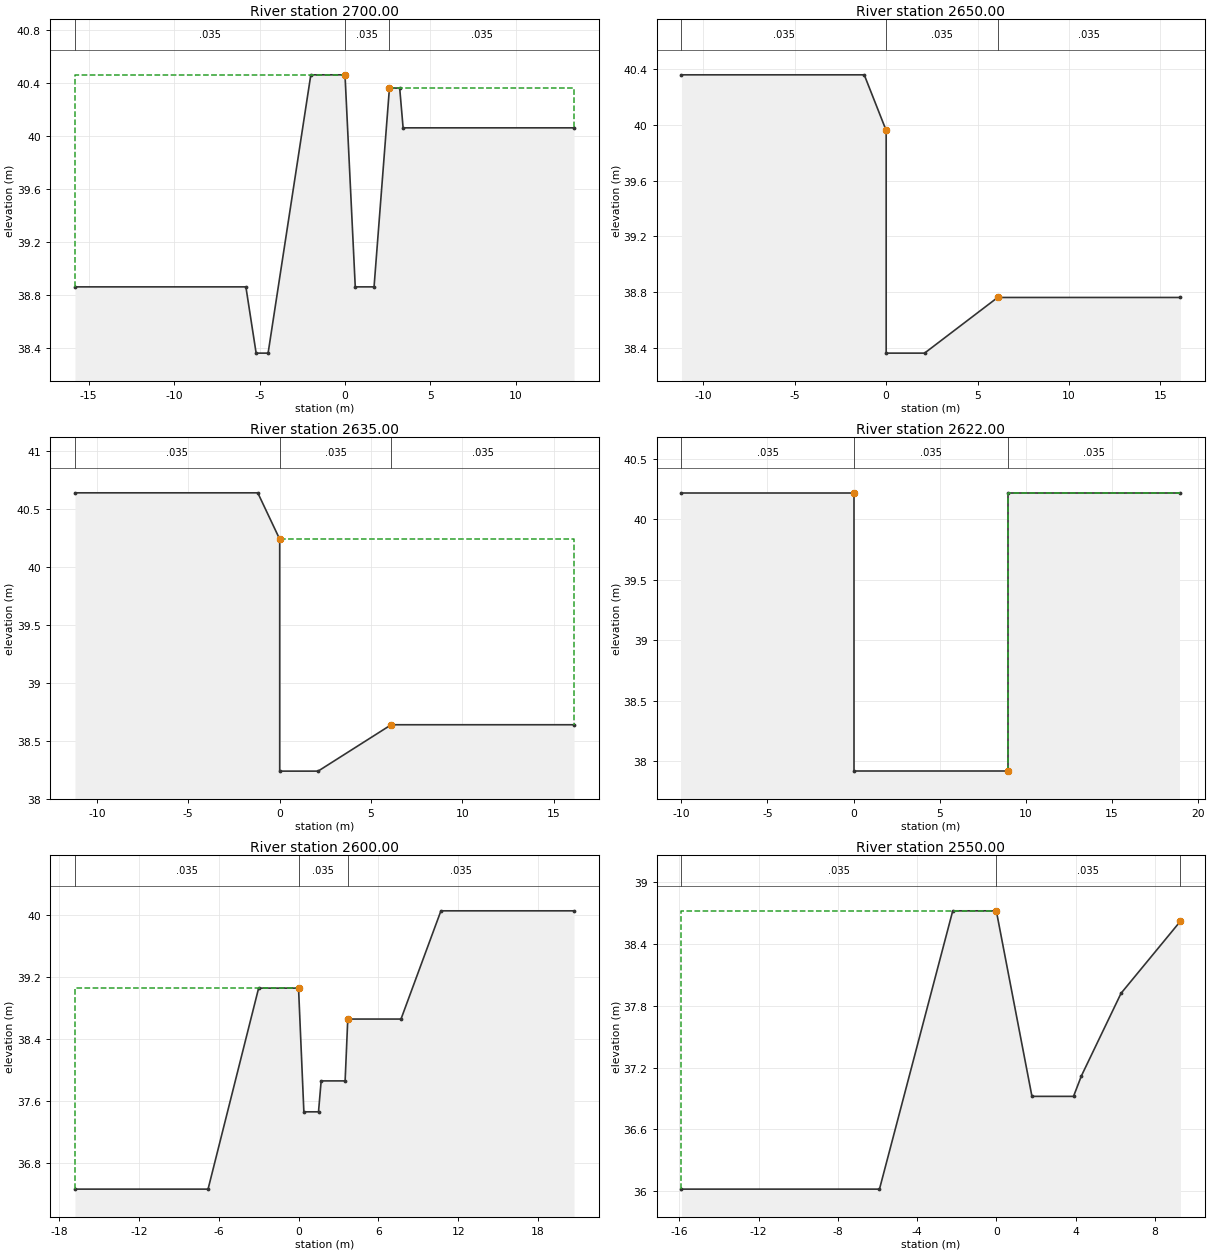
Type RM Length L Ch R = 1 ,2700.00 ,50,50,50
BEGIN DESCRIPTION:
54
END DESCRIPTION:
#Sta/Elev= 12
   -15.8   38.86    -5.8   38.86    -5.2   38.36    -4.5   38.36      -2   40.46
       0   40.46      .6   38.86     1.7   38.86     2.6   40.36     3.2   40.36
     3.4   40.06    13.4   40.06
#Mann= 3 , 0 , 0
   -15.8    .035       0       0    .035       0     2.6    .035       0
#XS Ineff= 2 , 0
               0   40.46     2.6           40.36
Permanent Ineff=
       F       F
Bank Sta=0,2.6
XS Rating Curve= 0
Exp/Cntr=.3,.1

Type RM Length L Ch R = 1 ,2650.00 ,15,15,15
BEGIN DESCRIPTION:
53
END DESCRIPTION:
#Sta/Elev= 7
   -11.2   40.36    -1.2   40.36       0   39.96       0   38.36     2.1   38.36
     6.1   38.76    16.1   38.76
#Mann= 3 , 0 , 0
   -11.2    .035       0       0    .035       0     6.1    .035       0
#XS Ineff= 2 , 0
               0   39.96     6.1           38.76
Permanent Ineff=
       F       F
Bank Sta=0,6.1
XS Rating Curve= 0
Exp/Cntr=.3,.1

Type RM Length L Ch R = 1 ,2635.00 ,13,13,13
BEGIN DESCRIPTION:
52.035
END DESCRIPTION:
#Sta/Elev= 7
   -11.2   40.64    -1.2   40.64       0   40.24       0   38.24     2.1   38.24
     6.1   38.64    16.1   38.64
#Mann= 3 , 0 , 0
   -11.2    .035       0       0    .035       0     6.1    .035       0
#XS Ineff= 2 , 0
       0       0   40.24     6.1       0   38.64
Permanent Ineff=
       F       F
Bank Sta=0,6.1
XS Rating Curve= 0
Exp/Cntr=.3,.1

Type RM Length L Ch R = 1 ,2622.00 ,22,22,22
BEGIN DESCRIPTION:
52.022
END DESCRIPTION:
#Sta/Elev= 6
     -10   40.22       0   40.22       0   37.92       9   37.92       9   40.22
      19   40.22
#Mann= 3 , 0 , 0
     -10    .035       0       0    .035       0       9    .035       0
#XS Ineff= 2 , 0
               0   40.22       9           40.22
Permanent Ineff=
       F       F
Bank Sta=0,9
XS Rating Curve= 0
Exp/Cntr=.3,.1

Type RM Length L Ch R = 1 ,2600.00 ,50,50,50
BEGIN DESCRIPTION:
52
END DESCRIPTION:
#Sta/Elev= 12
   -16.8   36.46    -6.8   36.46      -3   39.06       0   39.06      .4   37.46
     1.5   37.46     1.7   37.86     3.5   37.86     3.7   38.66     7.7   38.66
    10.7   40.06    20.7   40.06
#Mann= 3 , 0 , 0
   -16.8    .035       0       0    .035       0     3.7    .035       0
#XS Ineff= 2 , 0
               0   39.06     3.7           38.66
Permanent Ineff=
       F       F
Bank Sta=0,3.7
XS Rating Curve= 0
Exp/Cntr=.3,.1

Type RM Length L Ch R = 1 ,2550.00 ,50,50,50
BEGIN DESCRIPTION:
51
END DESCRIPTION:
#Sta/Elev= 9
   -15.9   36.02    -5.9   36.02    -2.2   38.72       0   38.72     1.8   36.92
     3.9   36.92     4.3   37.12     6.3   37.92     9.3   38.62
#Mann= 3 , 0 , 0
   -15.9    .035       0       0    .035       0     9.3    .035       0
#XS Ineff= 2 , 0
               0   38.72     9.3           38.62
Permanent Ineff=
       F       F
Bank Sta=0,9.3
XS Rating Curve= 0
Exp/Cntr=.3,.1

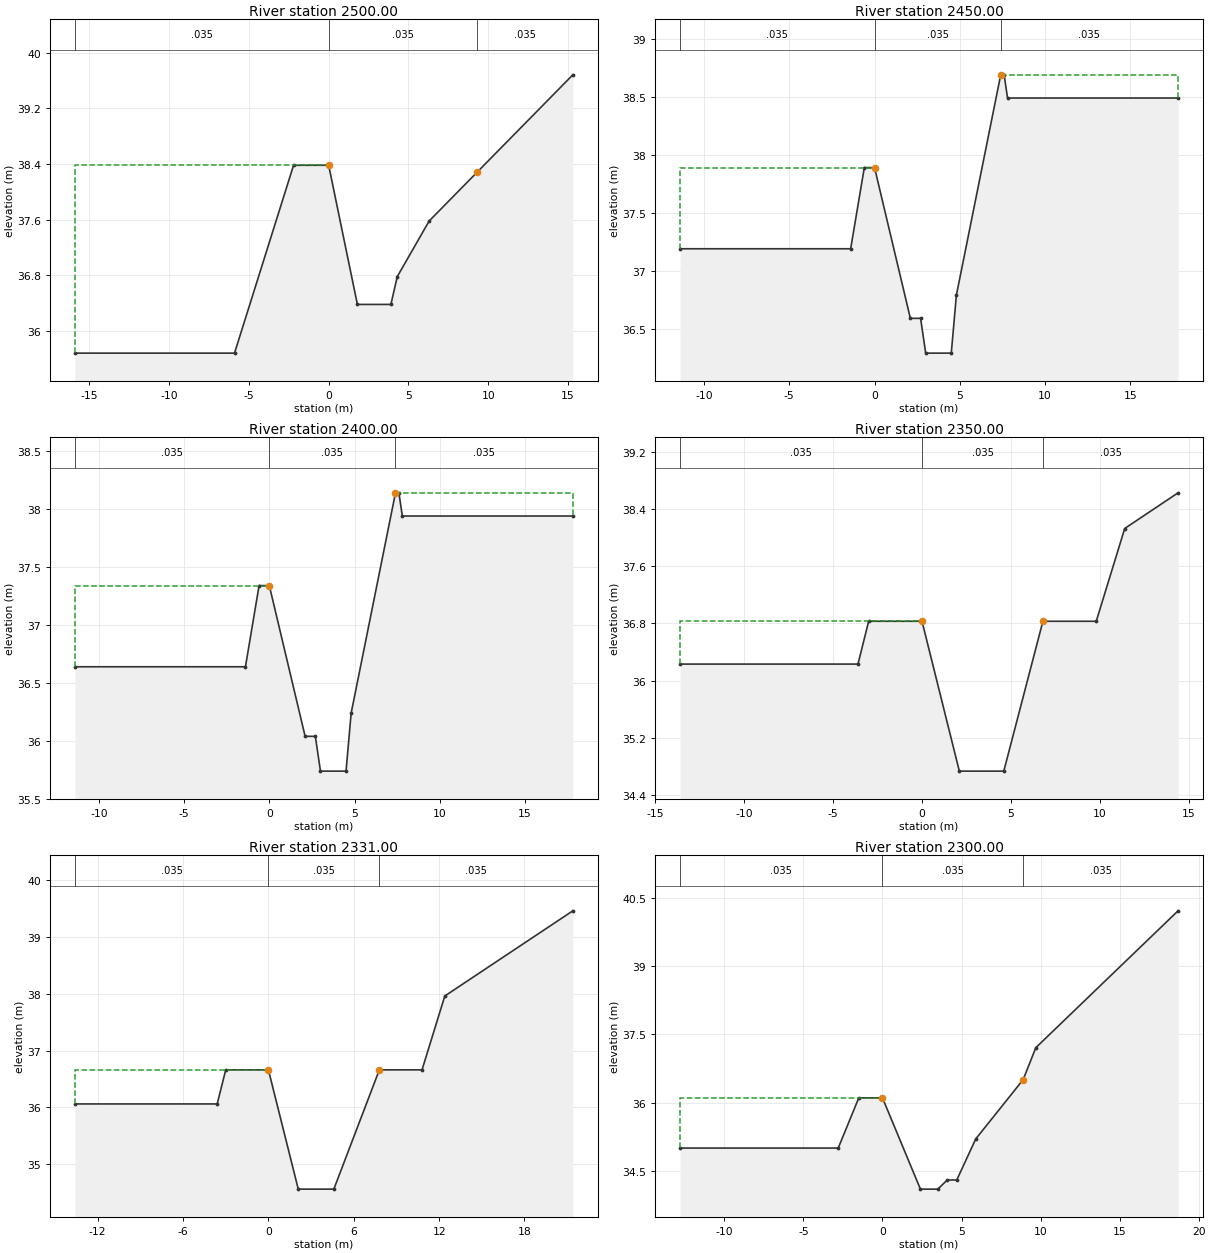
Type RM Length L Ch R = 1 ,2500.00 ,50,50,50
BEGIN DESCRIPTION:
50
END DESCRIPTION:
#Sta/Elev= 10
   -15.9   35.68    -5.9   35.68    -2.2   38.38       0   38.38     1.8   36.38
     3.9   36.38     4.3   36.78     6.3   37.58     9.3   38.28    15.3   39.68
#Mann= 3 , 0 , 0
   -15.9    .035       0       0    .035       0     9.3    .035       0
#XS Ineff= 2 , 0
               0   38.38     9.3           38.28
Permanent Ineff=
       F       F
Bank Sta=0,9.3
XS Rating Curve= 0
Exp/Cntr=.3,.1

Type RM Length L Ch R = 1 ,2450.00 ,50,50,50
BEGIN DESCRIPTION:
49
END DESCRIPTION:
#Sta/Elev= 13
   -11.4   37.19    -1.4   37.19     -.6   37.89       0   37.89     2.1   36.59
     2.7   36.59       3   36.29     4.5   36.29     4.8   36.79     7.4   38.69
     7.6   38.69     7.8   38.49    17.8   38.49
#Mann= 3 , 0 , 0
   -11.4    .035       0       0    .035       0     7.4    .035       0
#XS Ineff= 2 , 0
               0   37.89     7.4           38.69
Permanent Ineff=
       F       F
Bank Sta=0,7.4
XS Rating Curve= 0
Exp/Cntr=.3,.1

Type RM Length L Ch R = 1 ,2400.00 ,50,50,50
BEGIN DESCRIPTION:
48
END DESCRIPTION:
#Sta/Elev= 13
   -11.4   36.64    -1.4   36.64     -.6   37.34       0   37.34     2.1   36.04
     2.7   36.04       3   35.74     4.5   35.74     4.8   36.24     7.4   38.14
     7.6   38.14     7.8   37.94    17.8   37.94
#Mann= 3 , 0 , 0
   -11.4    .035       0       0    .035       0     7.4    .035       0
#XS Ineff= 2 , 0
               0   37.34     7.4           38.14
Permanent Ineff=
       F       F
Bank Sta=0,7.4
XS Rating Curve= 0
Exp/Cntr=.3,.1

Type RM Length L Ch R = 1 ,2350.00 ,19,19,19
BEGIN DESCRIPTION:
47
END DESCRIPTION:
#Sta/Elev= 10
   -13.6   36.23    -3.6   36.23      -3   36.83       0   36.83     2.1   34.73
     4.6   34.73     6.8   36.83     9.8   36.83    11.4   38.13    14.4   38.63
#Mann= 3 , 0 , 0
   -13.6    .035       0       0    .035       0     6.8    .035       0
#XS Ineff= 2 , 0
               0   36.83     6.8           36.83
Permanent Ineff=
       F       F
Bank Sta=0,6.8
XS Rating Curve= 0
Exp/Cntr=.3,.1

Type RM Length L Ch R = 1 ,2331.00 ,31,31,31
BEGIN DESCRIPTION:
46.031
END DESCRIPTION:
#Sta/Elev= 10
   -13.6   36.06    -3.6   36.06      -3   36.66       0   36.66     2.1   34.56
     4.6   34.56     7.8   36.66    10.8   36.66    12.4   37.96    21.4   39.46
#Mann= 3 , 0 , 0
   -13.6    .035       0       0    .035       0     7.8    .035       0
#XS Ineff= 2 , 0
               0   36.66     7.8           36.66
Permanent Ineff=
       F       F
Bank Sta=0,7.8
XS Rating Curve= 0
Exp/Cntr=.3,.1

Type RM Length L Ch R = 1 ,2300.00 ,50,50,50
BEGIN DESCRIPTION:
46
END DESCRIPTION:
#Sta/Elev= 12
   -12.8   35.01    -2.8   35.01    -1.5   36.11       0   36.11     2.4   34.11
     3.5   34.11     4.1   34.31     4.7   34.31     5.9   35.21     8.9   36.51
     9.7   37.21    18.7   40.21
#Mann= 3 , 0 , 0
   -12.8    .035       0       0    .035       0     8.9    .035       0
#XS Ineff= 2 , 0
               0   36.11     8.9           36.51
Permanent Ineff=
       F       F
Bank Sta=0,8.9
XS Rating Curve= 0
Exp/Cntr=.3,.1

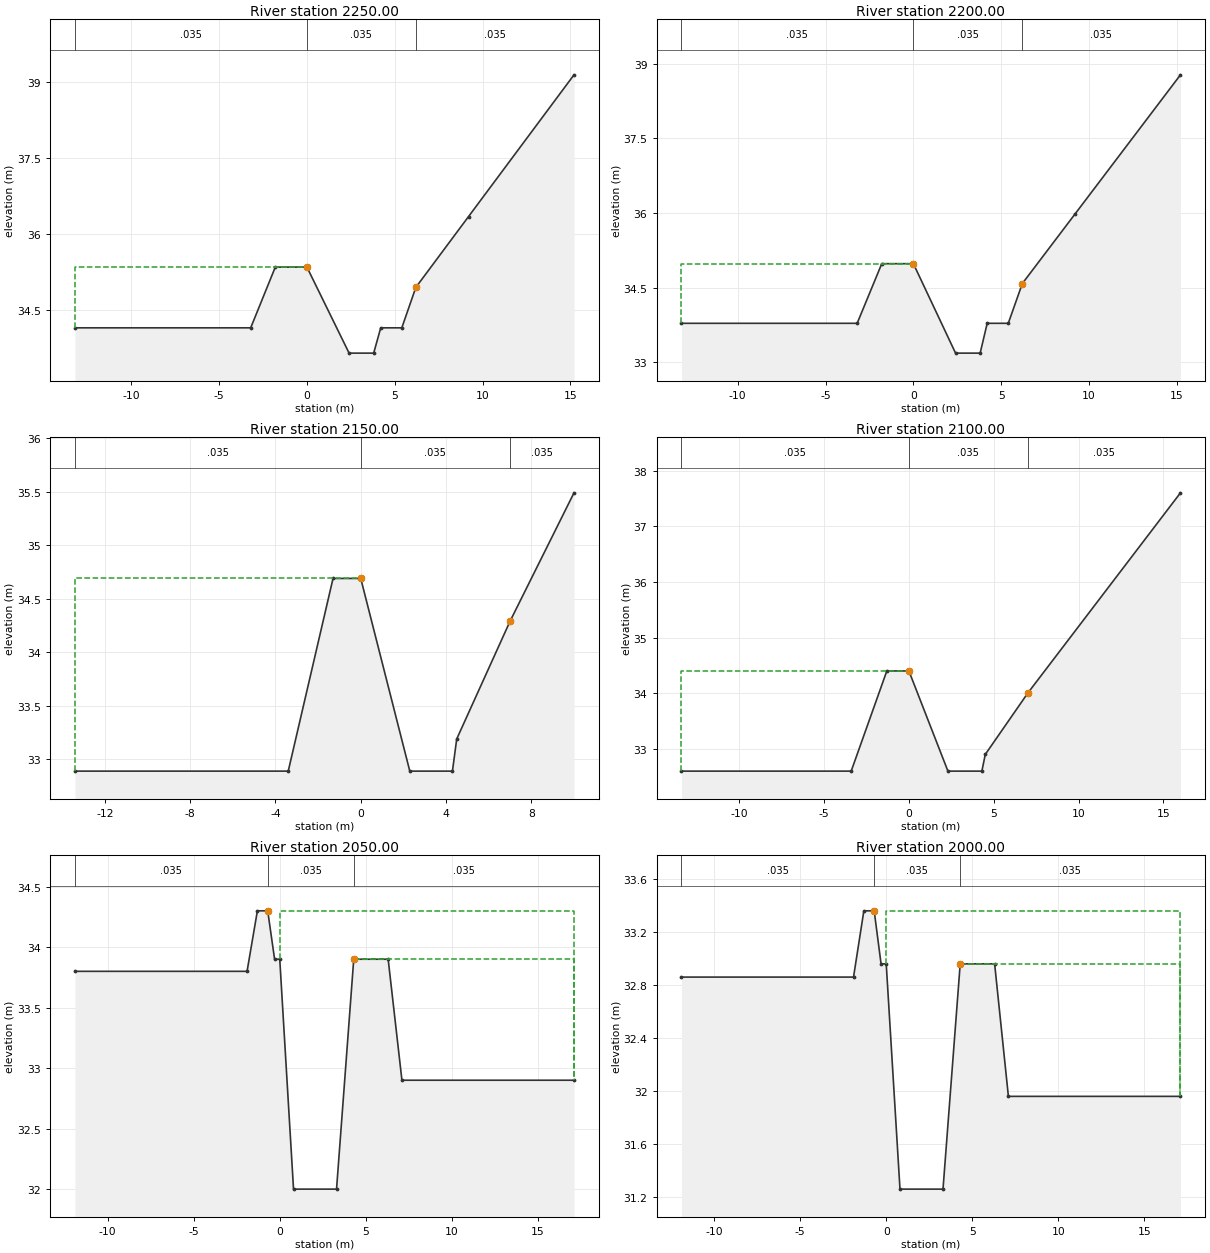
Type RM Length L Ch R = 1 ,2250.00 ,50,50,50
BEGIN DESCRIPTION:
45
END DESCRIPTION:
#Sta/Elev= 11
   -13.2   34.14    -3.2   34.14    -1.8   35.34       0   35.34     2.4   33.64
     3.8   33.64     4.2   34.14     5.4   34.14     6.2   34.94     9.2   36.34
    15.2   39.14
#Mann= 3 , 0 , 0
   -13.2    .035       0       0    .035       0     6.2    .035       0
#XS Ineff= 2 , 0
               0   35.34     6.2           34.94
Permanent Ineff=
       F       F
Bank Sta=0,6.2
XS Rating Curve= 0
Exp/Cntr=.3,.1

Type RM Length L Ch R = 1 ,2200.00 ,50,50,50
BEGIN DESCRIPTION:
44
END DESCRIPTION:
#Sta/Elev= 11
   -13.2   33.78    -3.2   33.78    -1.8   34.98       0   34.98     2.4   33.18
     3.8   33.18     4.2   33.78     5.4   33.78     6.2   34.58     9.2   35.98
    15.2   38.78
#Mann= 3 , 0 , 0
   -13.2    .035       0       0    .035       0     6.2    .035       0
#XS Ineff= 2 , 0
               0   34.98     6.2           34.58
Permanent Ineff=
       F       F
Bank Sta=0,6.2
XS Rating Curve= 0
Exp/Cntr=.3,.1

Type RM Length L Ch R = 1 ,2150.00 ,50,50,50
BEGIN DESCRIPTION:
43
END DESCRIPTION:
#Sta/Elev= 9
   -13.4   32.89    -3.4   32.89    -1.3   34.69       0   34.69     2.3   32.89
     4.3   32.89     4.5   33.19       7   34.29      10   35.49
#Mann= 3 , 0 , 0
   -13.4    .035       0       0    .035       0       7    .035       0
#XS Ineff= 2 , 0
               0   34.69       7           34.29
Permanent Ineff=
       F       F
Bank Sta=0,7
XS Rating Curve= 0
Exp/Cntr=.3,.1

Type RM Length L Ch R = 1 ,2100.00 ,50,50,50
BEGIN DESCRIPTION:
42
END DESCRIPTION:
#Sta/Elev= 9
   -13.4    32.6    -3.4    32.6    -1.3    34.4       0    34.4     2.3    32.6
     4.3    32.6     4.5    32.9       7      34      16    37.6
#Mann= 3 , 0 , 0
   -13.4    .035       0       0    .035       0       7    .035       0
#XS Ineff= 2 , 0
               0    34.4       7              34
Permanent Ineff=
       F       F
Bank Sta=0,7
XS Rating Curve= 0
Exp/Cntr=.3,.1

Type RM Length L Ch R = 1 ,2050.00 ,50,50,50
BEGIN DESCRIPTION:
41
END DESCRIPTION:
#Sta/Elev= 12
   -11.9    33.8    -1.9    33.8    -1.3    34.3     -.7    34.3     -.3    33.9
       0    33.9      .8      32     3.3      32     4.3    33.9     6.3    33.9
     7.1    32.9    17.1    32.9
#Mann= 3 , 0 , 0
   -11.9    .035       0     -.7    .035       0     4.3    .035       0
#XS Ineff= 2 , 0
       0     -.7    34.3     4.3       0    33.9
Permanent Ineff=
       F       F
Bank Sta=-.7,4.3
XS Rating Curve= 0
Exp/Cntr=.3,.1

Type RM Length L Ch R = 1 ,2000.00 ,50,50,50
BEGIN DESCRIPTION:
40
END DESCRIPTION:
#Sta/Elev= 12
   -11.9   32.86    -1.9   32.86    -1.3   33.36     -.7   33.36     -.3   32.96
       0   32.96      .8   31.26     3.3   31.26     4.3   32.96     6.3   32.96
     7.1   31.96    17.1   31.96
#Mann= 3 , 0 , 0
   -11.9    .035       0     -.7    .035       0     4.3    .035       0
#XS Ineff= 2 , 0
       0     -.7   33.36     4.3       0   32.96
Permanent Ineff=
       F       F
Bank Sta=-.7,4.3
XS Rating Curve= 0
Exp/Cntr=.3,.1

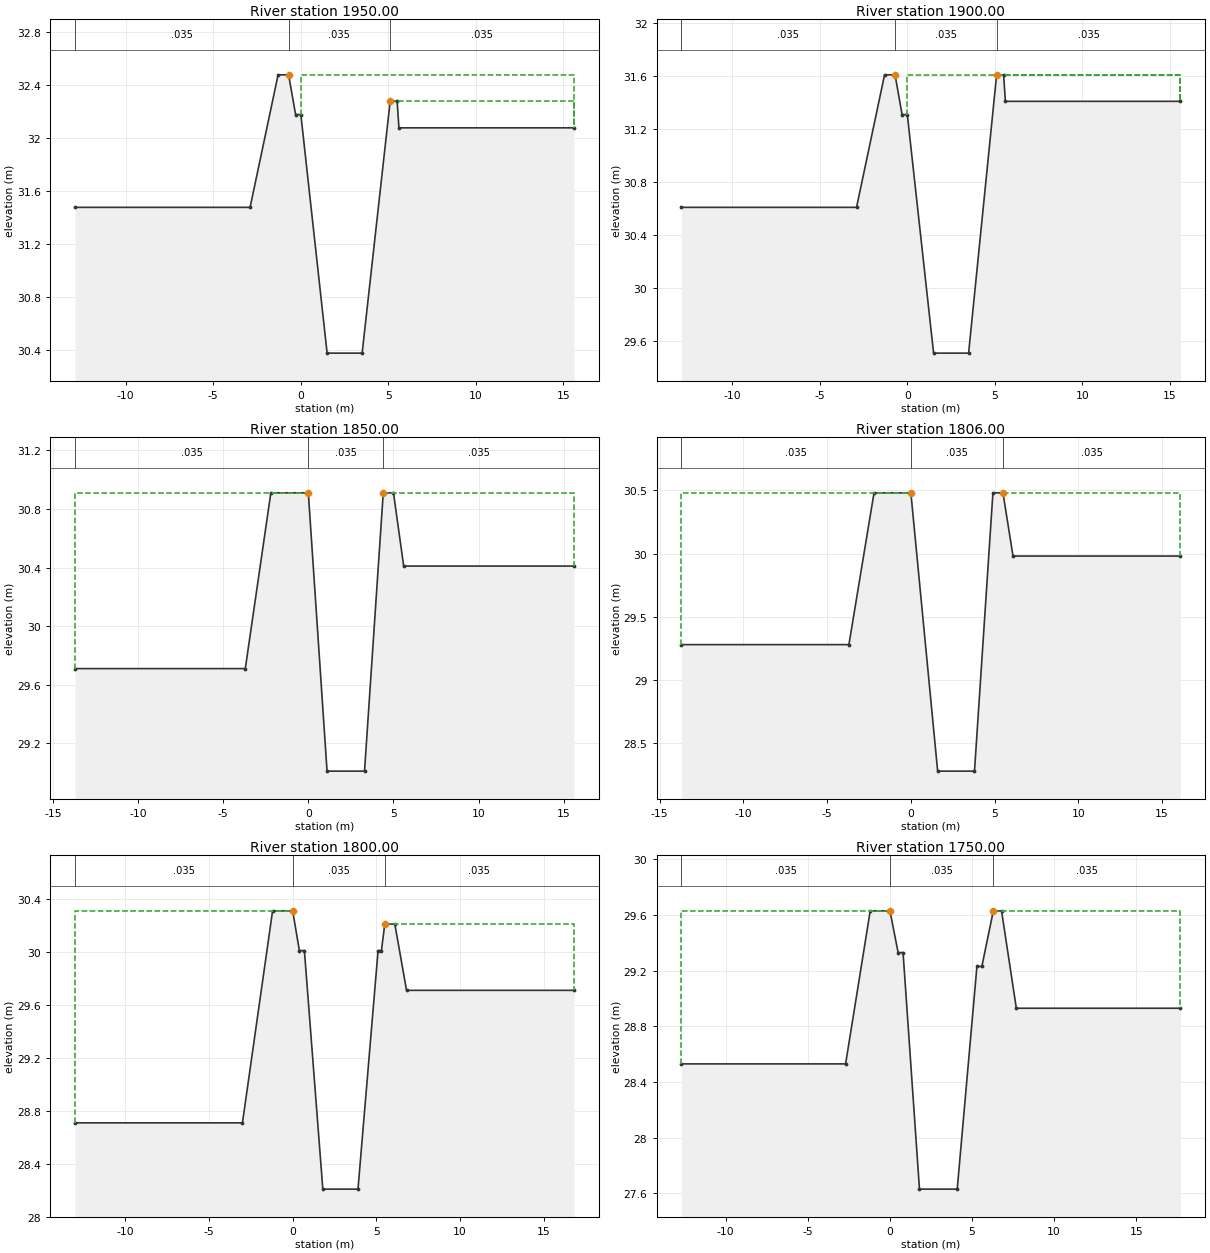
Type RM Length L Ch R = 1 ,1950.00 ,50,50,50
BEGIN DESCRIPTION:
39
END DESCRIPTION:
#Sta/Elev= 12
   -12.9   31.48    -2.9   31.48    -1.3   32.48     -.7   32.48     -.3   32.18
       0   32.18     1.5   30.38     3.5   30.38     5.1   32.28     5.5   32.28
     5.6   32.08    15.6   32.08
#Mann= 3 , 0 , 0
   -12.9    .035       0     -.7    .035       0     5.1    .035       0
#XS Ineff= 2 , 0
       0     -.7   32.48     5.1       0   32.28
Permanent Ineff=
       F       F
Bank Sta=-.7,5.1
XS Rating Curve= 0
Exp/Cntr=.3,.1

Type RM Length L Ch R = 1 ,1900.00 ,50,50,50
BEGIN DESCRIPTION:
38
END DESCRIPTION:
#Sta/Elev= 12
   -12.9   30.61    -2.9   30.61    -1.3   31.61     -.7   31.61     -.3   31.31
       0   31.31     1.5   29.51     3.5   29.51     5.1   31.61     5.5   31.61
     5.6   31.41    15.6   31.41
#Mann= 3 , 0 , 0
   -12.9    .035       0     -.7    .035       0     5.1    .035       0
#XS Ineff= 2 , 0
       0     -.7   31.61     5.1       0   31.61
Permanent Ineff=
       F       F
Bank Sta=-.7,5.1
XS Rating Curve= 0
Exp/Cntr=.3,.1

Type RM Length L Ch R = 1 ,1850.00 ,44,44,44
BEGIN DESCRIPTION:
37
END DESCRIPTION:
#Sta/Elev= 10
   -13.7   29.71    -3.7   29.71    -2.2   30.91       0   30.91     1.1   29.01
     3.3   29.01     4.4   30.91       5   30.91     5.6   30.41    15.6   30.41
#Mann= 3 , 0 , 0
   -13.7    .035       0       0    .035       0     4.4    .035       0
#XS Ineff= 2 , 0
               0   30.91     4.4           30.91
Permanent Ineff=
       F       F
Bank Sta=0,4.4
XS Rating Curve= 0
Exp/Cntr=.3,.1

Type RM Length L Ch R = 1 ,1806.00 ,6,6,6
BEGIN DESCRIPTION:
36.006
END DESCRIPTION:
#Sta/Elev= 10
   -13.7   29.28    -3.7   29.28    -2.2   30.48       0   30.48     1.6   28.28
     3.8   28.28     4.9   30.48     5.5   30.48     6.1   29.98    16.1   29.98
#Mann= 3 , 0 , 0
   -13.7    .035       0       0    .035       0     5.5    .035       0
#XS Ineff= 2 , 0
               0   30.48     5.5           30.48
Permanent Ineff=
       F       F
Bank Sta=0,5.5
XS Rating Curve= 0
Exp/Cntr=.3,.1

Type RM Length L Ch R = 1 ,1800.00 ,50,50,50
BEGIN DESCRIPTION:
36
END DESCRIPTION:
#Sta/Elev= 14
     -13   28.71      -3   28.71    -1.2   30.31       0   30.31      .4   30.01
      .7   30.01     1.8   28.21     3.9   28.21     5.1   30.01     5.3   30.01
     5.5   30.21     6.1   30.21     6.8   29.71    16.8   29.71
#Mann= 3 , 0 , 0
     -13    .035       0       0    .035       0     5.5    .035       0
#XS Ineff= 2 , 0
               0   30.31     5.5           30.21
Permanent Ineff=
       F       F
Bank Sta=0,5.5
XS Rating Curve= 0
Exp/Cntr=.3,.1

Type RM Length L Ch R = 1 ,1750.00 ,50,50,50
BEGIN DESCRIPTION:
35
END DESCRIPTION:
#Sta/Elev= 14
   -12.7   28.53    -2.7   28.53    -1.2   29.63       0   29.63      .5   29.33
      .8   29.33     1.8   27.63     4.1   27.63     5.3   29.23     5.6   29.23
     6.3   29.63     6.8   29.63     7.7   28.93    17.7   28.93
#Mann= 3 , 0 , 0
   -12.7    .035       0       0    .035       0     6.3    .035       0
#XS Ineff= 2 , 0
               0   29.63     6.3           29.63
Permanent Ineff=
       F       F
Bank Sta=0,6.3
XS Rating Curve= 0
Exp/Cntr=.3,.1

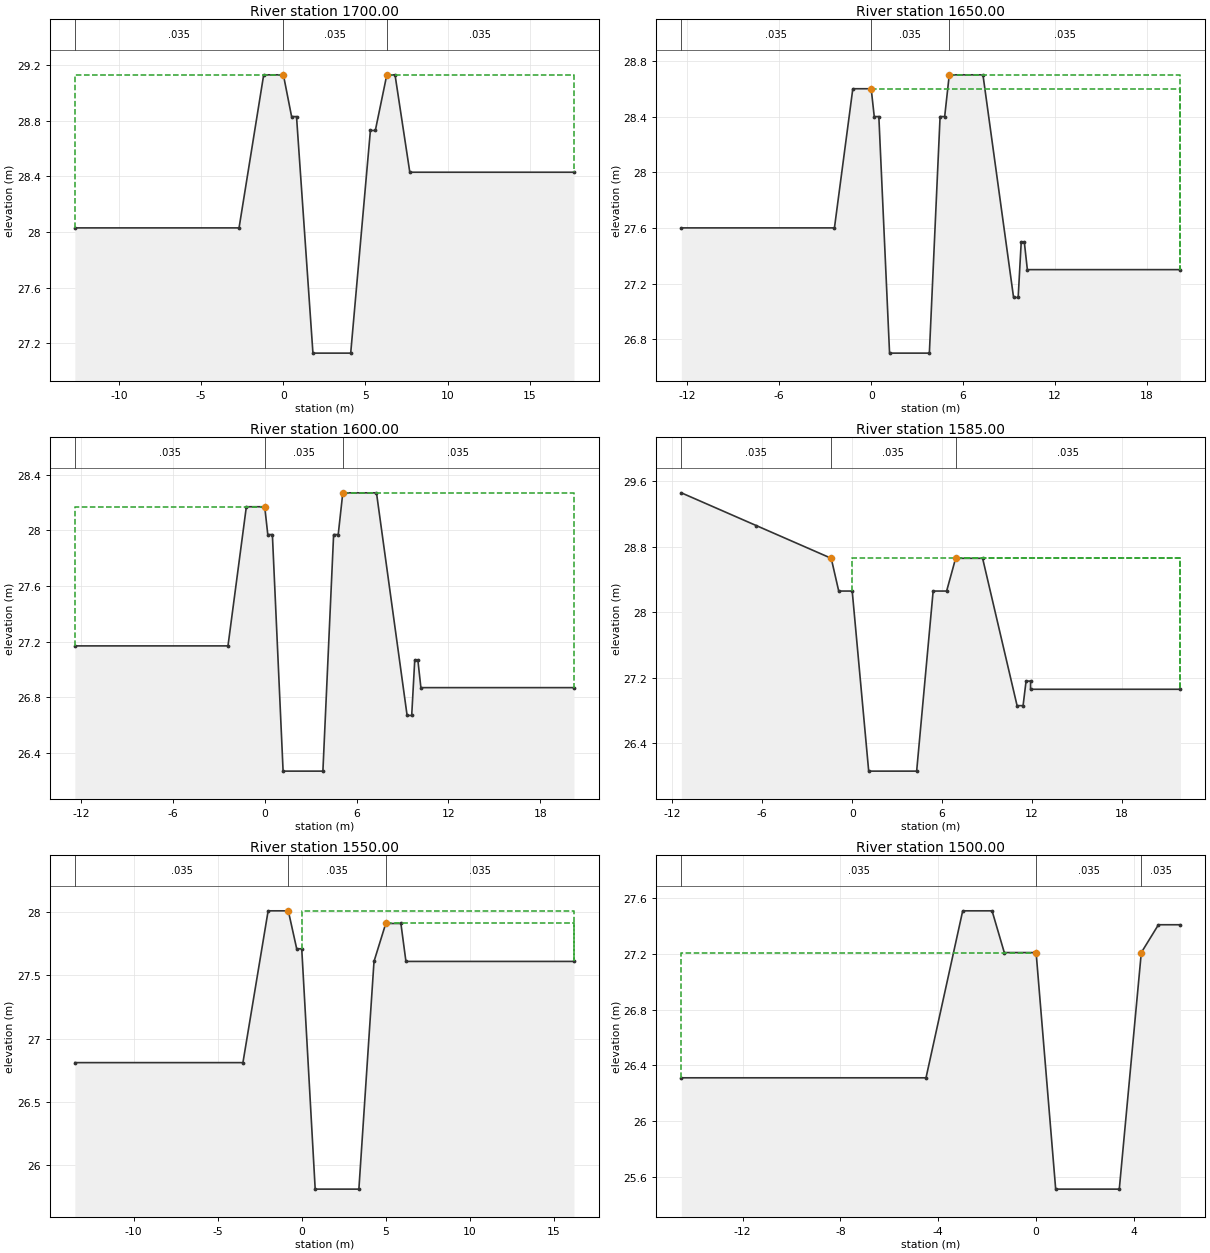
Type RM Length L Ch R = 1 ,1700.00 ,50,50,50
BEGIN DESCRIPTION:
34
END DESCRIPTION:
#Sta/Elev= 14
   -12.7   28.03    -2.7   28.03    -1.2   29.13       0   29.13      .5   28.83
      .8   28.83     1.8   27.13     4.1   27.13     5.3   28.73     5.6   28.73
     6.3   29.13     6.8   29.13     7.7   28.43    17.7   28.43
#Mann= 3 , 0 , 0
   -12.7    .035       0       0    .035       0     6.3    .035       0
#XS Ineff= 2 , 0
               0   29.13     6.3           29.13
Permanent Ineff=
       F       F
Bank Sta=0,6.3
XS Rating Curve= 0
Exp/Cntr=.3,.1

Type RM Length L Ch R = 1 ,1650.00 ,50,50,50
BEGIN DESCRIPTION:
33
END DESCRIPTION:
#Sta/Elev= 18
   -12.4    27.6    -2.4    27.6    -1.2    28.6       0    28.6      .2    28.4
      .5    28.4     1.2    26.7     3.8    26.7     4.5    28.4     4.8    28.4
     5.1    28.7     7.3    28.7     9.3    27.1     9.6    27.1     9.8    27.5
      10    27.5    10.2    27.3    20.2    27.3
#Mann= 3 , 0 , 0
   -12.4    .035       0       0    .035       0     5.1    .035       0
#XS Ineff= 2 , 0
       0       0    28.6     5.1       0    28.7
Permanent Ineff=
       F       F
Bank Sta=0,5.1
XS Rating Curve= 0
Exp/Cntr=.3,.1

Type RM Length L Ch R = 1 ,1600.00 ,15,15,15
BEGIN DESCRIPTION:
32
END DESCRIPTION:
#Sta/Elev= 18
   -12.4   27.17    -2.4   27.17    -1.2   28.17       0   28.17      .2   27.97
      .5   27.97     1.2   26.27     3.8   26.27     4.5   27.97     4.8   27.97
     5.1   28.27     7.3   28.27     9.3   26.67     9.6   26.67     9.8   27.07
      10   27.07    10.2   26.87    20.2   26.87
#Mann= 3 , 0 , 0
   -12.4    .035       0       0    .035       0     5.1    .035       0
#XS Ineff= 2 , 0
               0   28.17     5.1           28.27
Permanent Ineff=
       F       F
Bank Sta=0,5.1
XS Rating Curve= 0
Exp/Cntr=.3,.1

Type RM Length L Ch R = 1 ,1585.00 ,35,35,35
BEGIN DESCRIPTION:
31.035
END DESCRIPTION:
#Sta/Elev= 17
   -11.4   29.46    -6.4   29.06    -1.4   28.66     -.9   28.26       0   28.26
     1.1   26.06     4.3   26.06     5.4   28.26     6.3   28.26     6.9   28.66
     8.7   28.66      11   26.86    11.4   26.86    11.6   27.16    11.9   27.16
    11.9   27.06    21.9   27.06
#Mann= 3 , 0 , 0
   -11.4    .035       0    -1.4    .035       0     6.9    .035       0
#XS Ineff= 2 , 0
       0    -1.4   28.66     6.9       0   28.66
Permanent Ineff=
       F       F
Bank Sta=-1.4,6.9
XS Rating Curve= 0
Exp/Cntr=.3,.1

Type RM Length L Ch R = 1 ,1550.00 ,50,50,50
BEGIN DESCRIPTION:
31
END DESCRIPTION:
#Sta/Elev= 13
   -13.5   26.81    -3.5   26.81      -2   28.01     -.8   28.01     -.3   27.71
       0   27.71      .8   25.81     3.4   25.81     4.3   27.61       5   27.91
     5.9   27.91     6.2   27.61    16.2   27.61
#Mann= 3 , 0 , 0
   -13.5    .035       0     -.8    .035       0       5    .035       0
#XS Ineff= 2 , 0
       0     -.8   28.01       5       0   27.91
Permanent Ineff=
       F       F
Bank Sta=-.8,5
XS Rating Curve= 0
Exp/Cntr=.3,.1

Type RM Length L Ch R = 1 ,1500.00 ,10,10,10
BEGIN DESCRIPTION:
30
END DESCRIPTION:
#Sta/Elev= 11
   -14.5   26.31    -4.5   26.31      -3   27.51    -1.8   27.51    -1.3   27.21
       0   27.21      .8   25.51     3.4   25.51     4.3   27.21       5   27.41
     5.9   27.41
#Mann= 3 , 0 , 0
   -14.5    .035       0       0    .035       0     4.3    .035       0
#XS Ineff= 2 , 0
               0   27.21     4.3           27.21
Permanent Ineff=
       F       F
Bank Sta=0,4.3
XS Rating Curve= 0
Exp/Cntr=.3,.1

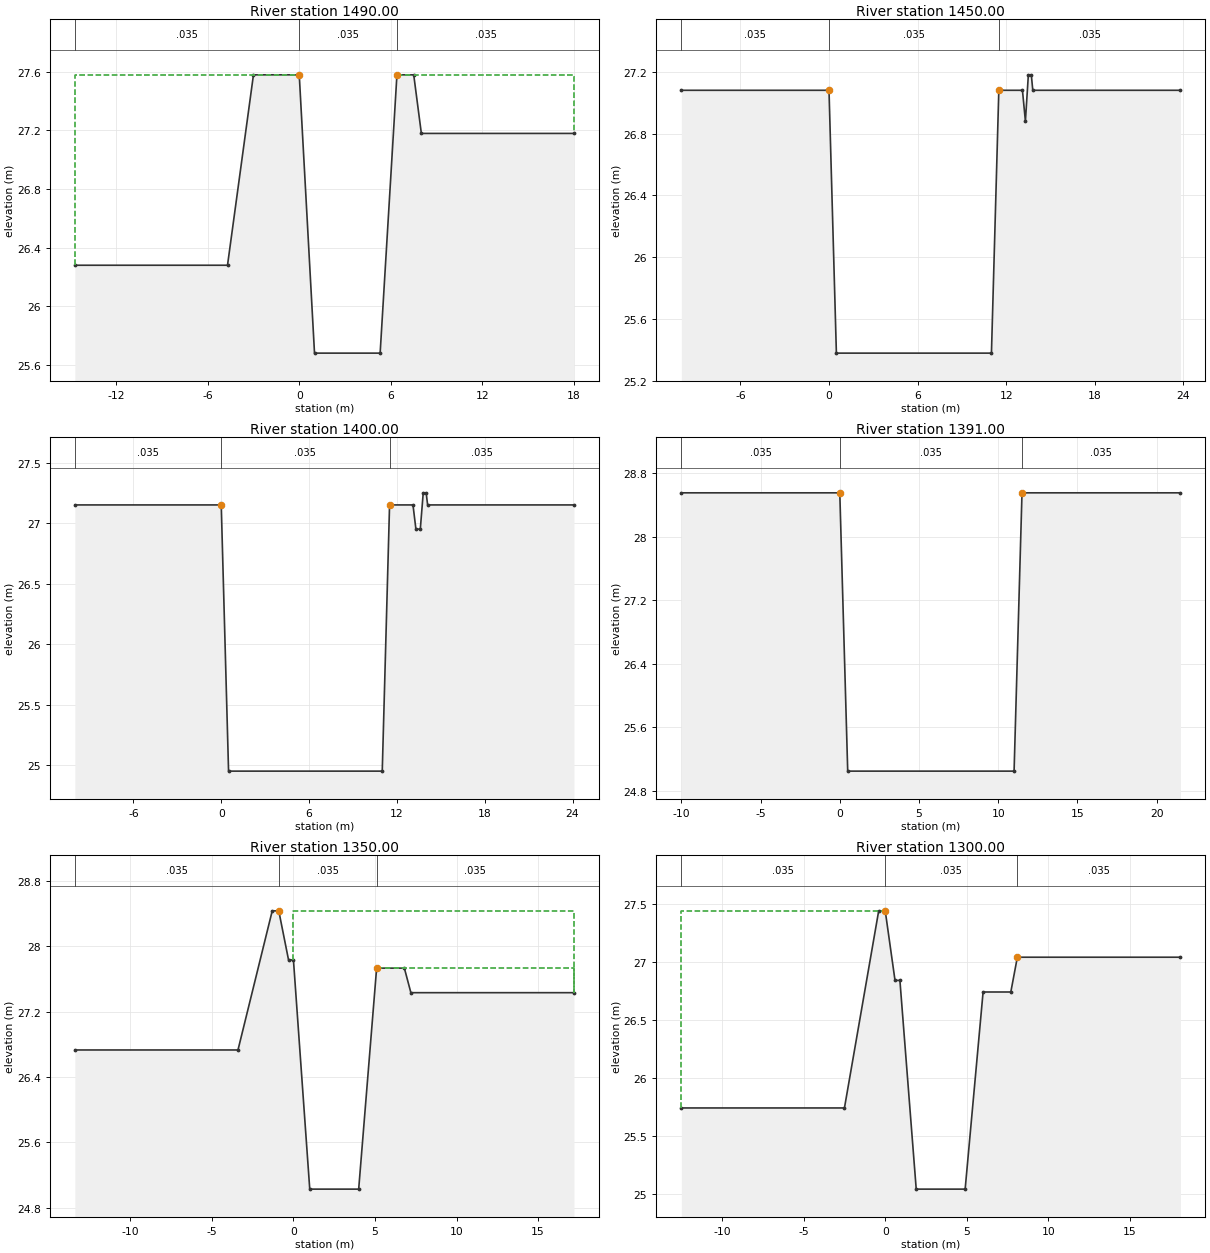
Type RM Length L Ch R = 1 ,1490.00 ,40,40,40
BEGIN DESCRIPTION:
29.04
END DESCRIPTION:
#Sta/Elev= 10
   -14.7   26.28    -4.7   26.28      -3   27.58       0   27.58       1   25.68
     5.3   25.68     6.4   27.58     7.5   27.58       8   27.18      18   27.18
#Mann= 3 , 0 , 0
   -14.7    .035       0       0    .035       0     6.4    .035       0
#XS Ineff= 2 , 0
               0   27.58     6.4           27.58
Permanent Ineff=
       F       F
Bank Sta=0,6.4
XS Rating Curve= 0
Exp/Cntr=.3,.1

Type RM Length L Ch R = 1 ,1450.00 ,50,50,50
BEGIN DESCRIPTION:
29
END DESCRIPTION:
#Sta/Elev= 11
     -10   27.08       0   27.08      .5   25.38      11   25.38    11.5   27.08
    13.1   27.08    13.3   26.88    13.5   27.18    13.7   27.18    13.8   27.08
    23.8   27.08
#Mann= 3 , 0 , 0
     -10    .035       0       0    .035       0    11.5    .035       0
#XS Ineff= 2 , 0
               0   27.08    11.5           27.08
Permanent Ineff=
       F       F
Bank Sta=0,11.5
XS Rating Curve= 0
Exp/Cntr=.3,.1

Type RM Length L Ch R = 1 ,1400.00 ,9,9,9
BEGIN DESCRIPTION:
28
END DESCRIPTION:
#Sta/Elev= 12
     -10   27.15       0   27.15      .5   24.95      11   24.95    11.5   27.15
    13.1   27.15    13.3   26.95    13.6   26.95    13.8   27.25      14   27.25
    14.1   27.15    24.1   27.15
#Mann= 3 , 0 , 0
     -10    .035       0       0    .035       0    11.5    .035       0
#XS Ineff= 2 , 0
               0   27.15    11.5           27.15
Permanent Ineff=
       F       F
Bank Sta=0,11.5
XS Rating Curve= 0
Exp/Cntr=.3,.1

Type RM Length L Ch R = 1 ,1391.00 ,41,41,41
BEGIN DESCRIPTION:
27.041
END DESCRIPTION:
#Sta/Elev= 6
     -10   28.55       0   28.55      .5   25.05      11   25.05    11.5   28.55
    21.5   28.55
#Mann= 3 , 0 , 0
     -10    .035       0       0    .035       0    11.5    .035       0
#XS Ineff= 2 , 0
               0   28.55    11.5           28.55
Permanent Ineff=
       F       F
Bank Sta=0,11.5
XS Rating Curve= 0
Exp/Cntr=.3,.1

Type RM Length L Ch R = 1 ,1350.00 ,50,50,50
BEGIN DESCRIPTION:
27
END DESCRIPTION:
#Sta/Elev= 12
   -13.4   26.73    -3.4   26.73    -1.3   28.43     -.9   28.43     -.3   27.83
       0   27.83       1   25.03       4   25.03     5.1   27.73     6.8   27.73
     7.2   27.43    17.2   27.43
#Mann= 3 , 0 , 0
   -13.4    .035       0     -.9    .035       0     5.1    .035       0
#XS Ineff= 2 , 0
       0     -.9   28.43     5.1       0   27.73
Permanent Ineff=
       F       F
Bank Sta=-.9,5.1
XS Rating Curve= 0
Exp/Cntr=.3,.1

Type RM Length L Ch R = 1 ,1300.00 ,50,50,50
BEGIN DESCRIPTION:
26
END DESCRIPTION:
#Sta/Elev= 12
   -12.5   25.74    -2.5   25.74     -.4   27.44       0   27.44      .6   26.84
      .9   26.84     1.9   25.04     4.9   25.04       6   26.74     7.7   26.74
     8.1   27.04    18.1   27.04
#Mann= 3 , 0 , 0
   -12.5    .035       0       0    .035       0     8.1    .035       0
#XS Ineff= 2 , 0
               0   27.44     8.1           27.04
Permanent Ineff=
       F       F
Bank Sta=0,8.1
XS Rating Curve= 0
Exp/Cntr=.3,.1