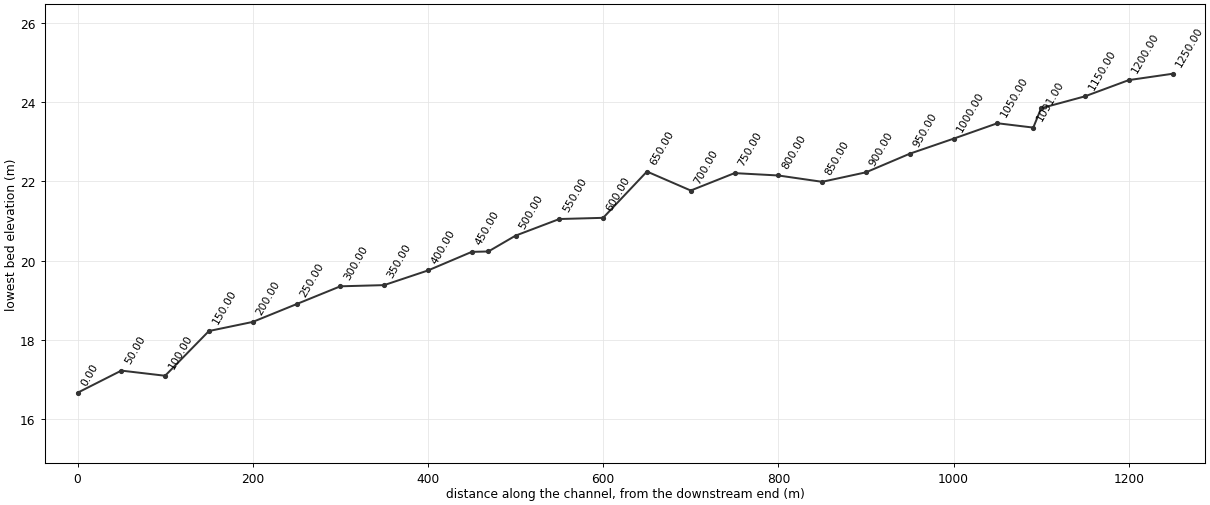
HEC-RAS study BONG.prj: dongduk-chon

--- BONG.g01 (geometry) --- (continued)

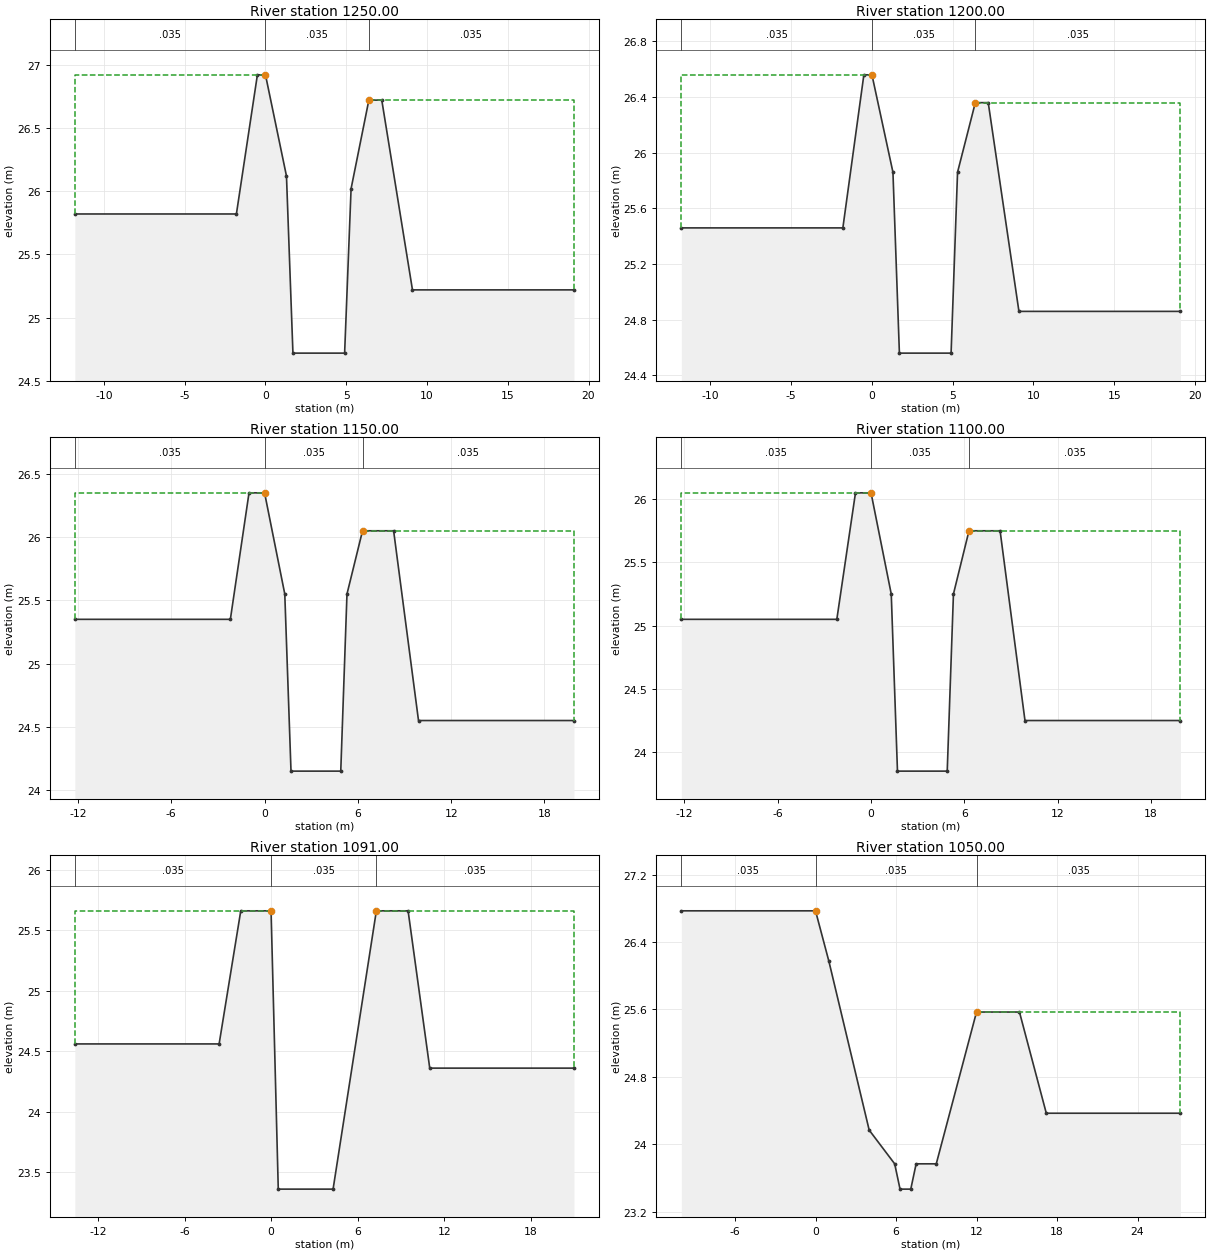
Type RM Length L Ch R = 1 ,1250.00 ,50,50,50
BEGIN DESCRIPTION:
25
END DESCRIPTION:
#Sta/Elev= 12
   -11.8   25.82    -1.8   25.82     -.5   26.92       0   26.92     1.3   26.12
     1.7   24.72     4.9   24.72     5.3   26.02     6.4   26.72     7.2   26.72
     9.1   25.22    19.1   25.22
#Mann= 3 , 0 , 0
   -11.8    .035       0       0    .035       0     6.4    .035       0
#XS Ineff= 2 , 0
               0   26.92     6.4           26.72
Permanent Ineff=
       F       F
Bank Sta=0,6.4
XS Rating Curve= 0
Exp/Cntr=.3,.1

Type RM Length L Ch R = 1 ,1200.00 ,50,50,50
BEGIN DESCRIPTION:
24
END DESCRIPTION:
#Sta/Elev= 12
   -11.8   25.46    -1.8   25.46     -.5   26.56       0   26.56     1.3   25.86
     1.7   24.56     4.9   24.56     5.3   25.86     6.4   26.36     7.2   26.36
     9.1   24.86    19.1   24.86
#Mann= 3 , 0 , 0
   -11.8    .035       0       0    .035       0     6.4    .035       0
#XS Ineff= 2 , 0
               0   26.56     6.4           26.36
Permanent Ineff=
       F       F
Bank Sta=0,6.4
XS Rating Curve= 0
Exp/Cntr=.3,.1

Type RM Length L Ch R = 1 ,1150.00 ,50,50,50
BEGIN DESCRIPTION:
23
END DESCRIPTION:
#Sta/Elev= 12
   -12.2   25.35    -2.2   25.35      -1   26.35       0   26.35     1.3   25.55
     1.7   24.15     4.9   24.15     5.3   25.55     6.3   26.05     8.3   26.05
     9.9   24.55    19.9   24.55
#Mann= 3 , 0 , 0
   -12.2    .035       0       0    .035       0     6.3    .035       0
#XS Ineff= 2 , 0
               0   26.35     6.3           26.05
Permanent Ineff=
       F       F
Bank Sta=0,6.3
XS Rating Curve= 0
Exp/Cntr=.3,.1

Type RM Length L Ch R = 1 ,1100.00 ,9,9,9
BEGIN DESCRIPTION:
22
END DESCRIPTION:
#Sta/Elev= 12
   -12.2   25.05    -2.2   25.05      -1   26.05       0   26.05     1.3   25.25
     1.7   23.85     4.9   23.85     5.3   25.25     6.3   25.75     8.3   25.75
     9.9   24.25    19.9   24.25
#Mann= 3 , 0 , 0
   -12.2    .035       0       0    .035       0     6.3    .035       0
#XS Ineff= 2 , 0
               0   26.05     6.3           25.75
Permanent Ineff=
       F       F
Bank Sta=0,6.3
XS Rating Curve= 0
Exp/Cntr=.3,.1

Type RM Length L Ch R = 1 ,1091.00 ,41,41,41
BEGIN DESCRIPTION:
21.041
END DESCRIPTION:
#Sta/Elev= 10
   -13.6   24.56    -3.6   24.56    -2.1   25.66       0   25.66      .5   23.36
     4.3   23.36     7.3   25.66     9.5   25.66      11   24.36      21   24.36
#Mann= 3 , 0 , 0
   -13.6    .035       0       0    .035       0     7.3    .035       0
#XS Ineff= 2 , 0
               0   25.66     7.3           25.66
Permanent Ineff=
       F       F
Bank Sta=0,7.3
XS Rating Curve= 0
Exp/Cntr=.3,.1

Type RM Length L Ch R = 1 ,1050.00 ,50,50,50
BEGIN DESCRIPTION:
21
END DESCRIPTION:
#Sta/Elev= 13
     -10   26.77       0   26.77       1   26.17       4   24.17     5.9   23.77
     6.3   23.47     7.1   23.47     7.5   23.77       9   23.77      12   25.57
    15.2   25.57    17.2   24.37    27.2   24.37
#Mann= 3 , 0 , 0
     -10    .035       0       0    .035       0      12    .035       0
#XS Ineff= 2 , 0
               0   26.77      12           25.57
Permanent Ineff=
       F       F
Bank Sta=0,12
XS Rating Curve= 0
Exp/Cntr=.3,.1

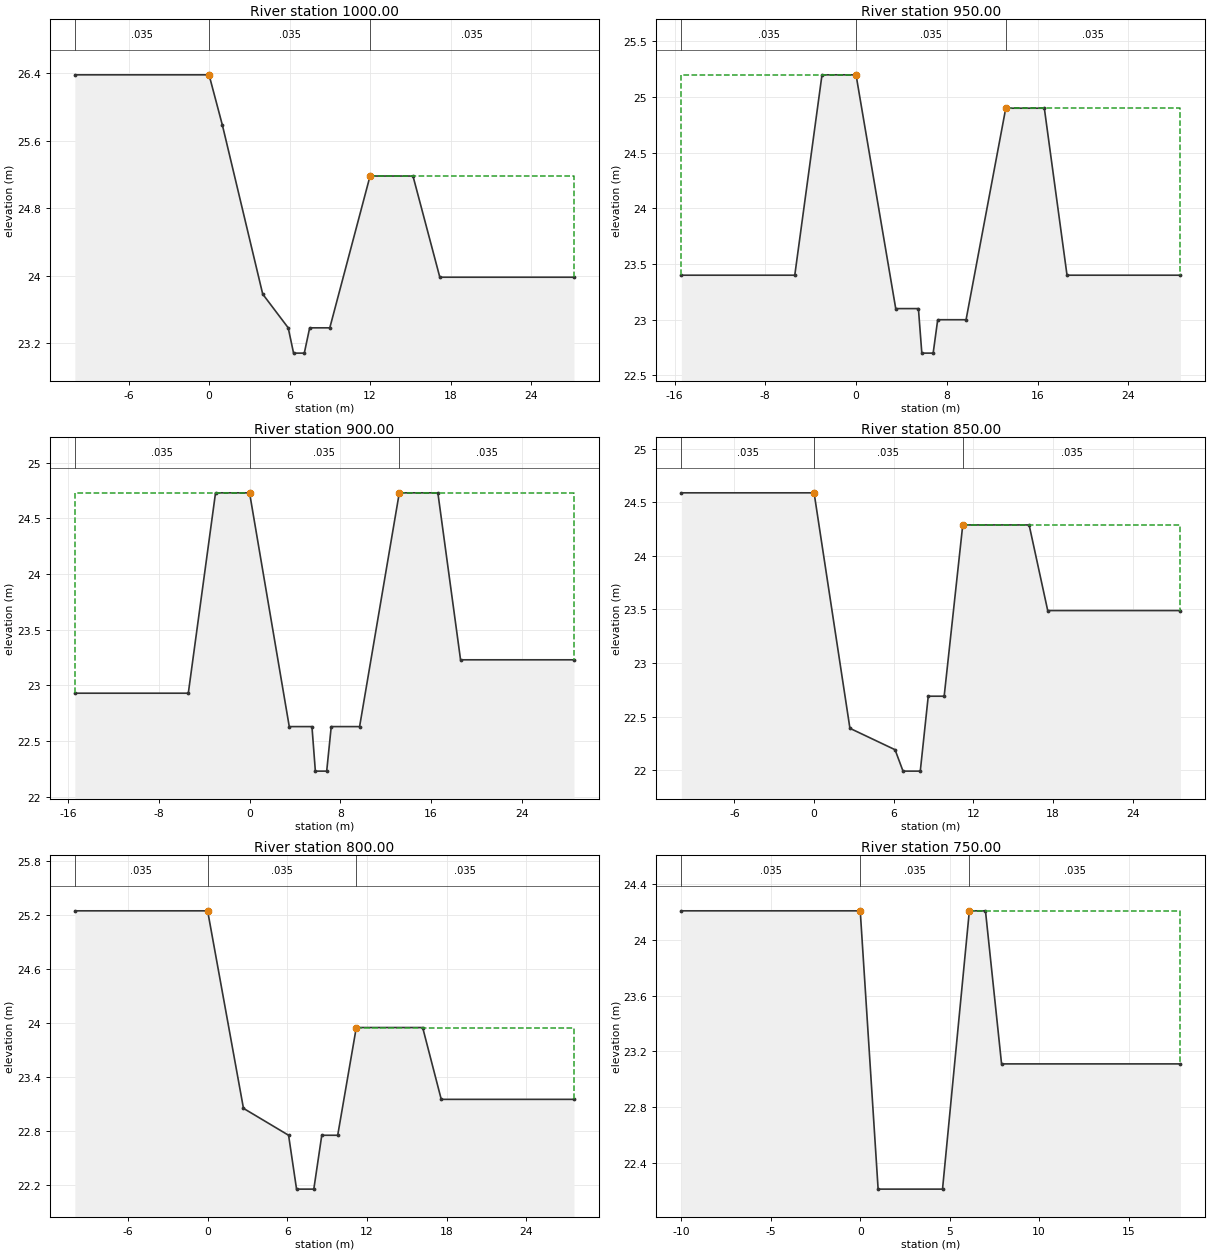
Type RM Length L Ch R = 1 ,1000.00 ,50,50,50
BEGIN DESCRIPTION:
20
END DESCRIPTION:
#Sta/Elev= 13
     -10   26.38       0   26.38       1   25.78       4   23.78     5.9   23.38
     6.3   23.08     7.1   23.08     7.5   23.38       9   23.38      12   25.18
    15.2   25.18    17.2   23.98    27.2   23.98
#Mann= 3 , 0 , 0
     -10    .035       0       0    .035       0      12    .035       0
#XS Ineff= 2 , 0
               0   26.38      12           25.18
Permanent Ineff=
       F       F
Bank Sta=0,12
XS Rating Curve= 0
Exp/Cntr=.3,.1

Type RM Length L Ch R = 1 ,950.00  ,50,50,50
BEGIN DESCRIPTION:
19
END DESCRIPTION:
#Sta/Elev= 14
   -15.4    23.4    -5.4    23.4      -3    25.2       0    25.2     3.5    23.1
     5.5    23.1     5.8    22.7     6.8    22.7     7.2      23     9.7      23
    13.2    24.9    16.6    24.9    18.6    23.4    28.6    23.4
#Mann= 3 , 0 , 0
   -15.4    .035       0       0    .035       0    13.2    .035       0
#XS Ineff= 2 , 0
               0    25.2    13.2            24.9
Permanent Ineff=
       F       F
Bank Sta=0,13.2
XS Rating Curve= 0
Exp/Cntr=.3,.1

Type RM Length L Ch R = 1 ,900.00  ,50,50,50
BEGIN DESCRIPTION:
18
END DESCRIPTION:
#Sta/Elev= 14
   -15.4   22.93    -5.4   22.93      -3   24.73       0   24.73     3.5   22.63
     5.5   22.63     5.8   22.23     6.8   22.23     7.2   22.63     9.7   22.63
    13.2   24.73    16.6   24.73    18.6   23.23    28.6   23.23
#Mann= 3 , 0 , 0
   -15.4    .035       0       0    .035       0    13.2    .035       0
#XS Ineff= 2 , 0
               0   24.73    13.2           24.73
Permanent Ineff=
       F       F
Bank Sta=0,13.2
XS Rating Curve= 0
Exp/Cntr=.3,.1

Type RM Length L Ch R = 1 ,850.00  ,50,50,50
BEGIN DESCRIPTION:
17
END DESCRIPTION:
#Sta/Elev= 12
     -10   24.59       0   24.59     2.7   22.39     6.1   22.19     6.7   21.99
       8   21.99     8.6   22.69     9.8   22.69    11.2   24.29    16.2   24.29
    17.6   23.49    27.6   23.49
#Mann= 3 , 0 , 0
     -10    .035       0       0    .035       0    11.2    .035       0
#XS Ineff= 2 , 0
               0   24.59    11.2           24.29
Permanent Ineff=
       F       F
Bank Sta=0,11.2
XS Rating Curve= 0
Exp/Cntr=.3,.1

Type RM Length L Ch R = 1 ,800.00  ,50,50,50
BEGIN DESCRIPTION:
16
END DESCRIPTION:
#Sta/Elev= 12
     -10   25.25       0   25.25     2.7   23.05     6.1   22.75     6.7   22.15
       8   22.15     8.6   22.75     9.8   22.75    11.2   23.95    16.2   23.95
    17.6   23.15    27.6   23.15
#Mann= 3 , 0 , 0
     -10    .035       0       0    .035       0    11.2    .035       0
#XS Ineff= 2 , 0
               0   25.25    11.2           23.95
Permanent Ineff=
       F       F
Bank Sta=0,11.2
XS Rating Curve= 0
Exp/Cntr=.3,.1

Type RM Length L Ch R = 1 ,750.00  ,50,50,50
BEGIN DESCRIPTION:
15
END DESCRIPTION:
#Sta/Elev= 8
     -10   24.21       0   24.21       1   22.21     4.6   22.21     6.1   24.21
       7   24.21     7.9   23.11    17.9   23.11
#Mann= 3 , 0 , 0
     -10    .035       0       0    .035       0     6.1    .035       0
#XS Ineff= 2 , 0
               0   24.21     6.1           24.21
Permanent Ineff=
       F       F
Bank Sta=0,6.1
XS Rating Curve= 0
Exp/Cntr=.3,.1

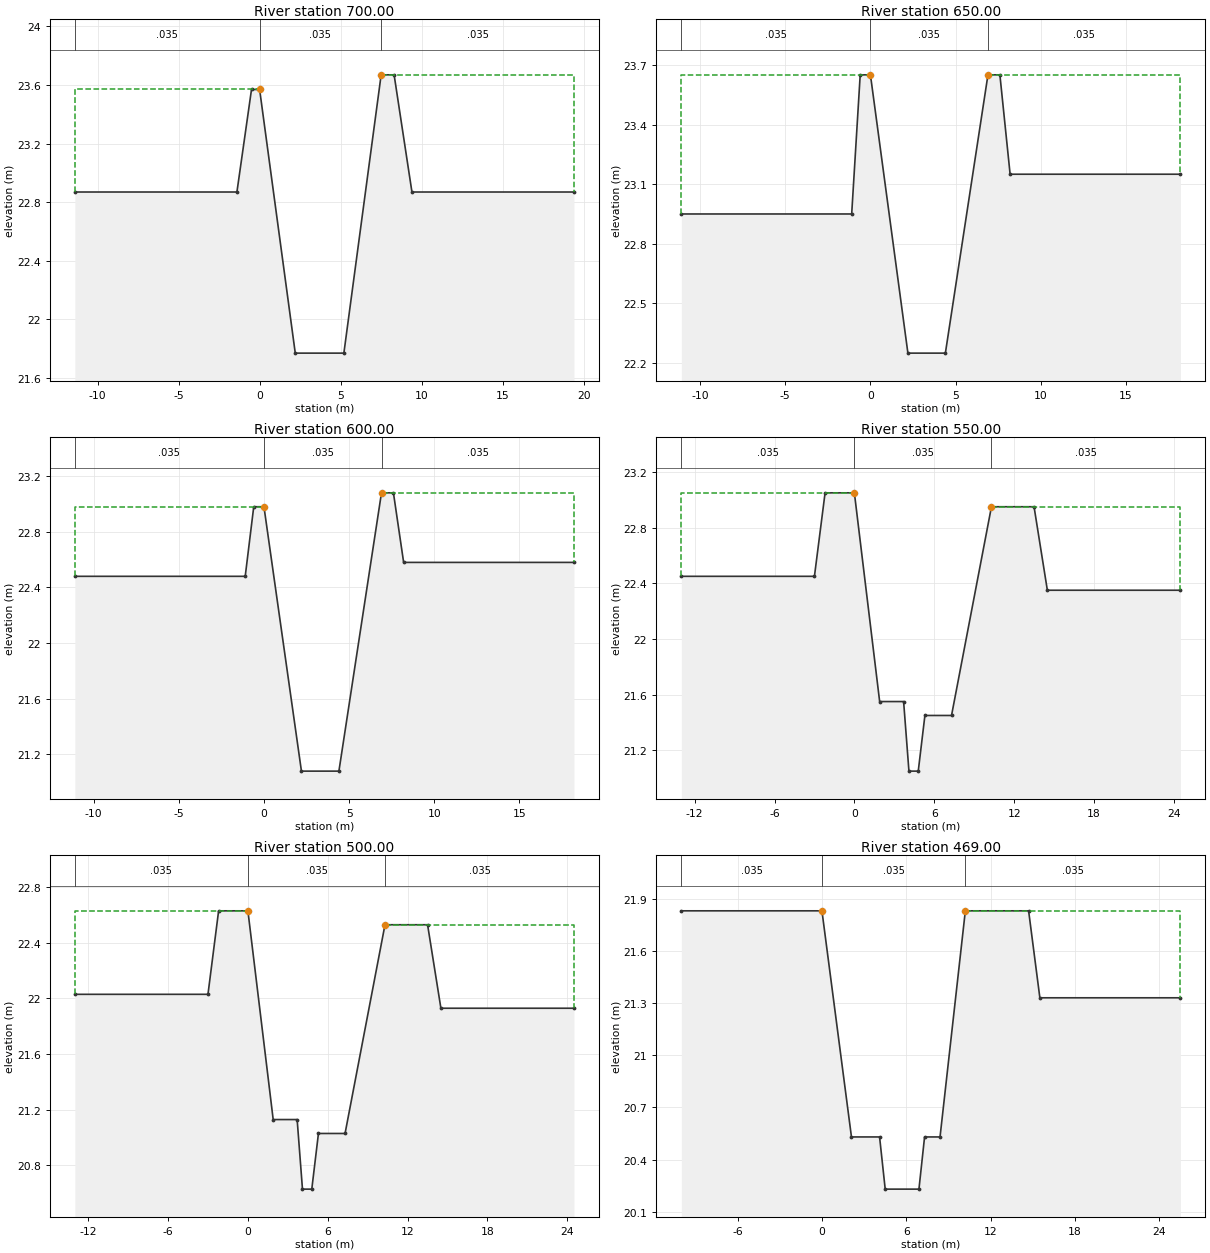
Type RM Length L Ch R = 1 ,700.00  ,50,50,50
BEGIN DESCRIPTION:
14
END DESCRIPTION:
#Sta/Elev= 10
   -11.4   22.87    -1.4   22.87     -.5   23.57       0   23.57     2.2   21.77
     5.2   21.77     7.5   23.67     8.3   23.67     9.4   22.87    19.4   22.87
#Mann= 3 , 0 , 0
   -11.4    .035       0       0    .035       0     7.5    .035       0
#XS Ineff= 2 , 0
               0   23.57     7.5           23.67
Permanent Ineff=
       F       F
Bank Sta=0,7.5
XS Rating Curve= 0
Exp/Cntr=.3,.1

Type RM Length L Ch R = 1 ,650.00  ,50,50,50
BEGIN DESCRIPTION:
13
END DESCRIPTION:
#Sta/Elev= 10
   -11.1   22.95    -1.1   22.95     -.6   23.65       0   23.65     2.2   22.25
     4.4   22.25     6.9   23.65     7.6   23.65     8.2   23.15    18.2   23.15
#Mann= 3 , 0 , 0
   -11.1    .035       0       0    .035       0     6.9    .035       0
#XS Ineff= 2 , 0
               0   23.65     6.9           23.65
Permanent Ineff=
       F       F
Bank Sta=0,6.9
XS Rating Curve= 0
Exp/Cntr=.3,.1

Type RM Length L Ch R = 1 ,600.00  ,50,50,50
BEGIN DESCRIPTION:
12
END DESCRIPTION:
#Sta/Elev= 10
   -11.1   22.48    -1.1   22.48     -.6   22.98       0   22.98     2.2   21.08
     4.4   21.08     6.9   23.08     7.6   23.08     8.2   22.58    18.2   22.58
#Mann= 3 , 0 , 0
   -11.1    .035       0       0    .035       0     6.9    .035       0
#XS Ineff= 2 , 0
               0   22.98     6.9           23.08
Permanent Ineff=
       F       F
Bank Sta=0,6.9
XS Rating Curve= 0
Exp/Cntr=.3,.1

Type RM Length L Ch R = 1 ,550.00  ,50,50,50
BEGIN DESCRIPTION:
11
END DESCRIPTION:
#Sta/Elev= 14
     -13   22.45      -3   22.45    -2.2   23.05       0   23.05     1.9   21.55
     3.7   21.55     4.1   21.05     4.8   21.05     5.3   21.45     7.3   21.45
    10.3   22.95    13.5   22.95    14.5   22.35    24.5   22.35
#Mann= 3 , 0 , 0
     -13    .035       0       0    .035       0    10.3    .035       0
#XS Ineff= 2 , 0
               0   23.05    10.3           22.95
Permanent Ineff=
       F       F
Bank Sta=0,10.3
XS Rating Curve= 0
Exp/Cntr=.3,.1

Type RM Length L Ch R = 1 ,500.00  ,31,31,31
BEGIN DESCRIPTION:
10
END DESCRIPTION:
#Sta/Elev= 14
     -13   22.03      -3   22.03    -2.2   22.63       0   22.63     1.9   21.13
     3.7   21.13     4.1   20.63     4.8   20.63     5.3   21.03     7.3   21.03
    10.3   22.53    13.5   22.53    14.5   21.93    24.5   21.93
#Mann= 3 , 0 , 0
     -13    .035       0       0    .035       0    10.3    .035       0
#XS Ineff= 2 , 0
               0   22.63    10.3           22.53
Permanent Ineff=
       F       F
Bank Sta=0,10.3
XS Rating Curve= 0
Exp/Cntr=.3,.1

Type RM Length L Ch R = 1 ,469.00  ,19,19,19
BEGIN DESCRIPTION:
9.019
END DESCRIPTION:
#Sta/Elev= 12
     -10   21.83       0   21.83     2.1   20.53     4.1   20.53     4.5   20.23
     6.9   20.23     7.3   20.53     8.4   20.53    10.2   21.83    14.7   21.83
    15.5   21.33    25.5   21.33
#Mann= 3 , 0 , 0
     -10    .035       0       0    .035       0    10.2    .035       0
#XS Ineff= 2 , 0
               0   21.83    10.2           21.83
Permanent Ineff=
       F       F
Bank Sta=0,10.2
XS Rating Curve= 0
Exp/Cntr=.3,.1

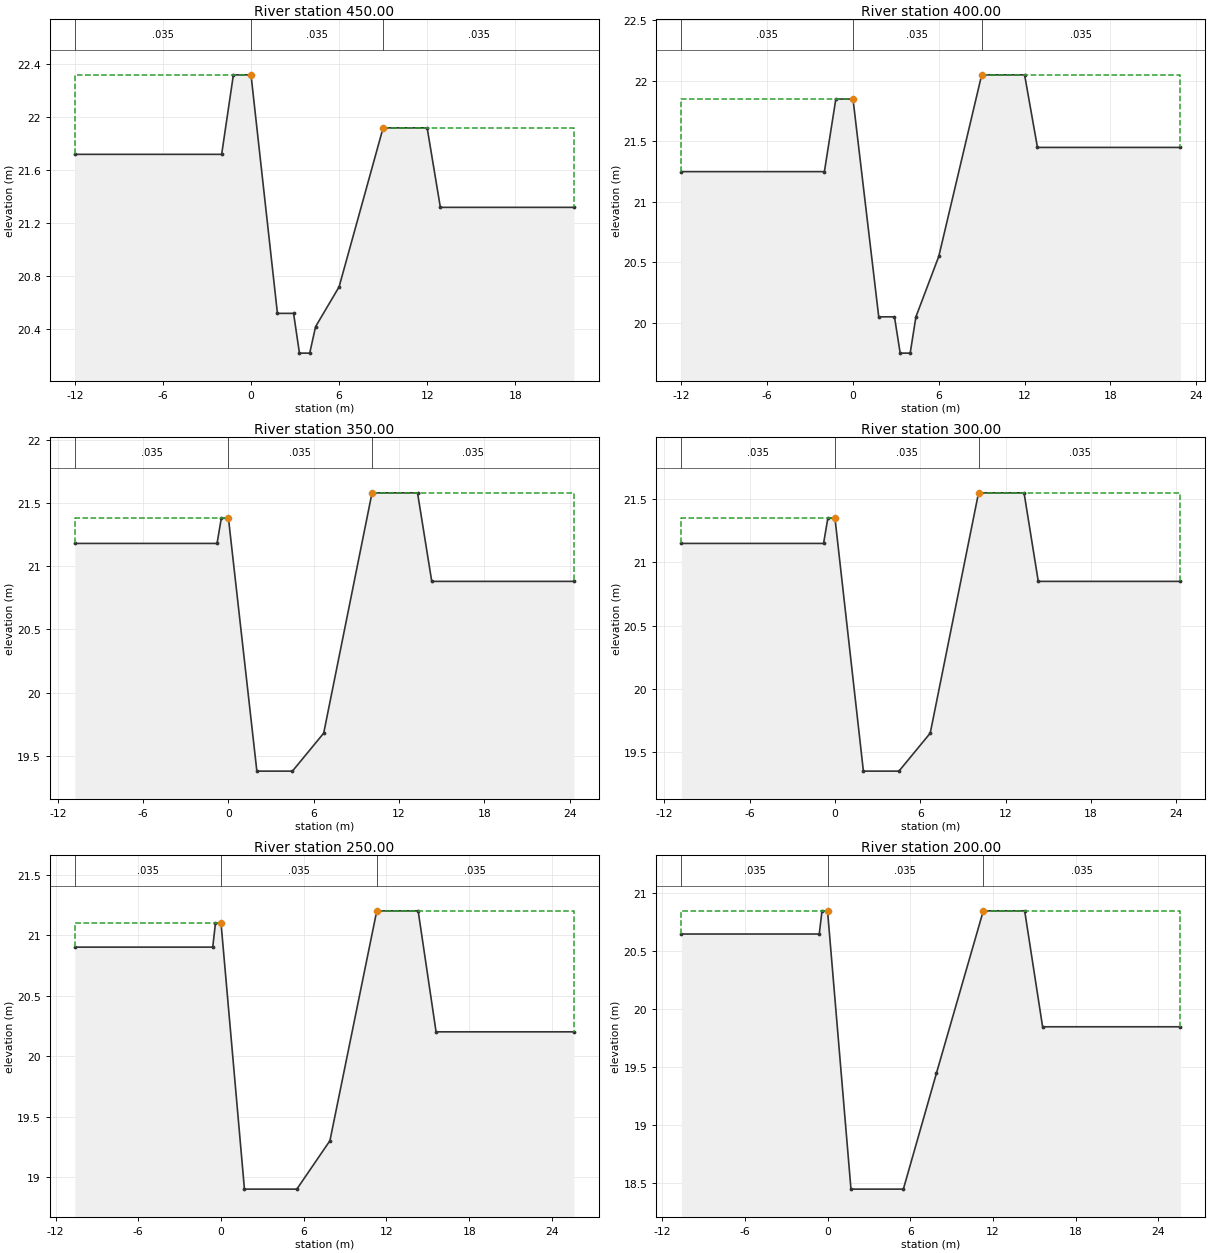
Type RM Length L Ch R = 1 ,450.00  ,50,50,50
BEGIN DESCRIPTION:
9
END DESCRIPTION:
#Sta/Elev= 14
     -12   21.72      -2   21.72    -1.2   22.32       0   22.32     1.8   20.52
     2.9   20.52     3.3   20.22       4   20.22     4.4   20.42       6   20.72
       9   21.92      12   21.92    12.9   21.32      22   21.32
#Mann= 3 , 0 , 0
     -12    .035       0       0    .035       0       9    .035       0
#XS Ineff= 2 , 0
               0   22.32       9           21.92
Permanent Ineff=
       F       F
Bank Sta=0,9
XS Rating Curve= 0
Exp/Cntr=.3,.1

Type RM Length L Ch R = 1 ,400.00  ,50,50,50
BEGIN DESCRIPTION:
8
END DESCRIPTION:
#Sta/Elev= 14
     -12   21.25      -2   21.25    -1.2   21.85       0   21.85     1.8   20.05
     2.9   20.05     3.3   19.75       4   19.75     4.4   20.05       6   20.55
       9   22.05      12   22.05    12.9   21.45    22.9   21.45
#Mann= 3 , 0 , 0
     -12    .035       0       0    .035       0       9    .035       0
#XS Ineff= 2 , 0
               0   21.85       9           22.05
Permanent Ineff=
       F       F
Bank Sta=0,9
XS Rating Curve= 0
Exp/Cntr=.3,.1

Type RM Length L Ch R = 1 ,350.00  ,50,50,50
BEGIN DESCRIPTION:
7
END DESCRIPTION:
#Sta/Elev= 11
   -10.8   21.18     -.8   21.18     -.5   21.38       0   21.38       2   19.38
     4.5   19.38     6.7   19.68    10.1   21.58    13.3   21.58    14.3   20.88
    24.3   20.88
#Mann= 3 , 0 , 0
   -10.8    .035       0       0    .035       0    10.1    .035       0
#XS Ineff= 2 , 0
               0   21.38    10.1           21.58
Permanent Ineff=
       F       F
Bank Sta=0,10.1
XS Rating Curve= 0
Exp/Cntr=.3,.1

Type RM Length L Ch R = 1 ,300.00  ,50,50,50
BEGIN DESCRIPTION:
6
END DESCRIPTION:
#Sta/Elev= 11
   -10.8   21.15     -.8   21.15     -.5   21.35       0   21.35       2   19.35
     4.5   19.35     6.7   19.65    10.1   21.55    13.3   21.55    14.3   20.85
    24.3   20.85
#Mann= 3 , 0 , 0
   -10.8    .035       0       0    .035       0    10.1    .035       0
#XS Ineff= 2 , 0
               0   21.35    10.1           21.55
Permanent Ineff=
       F       F
Bank Sta=0,10.1
XS Rating Curve= 0
Exp/Cntr=.3,.1

Type RM Length L Ch R = 1 ,250.00  ,50,50,50
BEGIN DESCRIPTION:
5
END DESCRIPTION:
#Sta/Elev= 11
   -10.6    20.9     -.6    20.9     -.4    21.1       0    21.1     1.7    18.9
     5.5    18.9     7.9    19.3    11.3    21.2    14.3    21.2    15.6    20.2
    25.6    20.2
#Mann= 3 , 0 , 0
   -10.6    .035       0       0    .035       0    11.3    .035       0
#XS Ineff= 2 , 0
               0    21.1    11.3            21.2
Permanent Ineff=
       F       F
Bank Sta=0,11.3
XS Rating Curve= 0
Exp/Cntr=.3,.1

Type RM Length L Ch R = 1 ,200.00  ,50,50,50
BEGIN DESCRIPTION:
4
END DESCRIPTION:
#Sta/Elev= 11
   -10.6   20.65     -.6   20.65     -.4   20.85       0   20.85     1.7   18.45
     5.5   18.45     7.9   19.45    11.3   20.85    14.3   20.85    15.6   19.85
    25.6   19.85
#Mann= 3 , 0 , 0
   -10.6    .035       0       0    .035       0    11.3    .035       0
#XS Ineff= 2 , 0
               0   20.85    11.3           20.85
Permanent Ineff=
       F       F
Bank Sta=0,11.3
XS Rating Curve= 0
Exp/Cntr=.3,.1

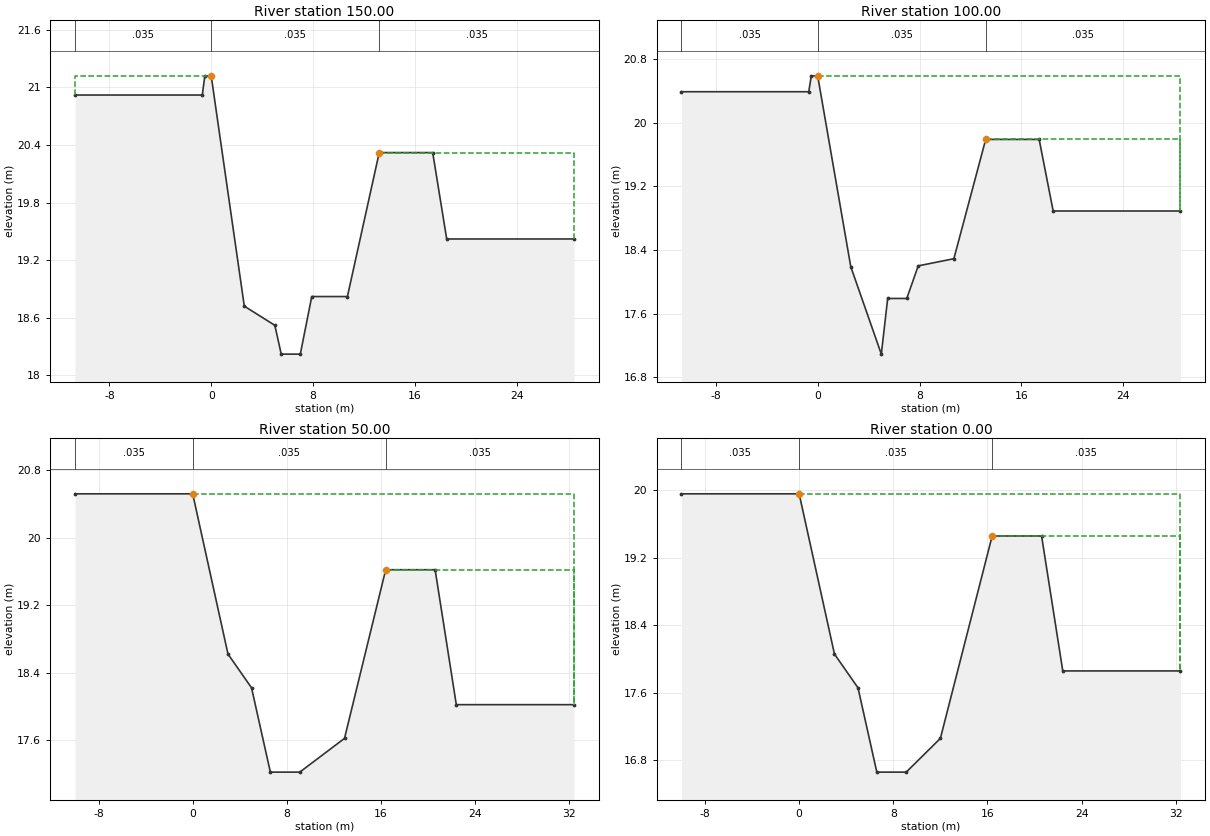
Type RM Length L Ch R = 1 ,150.00  ,50,50,50
BEGIN DESCRIPTION:
3
END DESCRIPTION:
#Sta/Elev= 14
   -10.7   20.92     -.7   20.92     -.5   21.12       0   21.12     2.6   18.72
       5   18.52     5.5   18.22       7   18.22     7.9   18.82    10.7   18.82
    13.2   20.32    17.4   20.32    18.5   19.42    28.5   19.42
#Mann= 3 , 0 , 0
   -10.7    .035       0       0    .035       0    13.2    .035       0
#XS Ineff= 2 , 0
               0   21.12    13.2           20.32
Permanent Ineff=
       F       F
Bank Sta=0,13.2
XS Rating Curve= 0
Exp/Cntr=.3,.1

Type RM Length L Ch R = 1 ,100.00  ,50,50,50
BEGIN DESCRIPTION:
2
END DESCRIPTION:
#Sta/Elev= 14
   -10.7   20.39     -.7   20.39     -.5   20.59       0   20.59     2.6   18.19
       5   17.09     5.5   17.79       7   17.79     7.9    18.2    10.7   18.29
    13.2   19.79    17.4   19.79    18.5   18.89    28.5   18.89
#Mann= 3 , 0 , 0
   -10.7    .035       0       0    .035       0    13.2    .035       0
#XS Ineff= 2 , 0
       0       0   20.59    13.2       0   19.79
Permanent Ineff=
       F       F
Bank Sta=0,13.2
XS Rating Curve= 0
Exp/Cntr=.3,.1

Type RM Length L Ch R = 1 ,50.00   ,50,50,50
BEGIN DESCRIPTION:
1
END DESCRIPTION:
#Sta/Elev= 11
     -10   20.52       0   20.52       3   18.62       5   18.22     6.6   17.22
     9.1   17.22    12.9   17.62    16.4   19.62    20.6   19.62    22.4   18.02
    32.4   18.02
#Mann= 3 , 0 , 0
     -10    .035       0       0    .035       0    16.4    .035       0
#XS Ineff= 2 , 0
       0       0   20.52    16.4       0   19.62
Permanent Ineff=
       F       F
Bank Sta=0,16.4
XS Rating Curve= 0
Exp/Cntr=.3,.1

Type RM Length L Ch R = 1 ,0.00    ,0,0,0
BEGIN DESCRIPTION:
0
END DESCRIPTION:
#Sta/Elev= 11
     -10   19.96       0   19.96       3   18.06       5   17.66     6.6   16.66
     9.1   16.66      12   17.06    16.4   19.46    20.6   19.46    22.4   17.86
    32.4   17.86
#Mann= 3 , 0 , 0
     -10    .035       0       0    .035       0    16.4    .035       0
#XS Ineff= 2 , 0
       0       0   19.96    16.4       0   19.46
Permanent Ineff=
       F       F
Bank Sta=0,16.4
XS Rating Curve= 0
Exp/Cntr=.3,.1

Chan Stop Cuts=-1