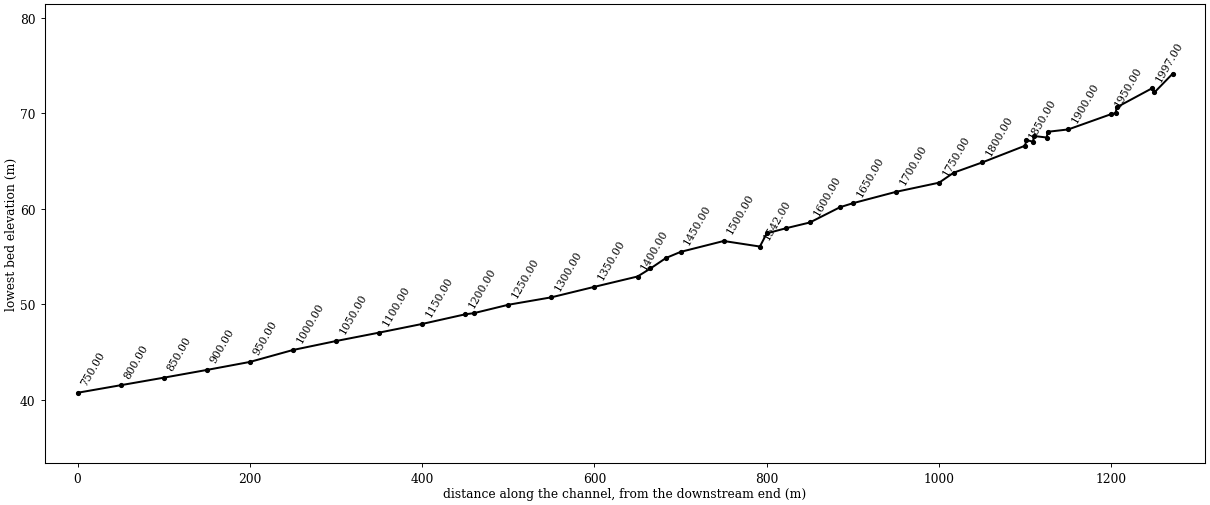
--- sahun-chun.prj (project) ---

Proj Title=sahun-chun
Current Plan=p01
Default Exp/Contr=.3,.1
SI Units
Geom File=g01
Flow File=f01
Plan File=p01
Y Axis Title=Elevation
X Axis Title(PF)=Main Channel Distance
X Axis Title(XS)=Station
BEGIN DESCRIPTION:
           BACK WATER COMPUTATION
      APPLICATION OF HEC-2 BY Samju Construction Engineering
      sahun-chun : 10,20,30,50,80 yr
END DESCRIPTION:
DSS Export Rating Curves= 0
DSS Export Rating Curve Sorted= 0
DSS Export Volume Flow Curves= 0
DXF OffsetX= 0
DXF OffsetY= 0
DXF ScaleX= 1
DXF ScaleY= 10

--- sahun-chun.p01 (plan) ---

Plan Title=Imported Plan 01
Version=Version 3.0.1  Mar 2001
Short Identifier=Imported Pla
Geom File=g01
Flow File=f01
Subcritical Flow
K Sum by GR= 0
Std Step Tol= 0.003
Critical Tol= 0.003
Num of Std Step Trials= 20
Max Error Tol= 0.1
Flow Tol Ratio= 0.001
Split Flow NTrial= 30
Split Flow Tol= 0.02
Split Flow Ratio= 0.02
Log Output Level= 0
Friction Slope Method= 1
Unsteady Friction Slope Method= 2
Parabolic Critical Depth
Global Vel Dist= 0 , 0 , 0
Global Log Level= 0
CheckData=True
Encroach Param=-1 ,0,0, 0
Computation Interval=1HOUR
Output Interval=1HOUR
Run HTab= 0
Run UNet= 0
Run PostProcess= 0
UNET Theta= 1
UNET ZTol= 0.02
UNET ZSATol= 0.1
UNET MxIter= 20
UNET MaxInSteps= 20
UNET DtIC= 0
UNET DtMin= 0
UNET MaxCRTS= 20
UNET WFStab= 2
UNET SFStab= 1
UNET WFX= 1
UNET SFX= 1
UNET Convert EG Bridges=-1
UNET Use Existing IB Tables=-1
Instantaneous Interval=1HOUR
Write IC File= 0
Write Velocity= 0
Write Detailed= 0

--- sahun-chun.f01 (steady flow) ---

Flow Title=Imported Flow 01
Version=Version 3.0.1  Mar 2001
Number of Profiles= 5
Profile Names=10YR,20YR,30YR,50YR,80YR
River Rch & RM=RIVER-1,Reach-1         ,2021.00
   33.63   37.05   39.05   41.56   43.88
River Rch & RM=RIVER-1,Reach-1         ,1000.00
   40.07   44.16   46.55   49.57   52.34
Boundary for River Rch & Prof#=RIVER-1,Reach-1         , 1
Up Type= 0
Dn Type= 3
Dn Slope=.063
Boundary for River Rch & Prof#=RIVER-1,Reach-1         , 2
Up Type= 0
Dn Type= 3
Dn Slope=.063
Boundary for River Rch & Prof#=RIVER-1,Reach-1         , 3
Up Type= 0
Dn Type= 3
Dn Slope=.063
Boundary for River Rch & Prof#=RIVER-1,Reach-1         , 4
Up Type= 0
Dn Type= 3
Dn Slope=.063
Boundary for River Rch & Prof#=RIVER-1,Reach-1         , 5
Up Type= 0
Dn Type= 3
Dn Slope=.063
DSS Import GetInterval= 0
DSS Import GetPeak= 0
DSS Import FillOption= 0

--- sahun-chun.g01 (geometry) ---

Geom Title=Imported Geom 01
Version=Version 3.0.1  Mar 2001

River Reach=RIVER-1         ,Reach-1
Reach XY= 2
              .5             .95              .5             .05

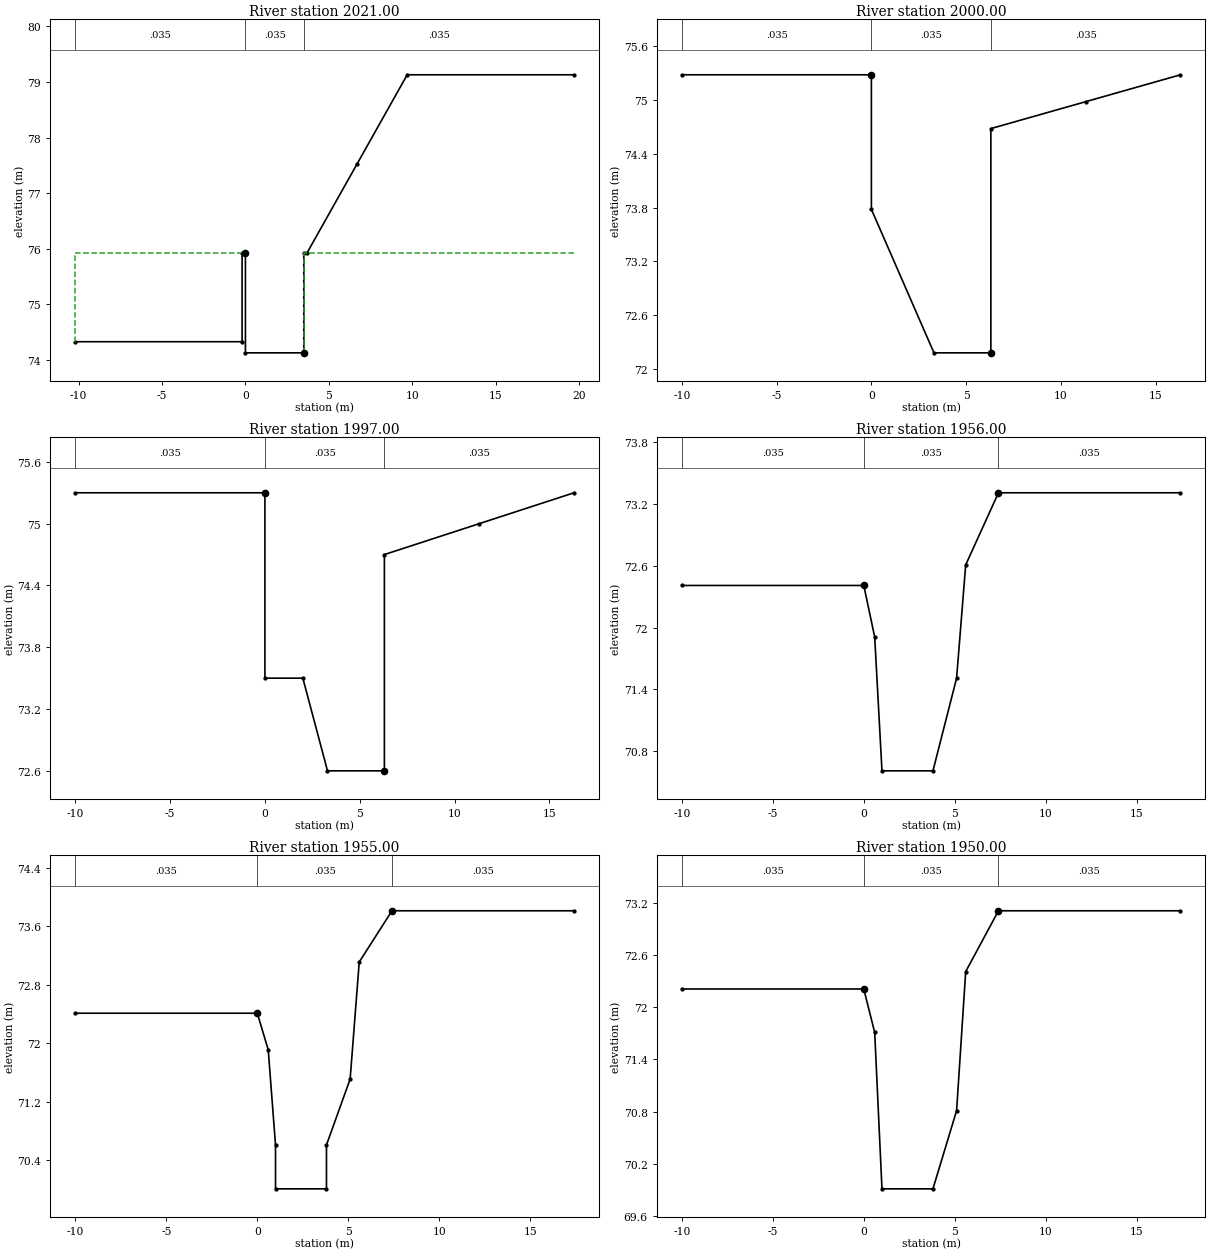
Type RM Length L Ch R = 1 ,2021.00 ,21,21,21
BEGIN DESCRIPTION:
40.021
END DESCRIPTION:
#Sta/Elev= 11
   -10.2   74.33     -.2   74.33     -.2   75.93       0   75.93       0   74.13
     3.5   74.13     3.5   75.93     3.7   75.93     6.7   77.53     9.7   79.13
    19.7   79.13
#Mann= 3 , 0 , 0
   -10.2    .035       0       0    .035       0     3.5    .035       0
#XS Ineff= 2 , 0
               0   75.93     3.5           75.93
Permanent Ineff=
       F       F
Bank Sta=0,3.5
XS Rating Curve= 0
Exp/Cntr=.3,.1

Type RM Length L Ch R = 1 ,2000.00 ,3,3,3
BEGIN DESCRIPTION:
40
END DESCRIPTION:
#Sta/Elev= 8
     -10   75.28       0   75.28       0   73.78     3.3   72.18     6.3   72.18
     6.3   74.68    11.3   74.98    16.3   75.28
#Mann= 3 , 0 , 0
     -10    .035       0       0    .035       0     6.3    .035       0
#XS Ineff= 2 , 0
       0       0   75.28     6.3       0   72.18
Permanent Ineff=
       F       F
Bank Sta=0,6.3
XS Rating Curve= 0
Exp/Cntr=.3,.1

Type RM Length L Ch R = 1 ,1997.00 ,41,41,41
BEGIN DESCRIPTION:
39.047
END DESCRIPTION:
#Sta/Elev= 9
     -10    75.3       0    75.3       0    73.5       2    73.5     3.3    72.6
     6.3    72.6     6.3    74.7    11.3      75    16.3    75.3
#Mann= 3 , 0 , 0
     -10    .035       0       0    .035       0     6.3    .035       0
#XS Ineff= 2 , 0
       0       0    75.3     6.3       0    72.6
Permanent Ineff=
       F       F
Bank Sta=0,6.3
XS Rating Curve= 0
Exp/Cntr=.3,.1

Type RM Length L Ch R = 1 ,1956.00 ,1,1,1
BEGIN DESCRIPTION:
39.006
END DESCRIPTION:
#Sta/Elev= 9
     -10   72.41       0   72.41      .6   71.91       1   70.61     3.8   70.61
     5.1   71.51     5.6   72.61     7.4   73.31    17.4   73.31
#Mann= 3 , 0 , 0
     -10    .035       0       0    .035       0     7.4    .035       0
#XS Ineff= 2 , 0
               0   72.41     7.4           73.31
Permanent Ineff=
       F       F
Bank Sta=0,7.4
XS Rating Curve= 0
Exp/Cntr=.3,.1

Type RM Length L Ch R = 1 ,1955.00 ,5,5,5
BEGIN DESCRIPTION:
39.005
END DESCRIPTION:
#Sta/Elev= 11
     -10   72.41       0   72.41      .6   71.91       1   70.61       1   70.01
     3.8   70.01     3.8   70.61     5.1   71.51     5.6   73.11     7.4   73.81
    17.4   73.81
#Mann= 3 , 0 , 0
     -10    .035       0       0    .035       0     7.4    .035       0
#XS Ineff= 2 , 0
               0   72.41     7.4           73.81
Permanent Ineff=
       F       F
Bank Sta=0,7.4
XS Rating Curve= 0
Exp/Cntr=.3,.1

Type RM Length L Ch R = 1 ,1950.00 ,50,50,50
BEGIN DESCRIPTION:
39
END DESCRIPTION:
#Sta/Elev= 9
     -10   72.21       0   72.21      .6   71.71       1   69.91     3.8   69.91
     5.1   70.81     5.6   72.41     7.4   73.11    17.4   73.11
#Mann= 3 , 0 , 0
     -10    .035       0       0    .035       0     7.4    .035       0
#XS Ineff= 2 , 0
               0   72.21     7.4           73.11
Permanent Ineff=
       F       F
Bank Sta=0,7.4
XS Rating Curve= 0
Exp/Cntr=.3,.1

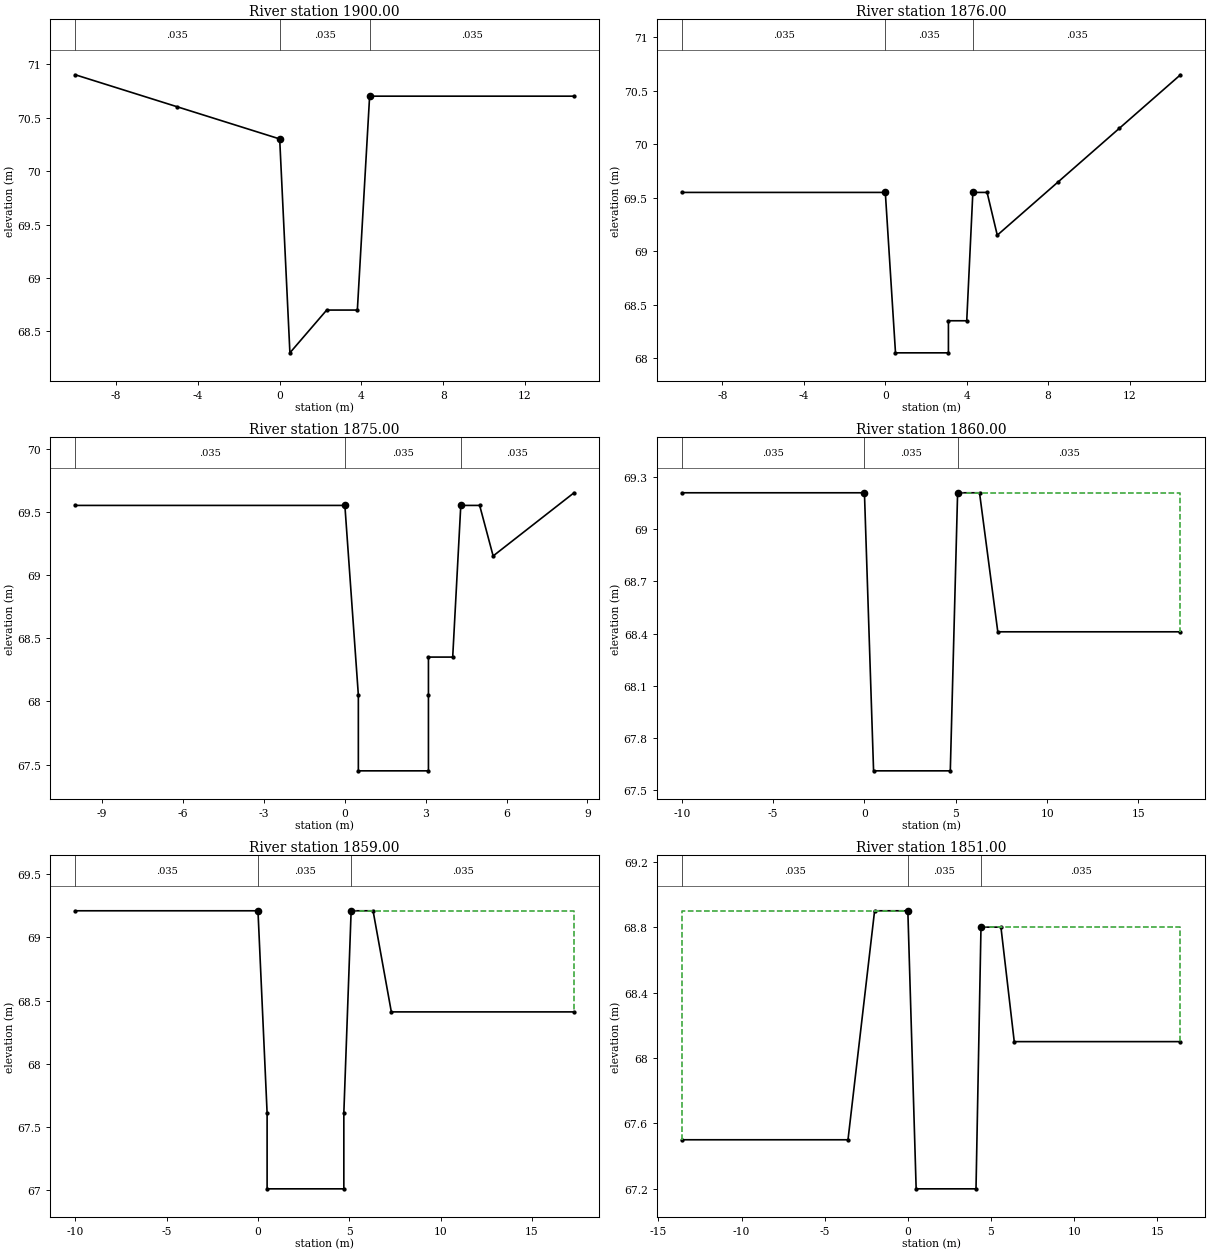
Type RM Length L Ch R = 1 ,1900.00 ,24,24,24
BEGIN DESCRIPTION:
38
END DESCRIPTION:
#Sta/Elev= 8
     -10    70.9      -5    70.6       0    70.3      .5    68.3     2.3    68.7
     3.8    68.7     4.4    70.7    14.4    70.7
#Mann= 3 , 0 , 0
     -10    .035       0       0    .035       0     4.4    .035       0
#XS Ineff= 2 , 0
               0    70.3     4.4            70.7
Permanent Ineff=
       F       F
Bank Sta=0,4.4
XS Rating Curve= 0
Exp/Cntr=.3,.1

Type RM Length L Ch R = 1 ,1876.00 ,1,1,1
BEGIN DESCRIPTION:
37.026
END DESCRIPTION:
#Sta/Elev= 12
     -10   69.55       0   69.55      .5   68.05     3.1   68.05     3.1   68.35
       4   68.35     4.3   69.55       5   69.55     5.5   69.15     8.5   69.65
    11.5   70.15    14.5   70.65
#Mann= 3 , 0 , 0
     -10    .035       0       0    .035       0     4.3    .035       0
#XS Ineff= 2 , 0
               0   69.55     4.3           69.55
Permanent Ineff=
       F       F
Bank Sta=0,4.3
XS Rating Curve= 0
Exp/Cntr=.3,.1

Type RM Length L Ch R = 1 ,1875.00 ,15,15,15
BEGIN DESCRIPTION:
37.025
END DESCRIPTION:
#Sta/Elev= 12
     -10   69.55       0   69.55      .5   68.05      .5   67.45     3.1   67.45
     3.1   68.05     3.1   68.35       4   68.35     4.3   69.55       5   69.55
     5.5   69.15     8.5   69.65
#Mann= 3 , 0 , 0
     -10    .035       0       0    .035       0     4.3    .035       0
#XS Ineff= 2 , 0
               0   69.55     4.3           69.55
Permanent Ineff=
       F       F
Bank Sta=0,4.3
XS Rating Curve= 0
Exp/Cntr=.3,.1

Type RM Length L Ch R = 1 ,1860.00 ,1,1,1
BEGIN DESCRIPTION:
37.01
END DESCRIPTION:
#Sta/Elev= 8
     -10   69.21       0   69.21      .5   67.61     4.7   67.61     5.1   69.21
     6.3   69.21     7.3   68.41    17.3   68.41
#Mann= 3 , 0 , 0
     -10    .035       0       0    .035       0     5.1    .035       0
#XS Ineff= 2 , 0
               0   69.21     5.1           69.21
Permanent Ineff=
       F       F
Bank Sta=0,5.1
XS Rating Curve= 0
Exp/Cntr=.3,.1

Type RM Length L Ch R = 1 ,1859.00 ,8,8,8
BEGIN DESCRIPTION:
37.009
END DESCRIPTION:
#Sta/Elev= 10
     -10   69.21       0   69.21      .5   67.61      .5   67.01     4.7   67.01
     4.7   67.61     5.1   69.21     6.3   69.21     7.3   68.41    17.3   68.41
#Mann= 3 , 0 , 0
     -10    .035       0       0    .035       0     5.1    .035       0
#XS Ineff= 2 , 0
               0   69.21     5.1           69.21
Permanent Ineff=
       F       F
Bank Sta=0,5.1
XS Rating Curve= 0
Exp/Cntr=.3,.1

Type RM Length L Ch R = 1 ,1851.00 ,1,1,1
BEGIN DESCRIPTION:
37.001
END DESCRIPTION:
#Sta/Elev= 10
   -13.6    67.5    -3.6    67.5      -2    68.9       0    68.9      .5    67.2
     4.1    67.2     4.4    68.8     5.6    68.8     6.4    68.1    16.4    68.1
#Mann= 3 , 0 , 0
   -13.6    .035       0       0    .035       0     4.4    .035       0
#XS Ineff= 2 , 0
               0    68.9     4.4            68.8
Permanent Ineff=
       F       F
Bank Sta=0,4.4
XS Rating Curve= 0
Exp/Cntr=.3,.1

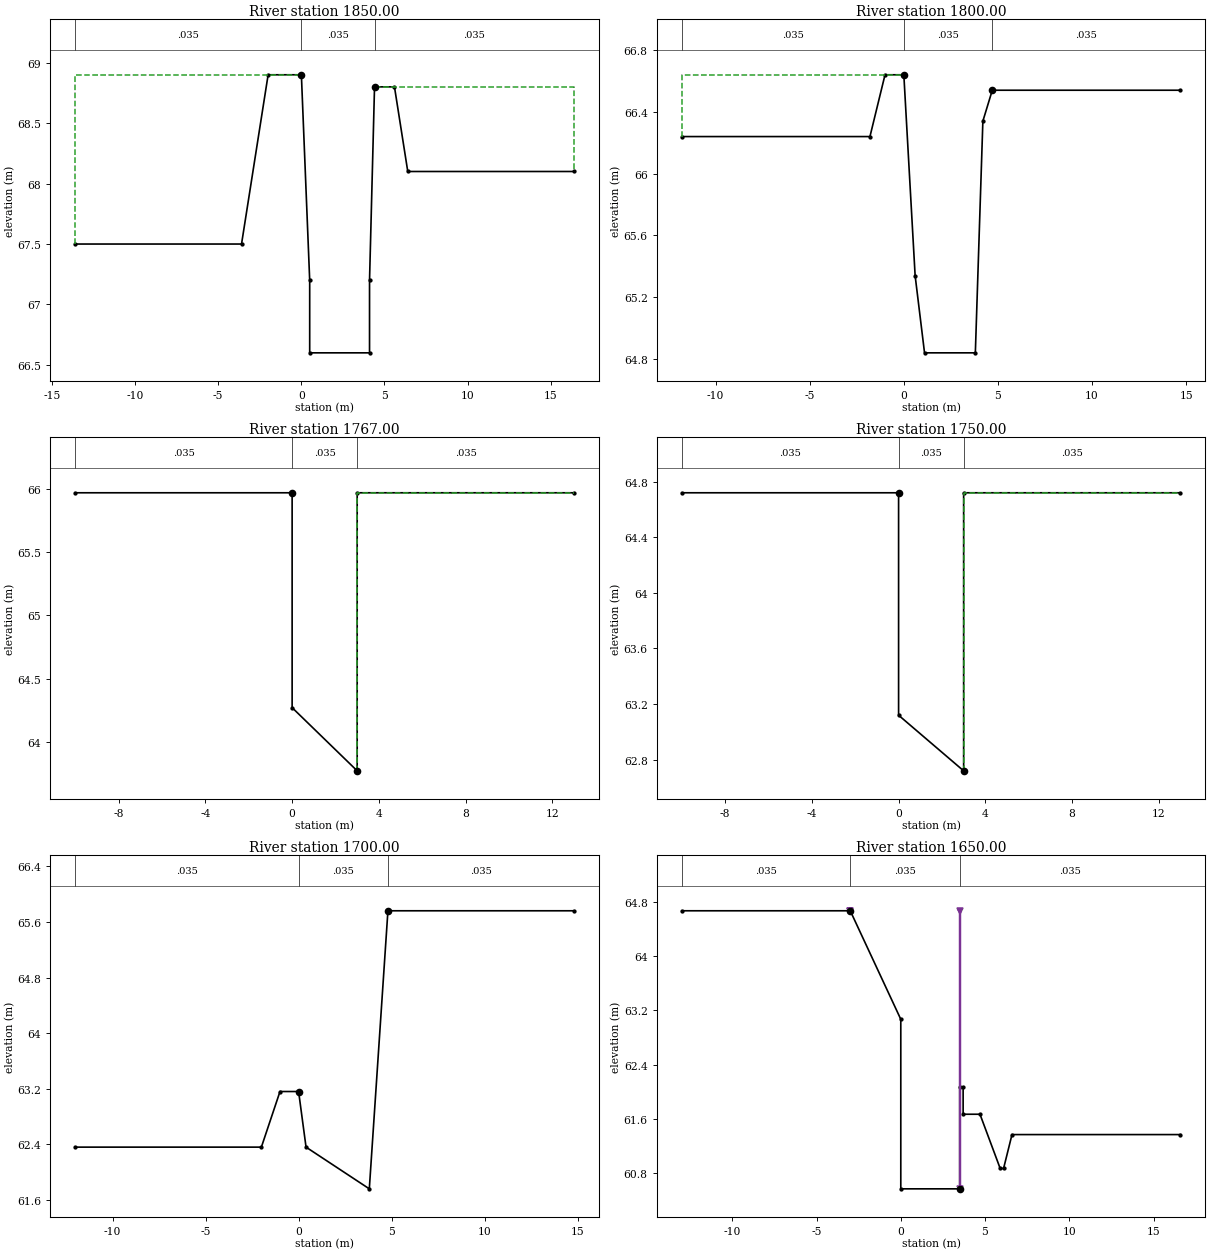
Type RM Length L Ch R = 1 ,1850.00 ,50,50,50
BEGIN DESCRIPTION:
37
END DESCRIPTION:
#Sta/Elev= 12
   -13.6    67.5    -3.6    67.5      -2    68.9       0    68.9      .5    67.2
      .5    66.6     4.1    66.6     4.1    67.2     4.4    68.8     5.6    68.8
     6.4    68.1    16.4    68.1
#Mann= 3 , 0 , 0
   -13.6    .035       0       0    .035       0     4.4    .035       0
#XS Ineff= 2 , 0
               0    68.9     4.4            68.8
Permanent Ineff=
       F       F
Bank Sta=0,4.4
XS Rating Curve= 0
Exp/Cntr=.3,.1

Type RM Length L Ch R = 1 ,1800.00 ,33,33,33
BEGIN DESCRIPTION:
36
END DESCRIPTION:
#Sta/Elev= 10
   -11.8   66.24    -1.8   66.24      -1   66.64       0   66.64      .6   65.34
     1.1   64.84     3.8   64.84     4.2   66.34     4.7   66.54    14.7   66.54
#Mann= 3 , 0 , 0
   -11.8    .035       0       0    .035       0     4.7    .035       0
#XS Ineff= 2 , 0
               0   66.64     4.7           66.54
Permanent Ineff=
       F       F
Bank Sta=0,4.7
XS Rating Curve= 0
Exp/Cntr=.3,.1

Type RM Length L Ch R = 1 ,1767.00 ,17,17,17
BEGIN DESCRIPTION:
35.017
END DESCRIPTION:
#Sta/Elev= 6
     -10   65.97       0   65.97       0   64.27       3   63.77       3   65.97
      13   65.97
#Mann= 3 , 0 , 0
     -10    .035       0       0    .035       0       3    .035       0
#XS Ineff= 2 , 0
               0   65.97       3           65.97
Permanent Ineff=
       F       F
Bank Sta=0,3
XS Rating Curve= 0
Exp/Cntr=.3,.1

Type RM Length L Ch R = 1 ,1750.00 ,50,50,50
BEGIN DESCRIPTION:
35
END DESCRIPTION:
#Sta/Elev= 6
     -10   64.72       0   64.72       0   63.12       3   62.72       3   64.72
      13   64.72
#Mann= 3 , 0 , 0
     -10    .035       0       0    .035       0       3    .035       0
#XS Ineff= 2 , 0
               0   64.72       3           64.72
Permanent Ineff=
       F       F
Bank Sta=0,3
XS Rating Curve= 0
Exp/Cntr=.3,.1

Type RM Length L Ch R = 1 ,1700.00 ,50,50,50
BEGIN DESCRIPTION:
34
END DESCRIPTION:
#Sta/Elev= 8
     -12   62.36      -2   62.36      -1   63.16       0   63.16      .4   62.36
     3.8   61.76     4.8   65.76    14.8   65.76
#Mann= 3 , 0 , 0
     -12    .035       0       0    .035       0     4.8    .035       0
#XS Ineff= 2 , 0
       0       0   63.16     4.8       0   65.76
Permanent Ineff=
       F       F
Bank Sta=0,4.8
XS Rating Curve= 0
Exp/Cntr=.3,.1

Type RM Length L Ch R = 1 ,1650.00 ,15,15,15
BEGIN DESCRIPTION:
33
END DESCRIPTION:
#Sta/Elev= 13
     -13   64.67      -3   64.67       0   63.07       0   60.57     3.5   60.57
     3.5   62.07     3.7   62.07     3.7   61.67     4.7   61.67     5.9   60.87
     6.1   60.87     6.6   61.37    16.6   61.37
#Mann= 3 , 0 , 0
     -13    .035       0      -3    .035       0     3.5    .035       0
Levee=-1,-3,64.67,-1,3.5,64.67,,
Bank Sta=-3,3.5
XS Rating Curve= 0
Exp/Cntr=.3,.1

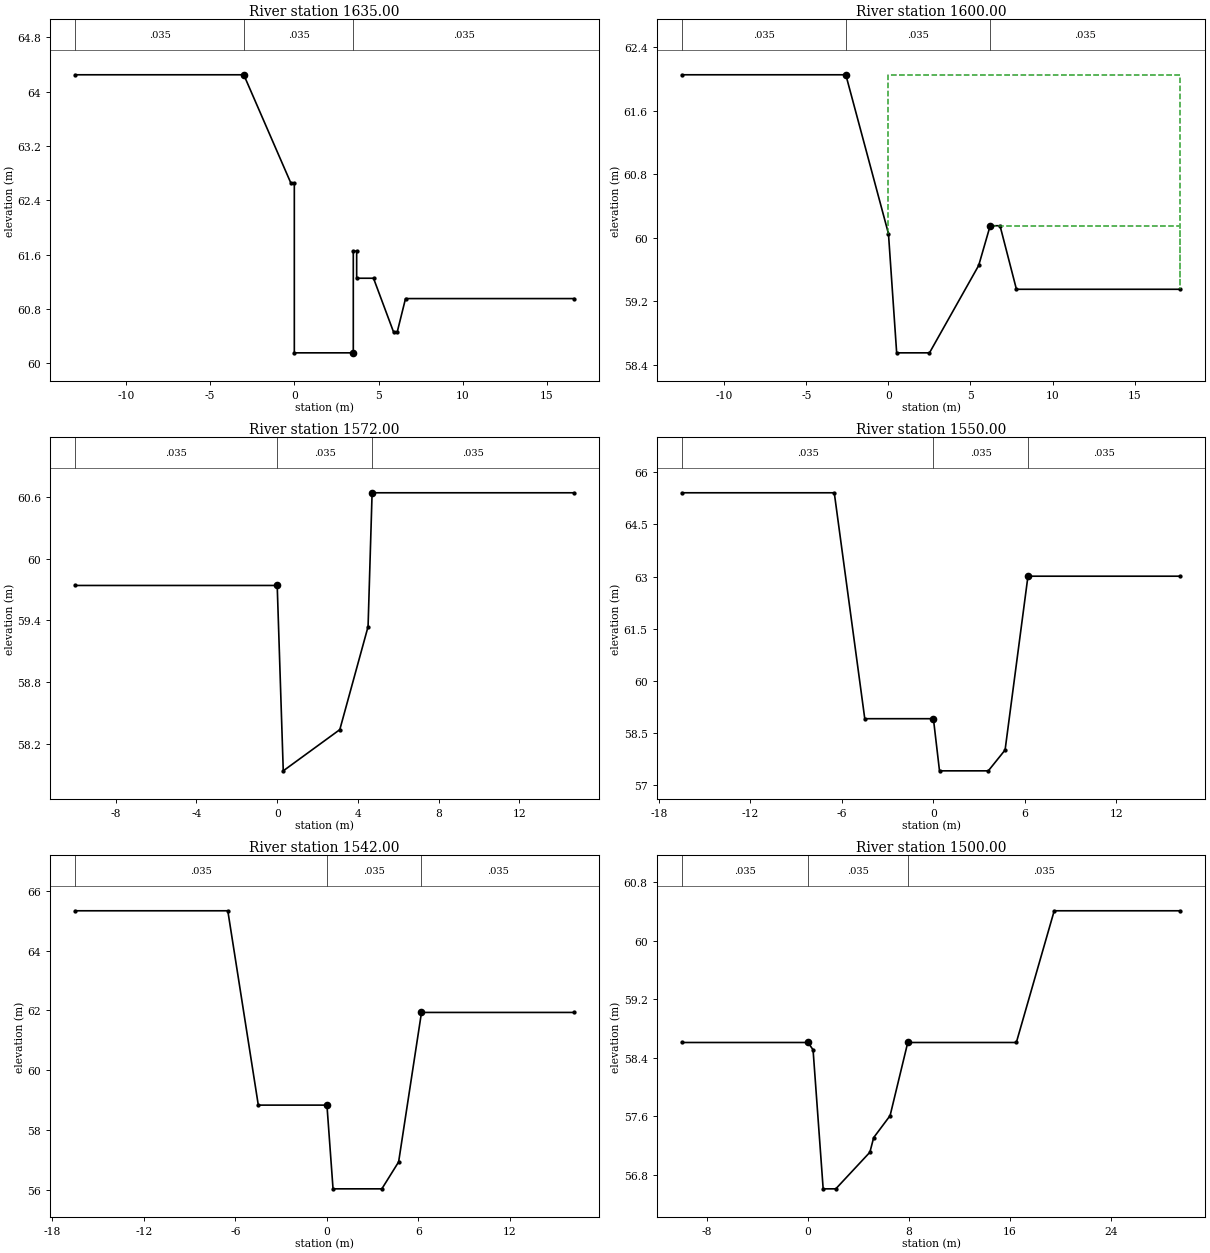
Type RM Length L Ch R = 1 ,1635.00 ,35,35,35
BEGIN DESCRIPTION:
32.035
END DESCRIPTION:
#Sta/Elev= 14
     -13   64.25      -3   64.25     -.2   62.65       0   62.65       0   60.15
     3.5   60.15     3.5   61.65     3.7   61.65     3.7   61.25     4.7   61.25
     5.9   60.45     6.1   60.45     6.6   60.95    16.6   60.95
#Mann= 3 , 0 , 0
     -13    .035       0      -3    .035       0     3.5    .035       0
Bank Sta=-3,3.5
XS Rating Curve= 0
Exp/Cntr=.3,.1

Type RM Length L Ch R = 1 ,1600.00 ,28,28,28
BEGIN DESCRIPTION:
32
END DESCRIPTION:
#Sta/Elev= 10
   -12.6   62.05    -2.6   62.05       0   60.05      .5   58.55     2.5   58.55
     5.5   59.65     6.2   60.15     6.8   60.15     7.8   59.35    17.8   59.35
#Mann= 3 , 0 , 0
   -12.6    .035       0    -2.6    .035       0     6.2    .035       0
#XS Ineff= 2 , 0
       0    -2.6   62.05     6.2       0   60.15
Permanent Ineff=
       F       F
Bank Sta=-2.6,6.2
XS Rating Curve= 0
Exp/Cntr=.3,.1

Type RM Length L Ch R = 1 ,1572.00 ,22,22,22
BEGIN DESCRIPTION:
31.022
END DESCRIPTION:
#Sta/Elev= 7
     -10   59.74       0   59.74      .3   57.94     3.1   58.34     4.5   59.34
     4.7   60.64    14.7   60.64
#Mann= 3 , 0 , 0
     -10    .035       0       0    .035       0     4.7    .035       0
#XS Ineff= 2 , 0
       0       0   59.74     4.7       0   60.64
Permanent Ineff=
       F       F
Bank Sta=0,4.7
XS Rating Curve= 0
Exp/Cntr=.3,.1

Type RM Length L Ch R = 1 ,1550.00 ,8,8,8
BEGIN DESCRIPTION:
31
END DESCRIPTION:
#Sta/Elev= 9
   -16.5   65.41    -6.5   65.41    -4.5   58.91       0   58.91      .4   57.41
     3.6   57.41     4.7   58.01     6.2   63.01    16.2   63.01
#Mann= 3 , 0 , 0
   -16.5    .035       0       0    .035       0     6.2    .035       0
#XS Ineff= 2 , 0
       0       0   58.91     6.2       0   63.01
Permanent Ineff=
       F       F
Bank Sta=0,6.2
XS Rating Curve= 0
Exp/Cntr=.3,.1

Type RM Length L Ch R = 1 ,1542.00 ,42,42,42
BEGIN DESCRIPTION:
30.042
END DESCRIPTION:
#Sta/Elev= 9
   -16.5   65.33    -6.5   65.33    -4.5   58.83       0   58.83      .4   56.03
     3.6   56.03     4.7   56.93     6.2   61.93    16.2   61.93
#Mann= 3 , 0 , 0
   -16.5    .035       0       0    .035       0     6.2    .035       0
#XS Ineff= 2 , 0
               0   58.83     6.2           61.93
Permanent Ineff=
       F       F
Bank Sta=0,6.2
XS Rating Curve= 0
Exp/Cntr=.3,.1

Type RM Length L Ch R = 1 ,1500.00 ,50,50,50
BEGIN DESCRIPTION:
30
END DESCRIPTION:
#Sta/Elev= 12
     -10   58.61       0   58.61      .4   58.51     1.2   56.61     2.2   56.61
     4.9   57.11     5.2   57.31     6.5   57.61     7.9   58.61    16.5   58.61
    19.5   60.41    29.5   60.41
#Mann= 3 , 0 , 0
     -10    .035       0       0    .035       0     7.9    .035       0
#XS Ineff= 2 , 0
               0   58.61     7.9           58.61
Permanent Ineff=
       F       F
Bank Sta=0,7.9
XS Rating Curve= 0
Exp/Cntr=.3,.1

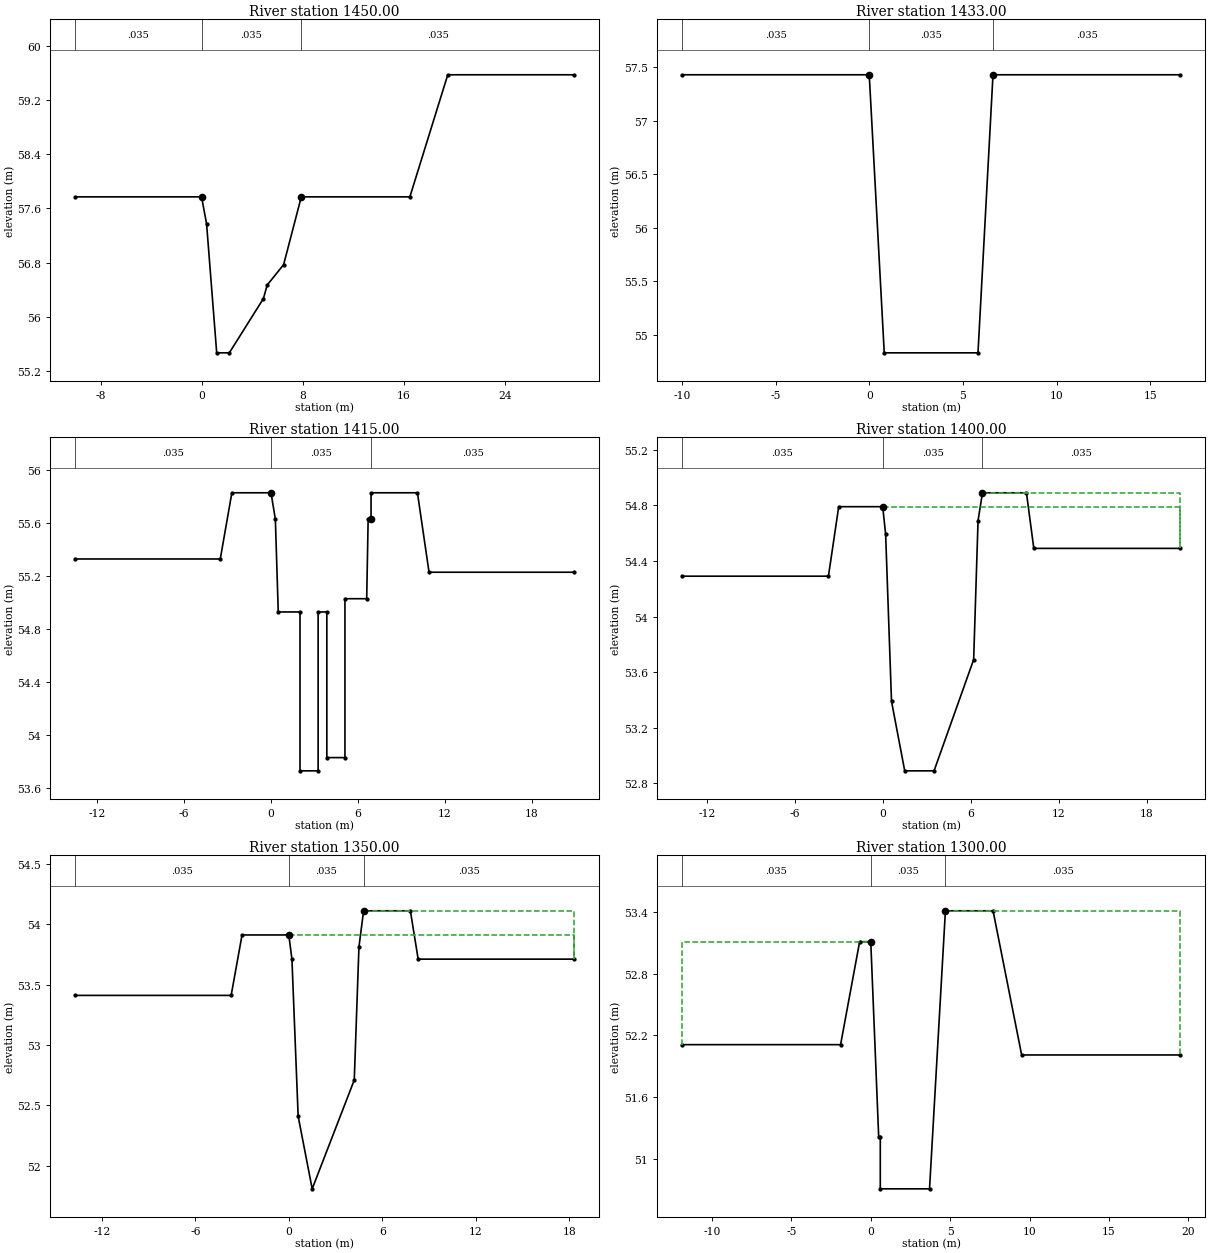
Type RM Length L Ch R = 1 ,1450.00 ,17,17,17
BEGIN DESCRIPTION:
29
END DESCRIPTION:
#Sta/Elev= 12
     -10   57.77       0   57.77      .4   57.37     1.2   55.47     2.2   55.47
     4.9   56.27     5.2   56.47     6.5   56.77     7.9   57.77    16.5   57.77
    19.5   59.57    29.5   59.57
#Mann= 3 , 0 , 0
     -10    .035       0       0    .035       0     7.9    .035       0
#XS Ineff= 2 , 0
               0   57.77     7.9           57.77
Permanent Ineff=
       F       F
Bank Sta=0,7.9
XS Rating Curve= 0
Exp/Cntr=.3,.1

Type RM Length L Ch R = 1 ,1433.00 ,18,18,18
BEGIN DESCRIPTION:
28.033
END DESCRIPTION:
#Sta/Elev= 6
     -10   57.43       0   57.43      .8   54.83     5.8   54.83     6.6   57.43
    16.6   57.43
#Mann= 3 , 0 , 0
     -10    .035       0       0    .035       0     6.6    .035       0
#XS Ineff= 2 , 0
               0   57.43     6.6           57.43
Permanent Ineff=
       F       F
Bank Sta=0,6.6
XS Rating Curve= 0
Exp/Cntr=.3,.1

Type RM Length L Ch R = 1 ,1415.00 ,15,15,15
BEGIN DESCRIPTION:
28.015
END DESCRIPTION:
#Sta/Elev= 21
   -13.5   55.33    -3.5   55.33    -2.7   55.83       0   55.83      .3   55.63
      .5   54.93       2   54.93       2   53.73    3.25   53.73    3.25   54.93
    3.85   54.93    3.85   53.83     5.1   53.83     5.1   55.03     6.6   55.03
     6.7   55.63     6.9   55.63     6.9   55.83    10.1   55.83    10.9   55.23
    20.9   55.23
#Mann= 3 , 0 , 0
   -13.5    .035       0       0    .035       0     6.9    .035       0
Bank Sta=0,6.9
XS Rating Curve= 0
Exp/Cntr=.3,.1

Type RM Length L Ch R = 1 ,1400.00 ,50,50,50
BEGIN DESCRIPTION:
28
END DESCRIPTION:
#Sta/Elev= 14
   -13.7   54.29    -3.7   54.29      -3   54.79       0   54.79      .2   54.59
      .6   53.39     1.5   52.89     3.5   52.89     6.2   53.69     6.5   54.69
     6.8   54.89     9.8   54.89    10.3   54.49    20.3   54.49
#Mann= 3 , 0 , 0
   -13.7    .035       0       0    .035       0     6.8    .035       0
#XS Ineff= 2 , 0
       0       0   54.79     6.8       0   54.89
Permanent Ineff=
       F       F
Bank Sta=0,6.8
XS Rating Curve= 0
Exp/Cntr=.3,.1

Type RM Length L Ch R = 1 ,1350.00 ,50,50,50
BEGIN DESCRIPTION:
27
END DESCRIPTION:
#Sta/Elev= 13
   -13.7   53.41    -3.7   53.41      -3   53.91       0   53.91      .2   53.71
      .6   52.41     1.5   51.81     4.2   52.71     4.5   53.81     4.8   54.11
     7.8   54.11     8.3   53.71    18.3   53.71
#Mann= 3 , 0 , 0
   -13.7    .035       0       0    .035       0     4.8    .035       0
#XS Ineff= 2 , 0
       0       0   53.91     4.8       0   54.11
Permanent Ineff=
       F       F
Bank Sta=0,4.8
XS Rating Curve= 0
Exp/Cntr=.3,.1

Type RM Length L Ch R = 1 ,1300.00 ,50,50,50
BEGIN DESCRIPTION:
26
END DESCRIPTION:
#Sta/Elev= 12
   -11.9   52.11    -1.9   52.11     -.7   53.11       0   53.11      .5   51.21
      .6   51.21      .6   50.71     3.7   50.71     4.7   53.41     7.7   53.41
     9.5   52.01    19.5   52.01
#Mann= 3 , 0 , 0
   -11.9    .035       0       0    .035       0     4.7    .035       0
#XS Ineff= 2 , 0
               0   53.11     4.7           53.41
Permanent Ineff=
       F       F
Bank Sta=0,4.7
XS Rating Curve= 0
Exp/Cntr=.3,.1

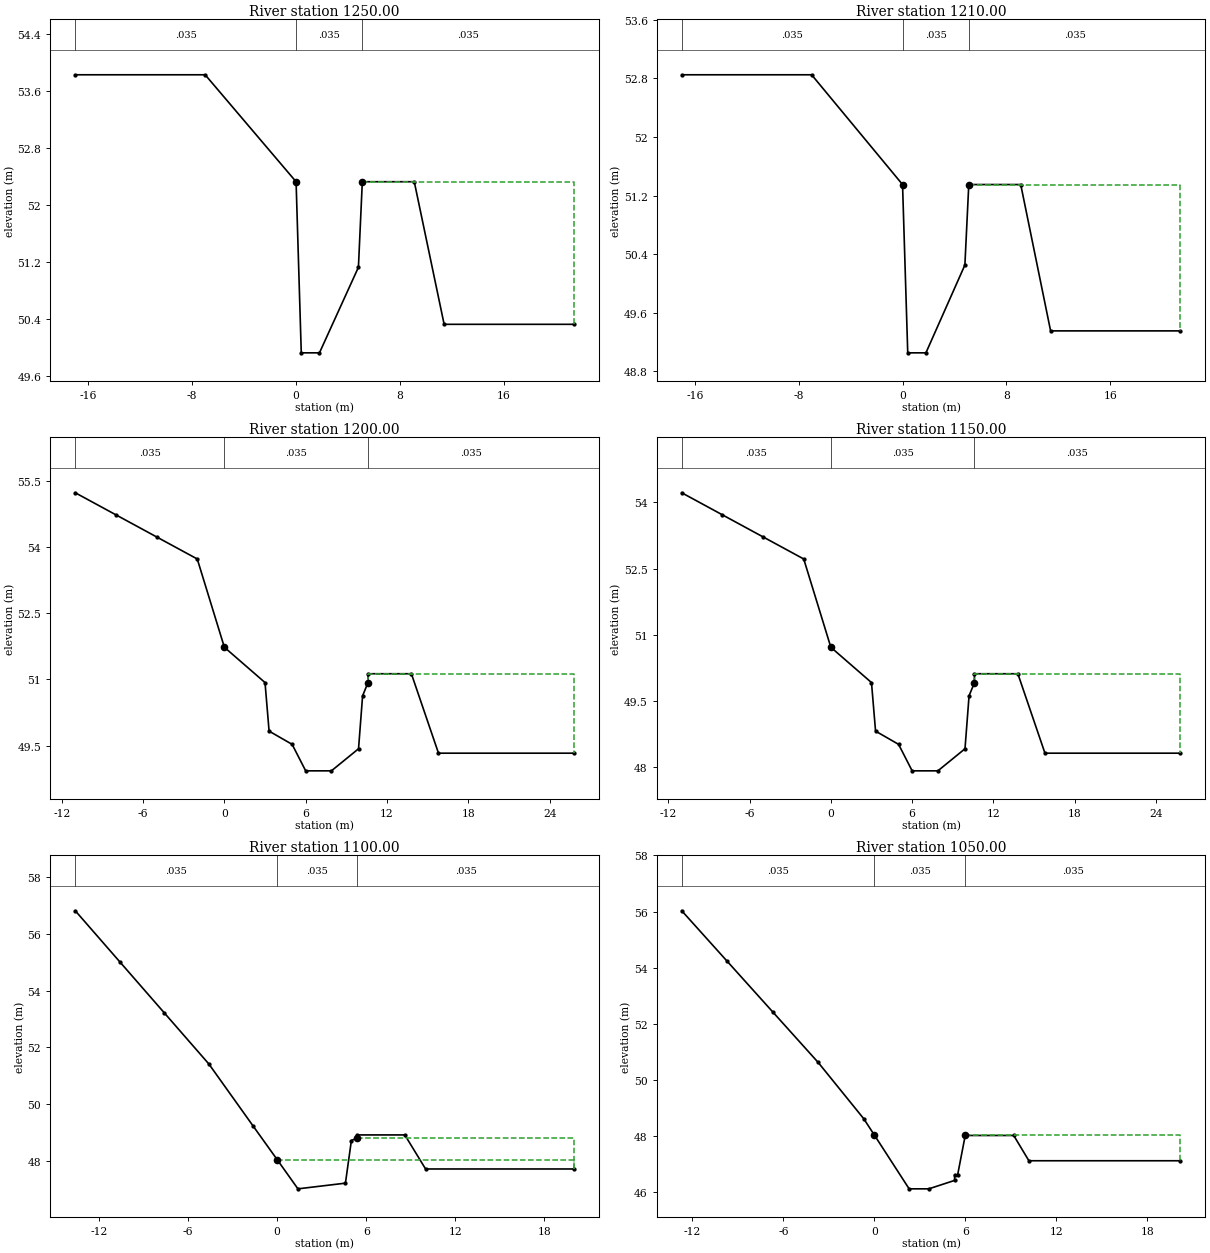
Type RM Length L Ch R = 1 ,1250.00 ,40,40,40
BEGIN DESCRIPTION:
25
END DESCRIPTION:
#Sta/Elev= 10
     -17   53.83      -7   53.83       0   52.33      .4   49.93     1.8   49.93
     4.8   51.13     5.1   52.33     9.1   52.33    11.4   50.33    21.4   50.33
#Mann= 3 , 0 , 0
     -17    .035       0       0    .035       0     5.1    .035       0
#XS Ineff= 2 , 0
               0   52.33     5.1           52.33
Permanent Ineff=
       F       F
Bank Sta=0,5.1
XS Rating Curve= 0
Exp/Cntr=.3,.1

Type RM Length L Ch R = 1 ,1210.00 ,10,10,10
BEGIN DESCRIPTION:
24.01
END DESCRIPTION:
#Sta/Elev= 10
     -17   52.85      -7   52.85       0   51.35      .4   49.05     1.8   49.05
     4.8   50.25     5.1   51.35     9.1   51.35    11.4   49.35    21.4   49.35
#Mann= 3 , 0 , 0
     -17    .035       0       0    .035       0     5.1    .035       0
#XS Ineff= 2 , 0
               0   51.35     5.1           51.35
Permanent Ineff=
       F       F
Bank Sta=0,5.1
XS Rating Curve= 0
Exp/Cntr=.3,.1

Type RM Length L Ch R = 1 ,1200.00 ,50,50,50
BEGIN DESCRIPTION:
24
END DESCRIPTION:
#Sta/Elev= 17
     -11   55.23      -8   54.73      -5   54.23      -2   53.73       0   51.73
       3   50.93     3.3   49.83       5   49.53       6   48.93     7.9   48.93
     9.9   49.43    10.2   50.63    10.6   50.93    10.6   51.13    13.8   51.13
    15.8   49.33    25.8   49.33
#Mann= 3 , 0 , 0
     -11    .035       0       0    .035       0    10.6    .035       0
#XS Ineff= 2 , 0
               0   51.73    10.6           51.13
Permanent Ineff=
       F       F
Bank Sta=0,10.6
XS Rating Curve= 0
Exp/Cntr=.3,.1

Type RM Length L Ch R = 1 ,1150.00 ,50,50,50
BEGIN DESCRIPTION:
23
END DESCRIPTION:
#Sta/Elev= 17
     -11   54.22      -8   53.72      -5   53.22      -2   52.72       0   50.72
       3   49.92     3.3   48.82       5   48.52       6   47.92     7.9   47.92
     9.9   48.42    10.2   49.62    10.6   49.92    10.6   50.12    13.8   50.12
    15.8   48.32    25.8   48.32
#Mann= 3 , 0 , 0
     -11    .035       0       0    .035       0    10.6    .035       0
#XS Ineff= 2 , 0
               0   50.72    10.6           50.12
Permanent Ineff=
       F       F
Bank Sta=0,10.6
XS Rating Curve= 0
Exp/Cntr=.3,.1

Type RM Length L Ch R = 1 ,1100.00 ,50,50,50
BEGIN DESCRIPTION:
22
END DESCRIPTION:
#Sta/Elev= 14
   -13.6   56.81   -10.6   55.01    -7.6   53.21    -4.6   51.41    -1.6   49.21
       0   48.04     1.4   47.01     4.6   47.21       5   48.71     5.4   48.81
     5.4   48.91     8.6   48.91      10   47.71      20   47.71
#Mann= 3 , 0 , 0
   -13.6    .035       0       0    .035       0     5.4    .035       0
#XS Ineff= 2 , 0
       0       0   48.04     5.4       0   48.81
Permanent Ineff=
       F       F
Bank Sta=0,5.4
XS Rating Curve= 0
Exp/Cntr=.3,.1

Type RM Length L Ch R = 1 ,1050.00 ,50,50,50
BEGIN DESCRIPTION:
21
END DESCRIPTION:
#Sta/Elev= 15
   -12.7   56.03    -9.7   54.23    -6.7   52.43    -3.7   50.63     -.7   48.63
       0   48.05     2.3   46.13     3.6   46.13     5.3   46.43     5.3   46.63
     5.5   46.63       6   48.03     9.2   48.03    10.2   47.13    20.2   47.13
#Mann= 3 , 0 , 0
   -12.7    .035       0       0    .035       0       6    .035       0
#XS Ineff= 2 , 0
               0   48.05       6           48.03
Permanent Ineff=
       F       F
Bank Sta=0,6
XS Rating Curve= 0
Exp/Cntr=.3,.1

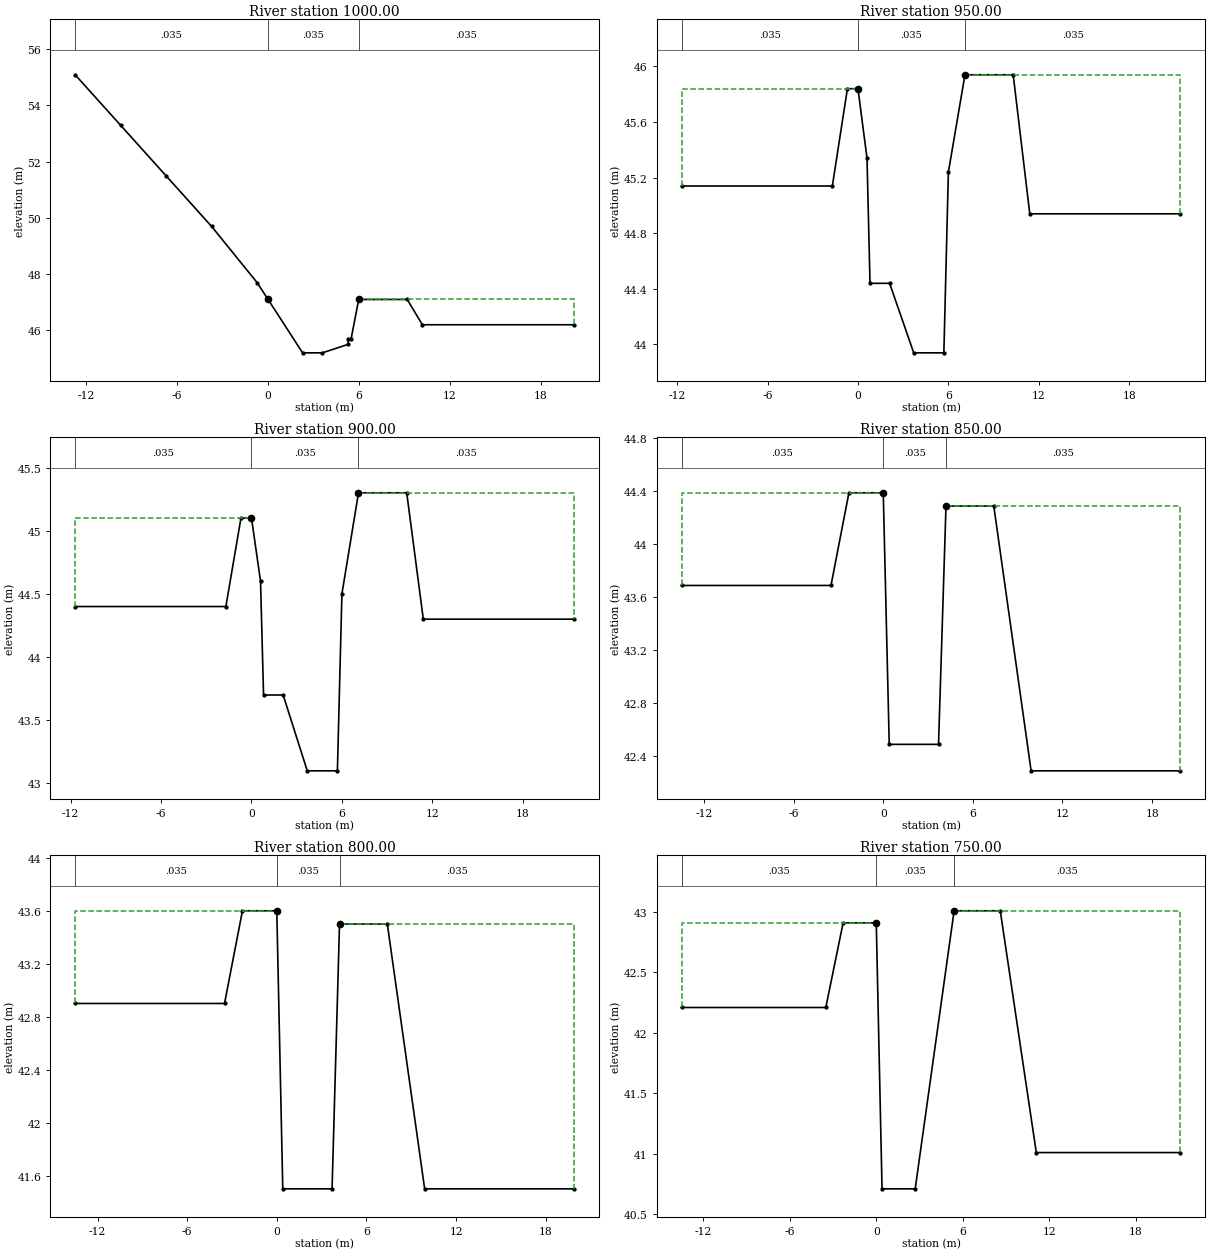
Type RM Length L Ch R = 1 ,1000.00 ,50,50,50
BEGIN DESCRIPTION:
20
END DESCRIPTION:
#Sta/Elev= 15
   -12.7   55.09    -9.7   53.29    -6.7   51.49    -3.7   49.69     -.7   47.69
       0   47.11     2.3   45.19     3.6   45.19     5.3   45.49     5.3   45.69
     5.5   45.69       6   47.09     9.2   47.09    10.2   46.19    20.2   46.19
#Mann= 3 , 0 , 0
   -12.7    .035       0       0    .035       0       6    .035       0
#XS Ineff= 2 , 0
               0   47.11       6           47.09
Permanent Ineff=
       F       F
Bank Sta=0,6
XS Rating Curve= 0
Exp/Cntr=.3,.1

Type RM Length L Ch R = 1 ,950.00  ,50,50,50
BEGIN DESCRIPTION:
19
END DESCRIPTION:
#Sta/Elev= 14
   -11.7   45.14    -1.7   45.14     -.7   45.84       0   45.84      .6   45.34
      .8   44.44     2.1   44.44     3.7   43.94     5.7   43.94       6   45.24
     7.1   45.94    10.3   45.94    11.4   44.94    21.4   44.94
#Mann= 3 , 0 , 0
   -11.7    .035       0       0    .035       0     7.1    .035       0
#XS Ineff= 2 , 0
               0   45.84     7.1           45.94
Permanent Ineff=
       F       F
Bank Sta=0,7.1
XS Rating Curve= 0
Exp/Cntr=.3,.1

Type RM Length L Ch R = 1 ,900.00  ,50,50,50
BEGIN DESCRIPTION:
18
END DESCRIPTION:
#Sta/Elev= 14
   -11.7    44.4    -1.7    44.4     -.7    45.1       0    45.1      .6    44.6
      .8    43.7     2.1    43.7     3.7    43.1     5.7    43.1       6    44.5
     7.1    45.3    10.3    45.3    11.4    44.3    21.4    44.3
#Mann= 3 , 0 , 0
   -11.7    .035       0       0    .035       0     7.1    .035       0
#XS Ineff= 2 , 0
               0    45.1     7.1            45.3
Permanent Ineff=
       F       F
Bank Sta=0,7.1
XS Rating Curve= 0
Exp/Cntr=.3,.1

Type RM Length L Ch R = 1 ,850.00  ,50,50,50
BEGIN DESCRIPTION:
17
END DESCRIPTION:
#Sta/Elev= 10
   -13.5   43.69    -3.5   43.69    -2.3   44.39       0   44.39      .4   42.49
     3.7   42.49     4.2   44.29     7.4   44.29     9.9   42.29    19.9   42.29
#Mann= 3 , 0 , 0
   -13.5    .035       0       0    .035       0     4.2    .035       0
#XS Ineff= 2 , 0
               0   44.39     4.2           44.29
Permanent Ineff=
       F       F
Bank Sta=0,4.2
XS Rating Curve= 0
Exp/Cntr=.3,.1

Type RM Length L Ch R = 1 ,800.00  ,50,50,50
BEGIN DESCRIPTION:
16
END DESCRIPTION:
#Sta/Elev= 10
   -13.5    42.9    -3.5    42.9    -2.3    43.6       0    43.6      .4    41.5
     3.7    41.5     4.2    43.5     7.4    43.5     9.9    41.5    19.9    41.5
#Mann= 3 , 0 , 0
   -13.5    .035       0       0    .035       0     4.2    .035       0
#XS Ineff= 2 , 0
               0    43.6     4.2            43.5
Permanent Ineff=
       F       F
Bank Sta=0,4.2
XS Rating Curve= 0
Exp/Cntr=.3,.1

Type RM Length L Ch R = 1 ,750.00  ,50,50,50
BEGIN DESCRIPTION:
15
END DESCRIPTION:
#Sta/Elev= 10
   -13.5   42.21    -3.5   42.21    -2.3   42.91       0   42.91      .4   40.71
     2.7   40.71     5.4   43.01     8.6   43.01    11.1   41.01    21.1   41.01
#Mann= 3 , 0 , 0
   -13.5    .035       0       0    .035       0     5.4    .035       0
#XS Ineff= 2 , 0
               0   42.91     5.4           43.01
Permanent Ineff=
       F       F
Bank Sta=0,5.4
XS Rating Curve= 0
Exp/Cntr=.3,.1