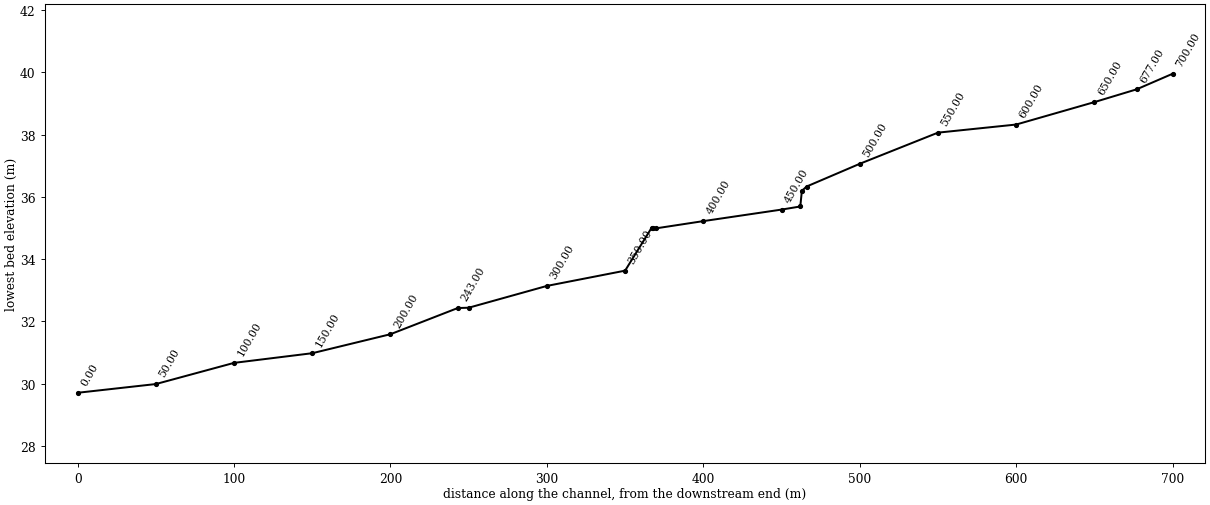
HEC-RAS study sahun-chun.prj: sahun-chun

--- sahun-chun.g01 (geometry) --- (continued)

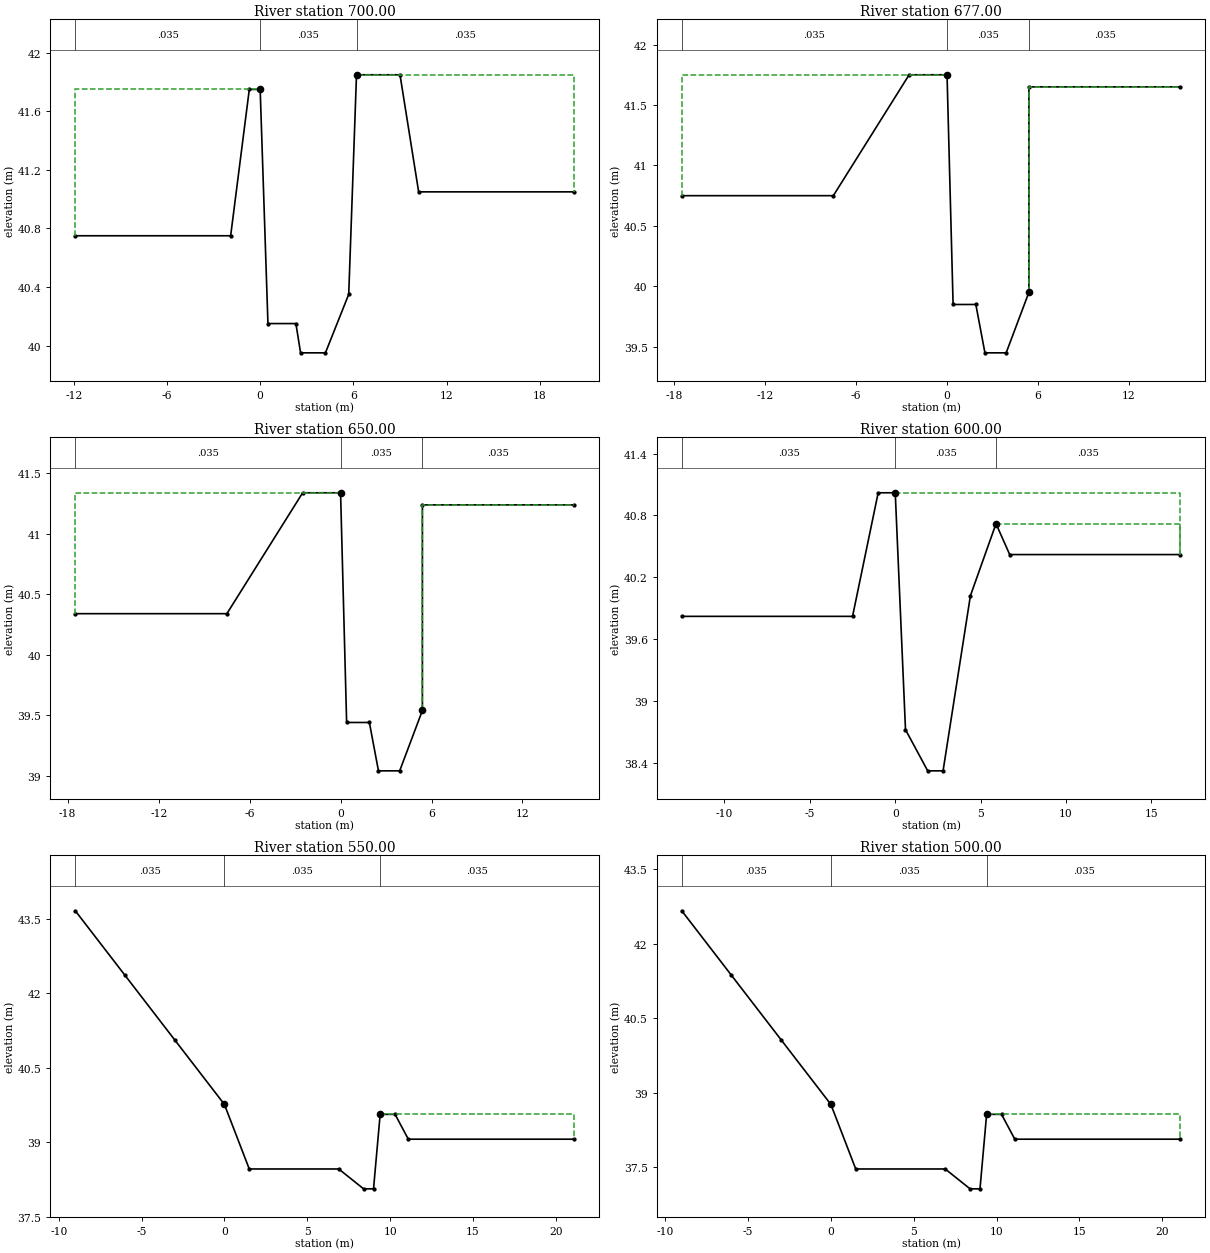
Type RM Length L Ch R = 1 ,700.00  ,23,23,23
BEGIN DESCRIPTION:
14
END DESCRIPTION:
#Sta/Elev= 13
   -11.9   40.75    -1.9   40.75     -.7   41.75       0   41.75      .5   40.15
     2.3   40.15     2.6   39.95     4.2   39.95     5.7   40.35     6.2   41.85
       9   41.85    10.2   41.05    20.2   41.05
#Mann= 3 , 0 , 0
   -11.9    .035       0       0    .035       0     6.2    .035       0
#XS Ineff= 2 , 0
               0   41.75     6.2           41.85
Permanent Ineff=
       F       F
Bank Sta=0,6.2
XS Rating Curve= 0
Exp/Cntr=.3,.1

Type RM Length L Ch R = 1 ,677.00  ,27,27,27
BEGIN DESCRIPTION:
13.027
END DESCRIPTION:
#Sta/Elev= 11
   -17.5   40.75    -7.5   40.75    -2.5   41.75       0   41.75      .4   39.85
     1.9   39.85     2.5   39.45     3.9   39.45     5.4   39.95     5.4   41.65
    15.4   41.65
#Mann= 3 , 0 , 0
   -17.5    .035       0       0    .035       0     5.4    .035       0
#XS Ineff= 2 , 0
               0   41.75     5.4           41.65
Permanent Ineff=
       F       F
Bank Sta=0,5.4
XS Rating Curve= 0
Exp/Cntr=.3,.1

Type RM Length L Ch R = 1 ,650.00  ,50,50,50
BEGIN DESCRIPTION:
13
END DESCRIPTION:
#Sta/Elev= 11
   -17.5   40.34    -7.5   40.34    -2.5   41.34       0   41.34      .4   39.44
     1.9   39.44     2.5   39.04     3.9   39.04     5.4   39.54     5.4   41.24
    15.4   41.24
#Mann= 3 , 0 , 0
   -17.5    .035       0       0    .035       0     5.4    .035       0
#XS Ineff= 2 , 0
               0   41.34     5.4           41.24
Permanent Ineff=
       F       F
Bank Sta=0,5.4
XS Rating Curve= 0
Exp/Cntr=.3,.1

Type RM Length L Ch R = 1 ,600.00  ,50,50,50
BEGIN DESCRIPTION:
12
END DESCRIPTION:
#Sta/Elev= 11
   -12.5   39.82    -2.5   39.82      -1   41.02       0   41.02      .6   38.72
     1.9   38.32     2.8   38.32     4.4   40.02     5.9   40.72     6.7   40.42
    16.7   40.42
#Mann= 3 , 0 , 0
   -12.5    .035       0       0    .035       0     5.9    .035       0
#XS Ineff= 2 , 0
       0       0   41.02     5.9       0   40.72
Permanent Ineff=
       F       F
Bank Sta=0,5.9
XS Rating Curve= 0
Exp/Cntr=.3,.1

Type RM Length L Ch R = 1 ,550.00  ,50,50,50
BEGIN DESCRIPTION:
11
END DESCRIPTION:
#Sta/Elev= 12
      -9   43.66      -6   42.36      -3   41.06       0   39.76     1.5   38.46
     6.9   38.46     8.4   38.06       9   38.06     9.4   39.56    10.3   39.56
    11.1   39.06    21.1   39.06
#Mann= 3 , 0 , 0
      -9    .035       0       0    .035       0     9.4    .035       0
#XS Ineff= 2 , 0
               0   39.76     9.4           39.56
Permanent Ineff=
       F       F
Bank Sta=0,9.4
XS Rating Curve= 0
Exp/Cntr=.3,.1

Type RM Length L Ch R = 1 ,500.00  ,34,34,34
BEGIN DESCRIPTION:
10
END DESCRIPTION:
#Sta/Elev= 12
      -9   42.66      -6   41.36      -3   40.06       0   38.76     1.5   37.46
     6.9   37.46     8.4   37.06       9   37.06     9.4   38.56    10.3   38.56
    11.1   38.06    21.1   38.06
#Mann= 3 , 0 , 0
      -9    .035       0       0    .035       0     9.4    .035       0
#XS Ineff= 2 , 0
               0   38.76     9.4           38.56
Permanent Ineff=
       F       F
Bank Sta=0,9.4
XS Rating Curve= 0
Exp/Cntr=.3,.1

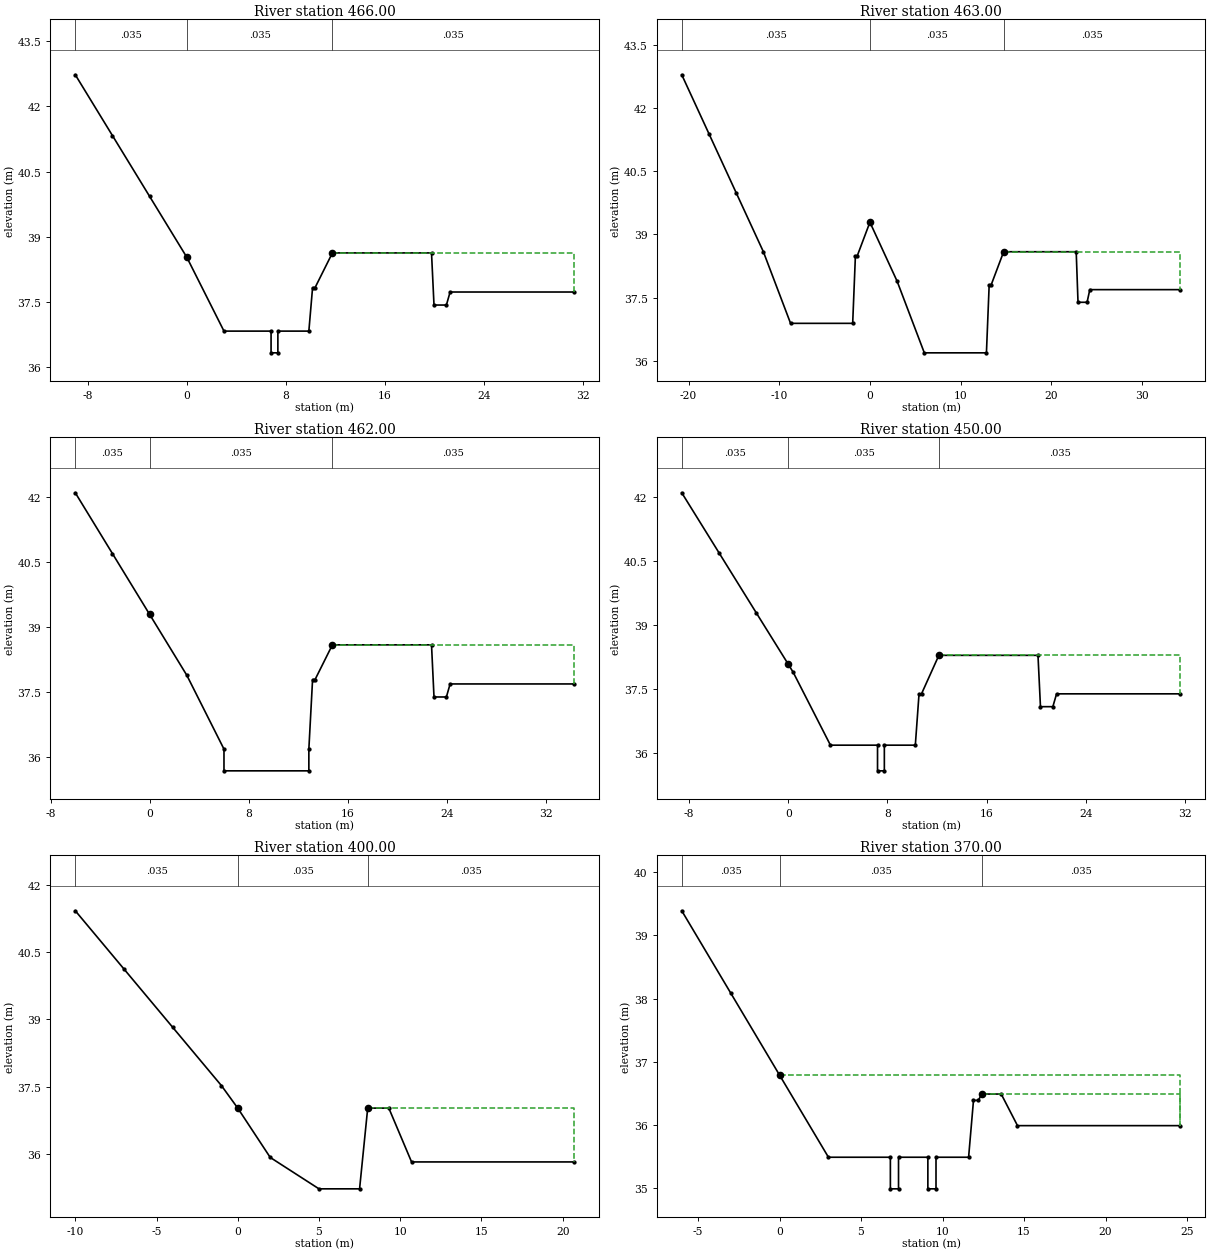
Type RM Length L Ch R = 1 ,466.00  ,3,3,3
BEGIN DESCRIPTION:
9.016
END DESCRIPTION:
#Sta/Elev= 18
      -9   42.73      -6   41.33      -3   39.93       0   38.53       3   36.83
     6.8   36.83     6.8   36.33    7.35   36.33    7.35   36.83    9.85   36.83
   10.15   37.83   10.35   37.83   11.75   38.63   19.75   38.63   19.95   37.43
   20.95   37.43   21.25   37.73   31.25   37.73
#Mann= 3 , 0 , 0
      -9    .035       0       0    .035       0   11.75    .035       0
#XS Ineff= 2 , 0
               0   38.53   11.75           38.63
Permanent Ineff=
       F       F
Bank Sta=0,11.75
XS Rating Curve= 0
Exp/Cntr=.3,.1

Type RM Length L Ch R = 1 ,463.00  ,1,1,1
BEGIN DESCRIPTION:
9.013
END DESCRIPTION:
#Sta/Elev= 20
  -20.75   42.79  -17.75   41.39  -14.75   39.99  -11.75   38.59   -8.75   36.89
    -1.9   36.89    -1.6   38.49    -1.4   38.49       0   39.29       3   37.89
       6   36.19   12.85   36.19   13.15   37.79   13.35   37.79   14.75   38.59
   22.75   38.59   22.95   37.39   23.95   37.39   24.25   37.69   34.25   37.69
#Mann= 3 , 0 , 0
  -20.75    .035       0       0    .035       0   14.75    .035       0
#XS Ineff= 2 , 0
               0   39.29   14.75           38.59
Permanent Ineff=
       F       F
Bank Sta=0,14.75
XS Rating Curve= 0
Exp/Cntr=.3,.1

Type RM Length L Ch R = 1 ,462.00  ,12,12,12
BEGIN DESCRIPTION:
9.012
END DESCRIPTION:
#Sta/Elev= 16
      -6   42.09      -3   40.69       0   39.29       3   37.89       6   36.19
       6   35.69   12.85   35.69   12.85   36.19   13.15   37.79   13.35   37.79
   14.75   38.59   22.75   38.59   22.95   37.39   23.95   37.39   24.25   37.69
   34.25   37.69
#Mann= 3 , 0 , 0
      -6    .035       0       0    .035       0   14.75    .035       0
#XS Ineff= 2 , 0
               0   39.29   14.75           38.59
Permanent Ineff=
       F       F
Bank Sta=0,14.75
XS Rating Curve= 0
Exp/Cntr=.3,.1

Type RM Length L Ch R = 1 ,450.00  ,50,50,50
BEGIN DESCRIPTION:
9
END DESCRIPTION:
#Sta/Elev= 19
    -8.6   42.09    -5.6   40.69    -2.6   39.29       0   38.08      .4   37.89
     3.4   36.19     7.2   36.19     7.2   35.59    7.75   35.59    7.75   36.19
   10.25   36.19   10.55   37.39   10.75   37.39   12.15   38.29   20.15   38.29
   20.35   37.09   21.35   37.09   21.65   37.39   31.65   37.39
#Mann= 3 , 0 , 0
    -8.6    .035       0       0    .035       0   12.15    .035       0
#XS Ineff= 2 , 0
               0   38.08   12.15           38.29
Permanent Ineff=
       F       F
Bank Sta=0,12.15
XS Rating Curve= 0
Exp/Cntr=.3,.1

Type RM Length L Ch R = 1 ,400.00  ,30,30,30
BEGIN DESCRIPTION:
8
END DESCRIPTION:
#Sta/Elev= 12
     -10   41.42      -7   40.12      -4   38.82      -1   37.52       0   37.02
       2   35.92       5   35.22     7.5   35.22       8   37.02     9.3   37.02
    10.7   35.82    20.7   35.82
#Mann= 3 , 0 , 0
     -10    .035       0       0    .035       0       8    .035       0
#XS Ineff= 2 , 0
               0   37.02       8           37.02
Permanent Ineff=
       F       F
Bank Sta=0,8
XS Rating Curve= 0
Exp/Cntr=.3,.1

Type RM Length L Ch R = 1 ,370.00  ,2,2,2
BEGIN DESCRIPTION:
7.02
END DESCRIPTION:
#Sta/Elev= 19
      -6   39.39      -3   38.09       0   36.79       3   35.49     6.8   35.49
     6.8   34.99     7.3   34.99     7.3   35.49     9.1   35.49     9.1   34.99
     9.6   34.99     9.6   35.49    11.6   35.49    11.9   36.39    12.2   36.39
    12.4   36.49    13.6   36.49    14.6   35.99    24.6   35.99
#Mann= 3 , 0 , 0
      -6    .035       0       0    .035       0    12.4    .035       0
#XS Ineff= 2 , 0
       0       0   36.79    12.4       0   36.49
Permanent Ineff=
       F       F
Bank Sta=0,12.4
XS Rating Curve= 0
Exp/Cntr=.3,.1

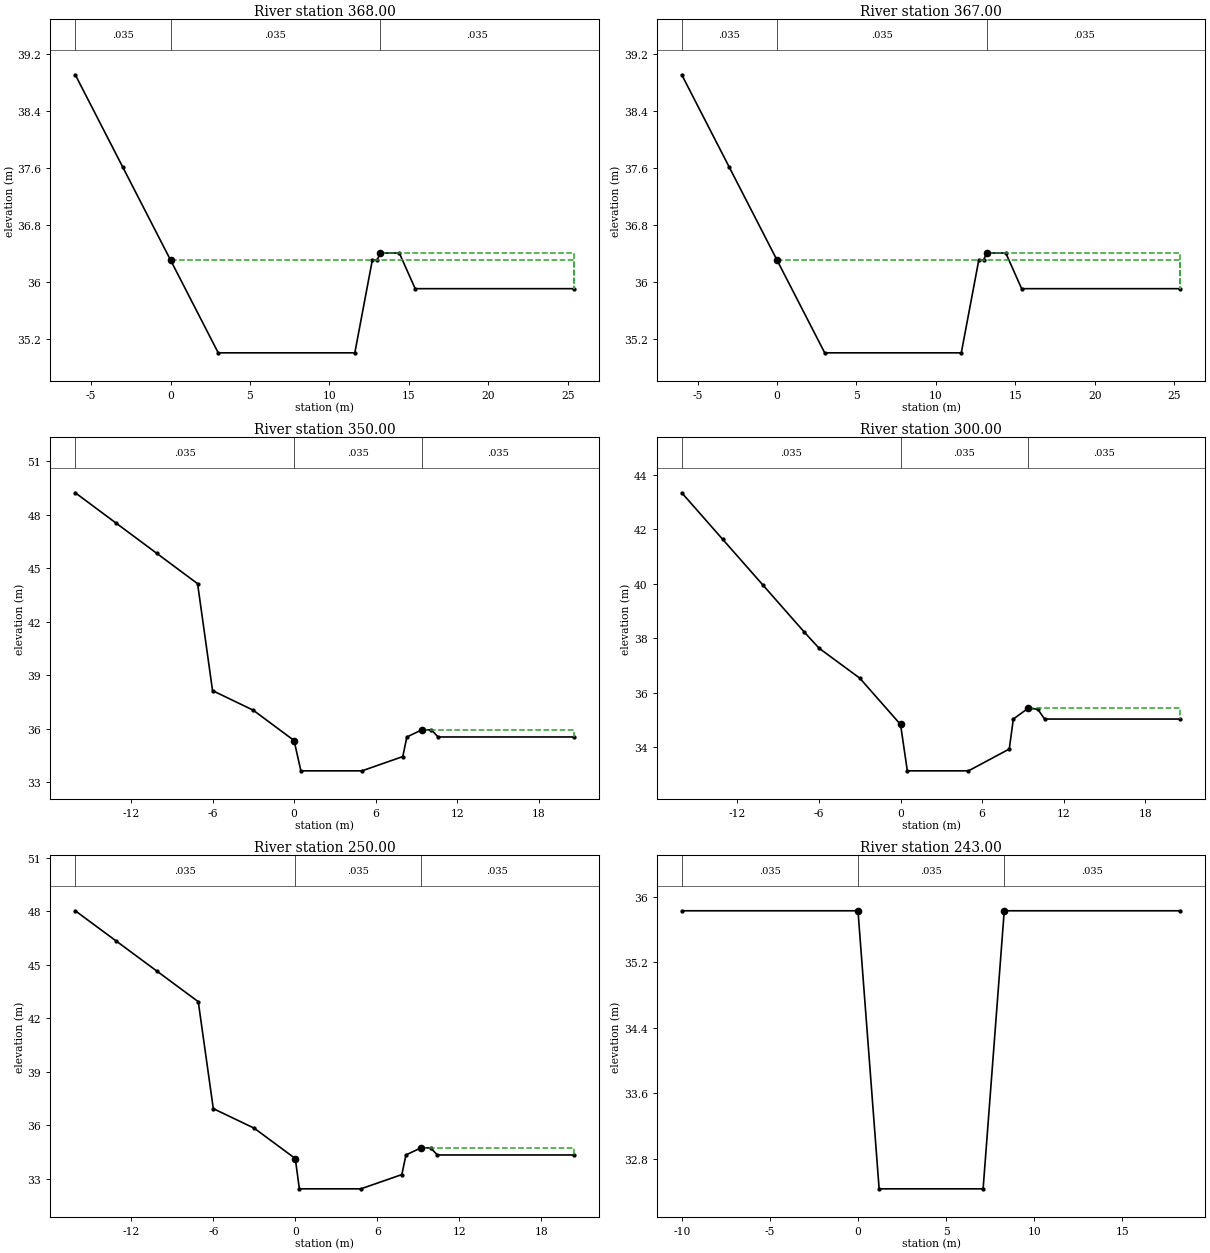
Type RM Length L Ch R = 1 ,368.00  ,1,1,1
BEGIN DESCRIPTION:
7.018
END DESCRIPTION:
#Sta/Elev= 11
      -6   38.91      -3   37.61       0   36.31       3   35.01    11.6   35.01
    12.7   36.31      13   36.31    13.2   36.41    14.4   36.41    15.4   35.91
    25.4   35.91
#Mann= 3 , 0 , 0
      -6    .035       0       0    .035       0    13.2    .035       0
#XS Ineff= 2 , 0
       0       0   36.31    13.2       0   36.41
Permanent Ineff=
       F       F
Bank Sta=0,13.2
XS Rating Curve= 0
Exp/Cntr=.3,.1

Type RM Length L Ch R = 1 ,367.00  ,17,17,17
BEGIN DESCRIPTION:
7.017
END DESCRIPTION:
#Sta/Elev= 11
      -6   38.91      -3   37.61       0   36.31       3   35.01    11.6   35.01
    12.7   36.31      13   36.31    13.2   36.41    14.4   36.41    15.4   35.91
    25.4   35.91
#Mann= 3 , 0 , 0
      -6    .035       0       0    .035       0    13.2    .035       0
#XS Ineff= 2 , 0
       0       0   36.31    13.2       0   36.41
Permanent Ineff=
       F       F
Bank Sta=0,13.2
XS Rating Curve= 0
Exp/Cntr=.3,.1

Type RM Length L Ch R = 1 ,350.00  ,50,50,50
BEGIN DESCRIPTION:
7
END DESCRIPTION:
#Sta/Elev= 15
   -16.1   49.23   -13.1   47.53   -10.1   45.83    -7.1   44.13      -6   38.13
      -3   37.03       0   35.33      .5   33.63       5   33.63       8   34.43
     8.3   35.53     9.4   35.93    10.1   35.93    10.6   35.53    20.6   35.53
#Mann= 3 , 0 , 0
   -16.1    .035       0       0    .035       0     9.4    .035       0
#XS Ineff= 2 , 0
       0       0   35.33     9.4       0   35.93
Permanent Ineff=
       F       F
Bank Sta=0,9.4
XS Rating Curve= 0
Exp/Cntr=.3,.1

Type RM Length L Ch R = 1 ,300.00  ,50,50,50
BEGIN DESCRIPTION:
6
END DESCRIPTION:
#Sta/Elev= 15
   -16.1   43.34   -13.1   41.64   -10.1   39.94    -7.1   38.24      -6   37.64
      -3   36.54       0   34.84      .5   33.14       5   33.14       8   33.94
     8.3   35.04     9.4   35.44    10.1    35.4    10.6   35.04    20.6   35.04
#Mann= 3 , 0 , 0
   -16.1    .035       0       0    .035       0     9.4    .035       0
#XS Ineff= 2 , 0
               0   34.84     9.4           35.44
Permanent Ineff=
       F       F
Bank Sta=0,9.4
XS Rating Curve= 0
Exp/Cntr=.3,.1

Type RM Length L Ch R = 1 ,250.00  ,7,7,7
BEGIN DESCRIPTION:
5
END DESCRIPTION:
#Sta/Elev= 15
   -16.1   48.04   -13.1   46.34   -10.1   44.64    -7.1   42.94      -6   36.94
      -3   35.84       0   34.14      .3   32.44     4.8   32.44     7.8   33.24
     8.1   34.34     9.2   34.74     9.9   34.74    10.4   34.34    20.4   34.34
#Mann= 3 , 0 , 0
   -16.1    .035       0       0    .035       0     9.2    .035       0
#XS Ineff= 2 , 0
               0   34.14     9.2           34.74
Permanent Ineff=
       F       F
Bank Sta=0,9.2
XS Rating Curve= 0
Exp/Cntr=.3,.1

Type RM Length L Ch R = 1 ,243.00  ,43,43,43
BEGIN DESCRIPTION:
4.043
END DESCRIPTION:
#Sta/Elev= 6
     -10   35.83       0   35.83     1.2   32.43     7.1   32.43     8.3   35.83
    18.3   35.83
#Mann= 3 , 0 , 0
     -10    .035       0       0    .035       0     8.3    .035       0
#XS Ineff= 2 , 0
               0   35.83     8.3           35.83
Permanent Ineff=
       F       F
Bank Sta=0,8.3
XS Rating Curve= 0
Exp/Cntr=.3,.1

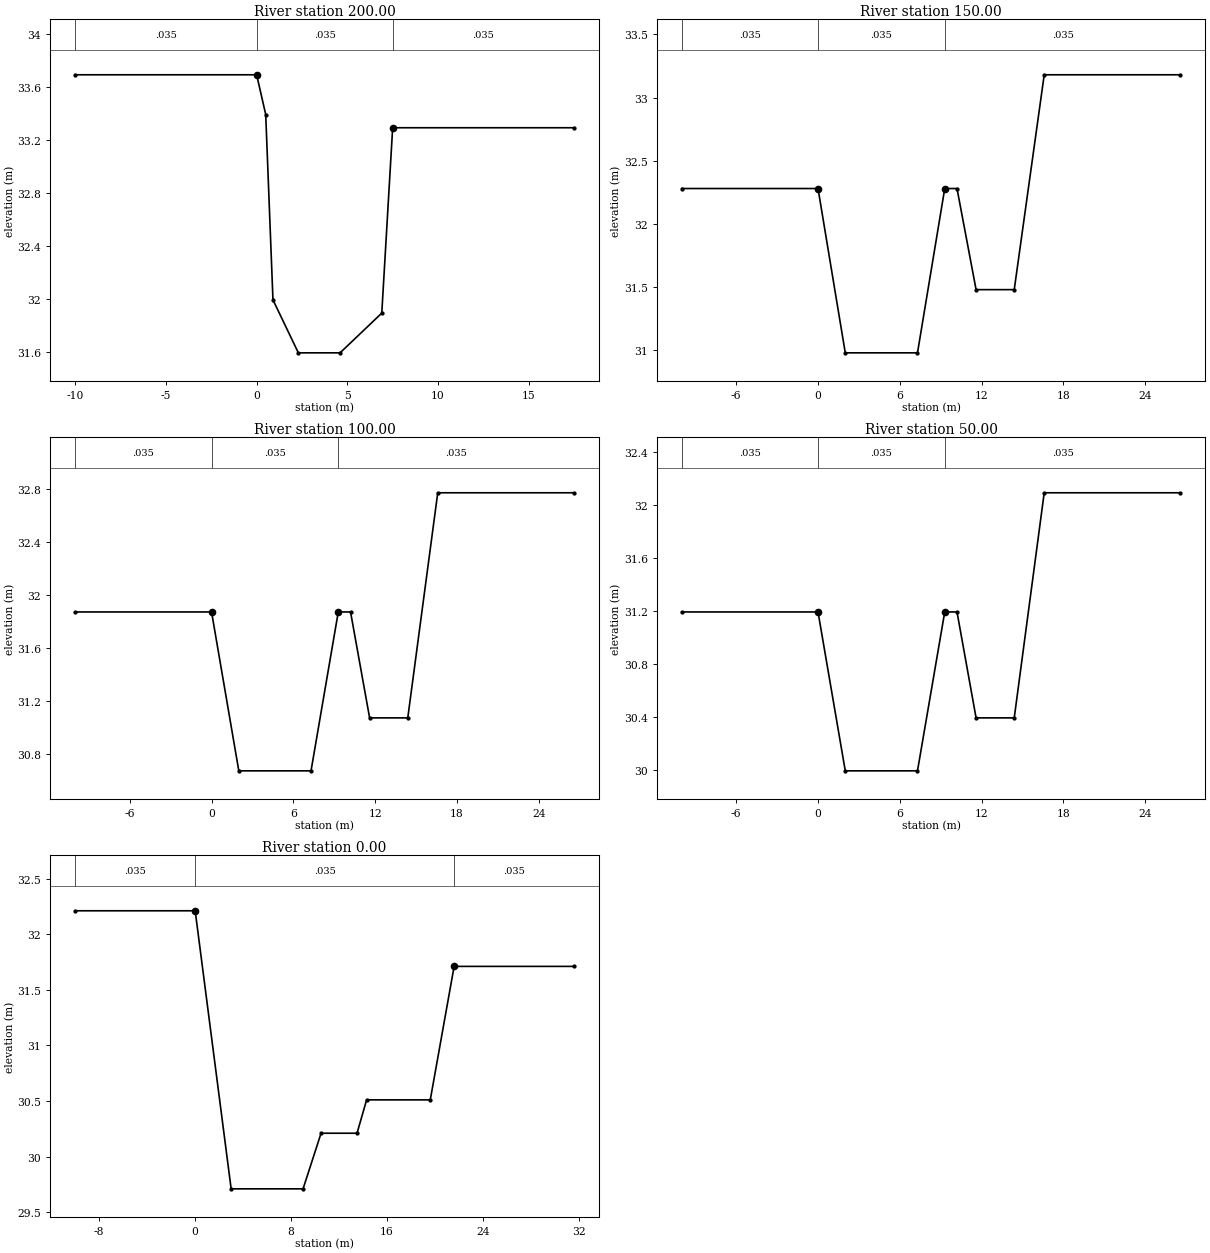
Type RM Length L Ch R = 1 ,200.00  ,50,50,50
BEGIN DESCRIPTION:
4
END DESCRIPTION:
#Sta/Elev= 9
     -10   33.69       0   33.69      .5   33.39      .9   31.99     2.3   31.59
     4.6   31.59     6.9   31.89     7.5   33.29    17.5   33.29
#Mann= 3 , 0 , 0
     -10    .035       0       0    .035       0     7.5    .035       0
#XS Ineff= 2 , 0
               0   33.69     7.5           33.29
Permanent Ineff=
       F       F
Bank Sta=0,7.5
XS Rating Curve= 0
Exp/Cntr=.3,.1

Type RM Length L Ch R = 1 ,150.00  ,50,50,50
BEGIN DESCRIPTION:
3
END DESCRIPTION:
#Sta/Elev= 10
     -10   32.28       0   32.28       2   30.98     7.3   30.98     9.3   32.28
    10.2   32.28    11.6   31.48    14.4   31.48    16.6   33.18    26.6   33.18
#Mann= 3 , 0 , 0
     -10    .035       0       0    .035       0     9.3    .035       0
#XS Ineff= 2 , 0
               0   32.28     9.3           32.28
Permanent Ineff=
       F       F
Bank Sta=0,9.3
XS Rating Curve= 0
Exp/Cntr=.3,.1

Type RM Length L Ch R = 1 ,100.00  ,50,50,50
BEGIN DESCRIPTION:
2
END DESCRIPTION:
#Sta/Elev= 10
     -10   31.87       0   31.87       2   30.67     7.3   30.67     9.3   31.87
    10.2   31.87    11.6   31.07    14.4   31.07    16.6   32.77    26.6   32.77
#Mann= 3 , 0 , 0
     -10    .035       0       0    .035       0     9.3    .035       0
#XS Ineff= 2 , 0
               0   31.87     9.3           31.87
Permanent Ineff=
       F       F
Bank Sta=0,9.3
XS Rating Curve= 0
Exp/Cntr=.3,.1

Type RM Length L Ch R = 1 ,50.00   ,50,50,50
BEGIN DESCRIPTION:
1
END DESCRIPTION:
#Sta/Elev= 10
     -10   31.19       0   31.19       2   29.99     7.3   29.99     9.3   31.19
    10.2   31.19    11.6   30.39    14.4   30.39    16.6   32.09    26.6   32.09
#Mann= 3 , 0 , 0
     -10    .035       0       0    .035       0     9.3    .035       0
#XS Ineff= 2 , 0
               0   31.19     9.3           31.19
Permanent Ineff=
       F       F
Bank Sta=0,9.3
XS Rating Curve= 0
Exp/Cntr=.3,.1

Type RM Length L Ch R = 1 ,0.00    ,0,0,0
BEGIN DESCRIPTION:
0
END DESCRIPTION:
#Sta/Elev= 10
     -10   32.21       0   32.21       3   29.71       9   29.71    10.5   30.21
    13.5   30.21    14.3   30.51   19.61   30.51    21.6   31.71    31.6   31.71
#Mann= 3 , 0 , 0
     -10    .035       0       0    .035       0    21.6    .035       0
#XS Ineff= 2 , 0
               0   32.21    21.6           31.71
Permanent Ineff=
       F       F
Bank Sta=0,21.6
XS Rating Curve= 0
Exp/Cntr=.3,.1

Chan Stop Cuts=-1