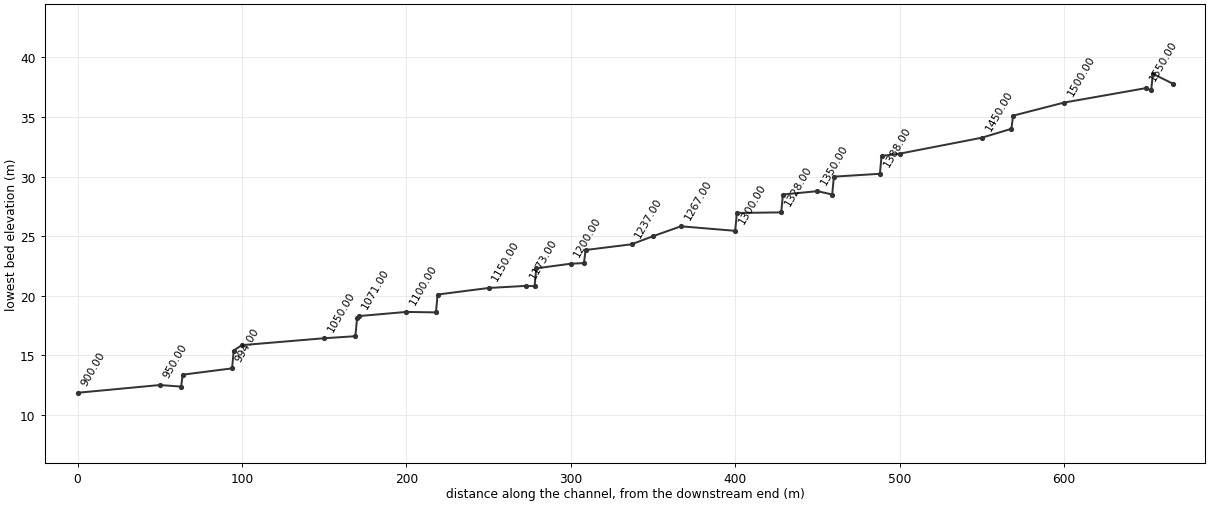
--- WOL.prj (project) ---

Proj Title=wuljun-chun
Current Plan=p01
Default Exp/Contr=.3,.1
SI Units
Geom File=g01
Flow File=f01
Plan File=p01
Y Axis Title=Elevation
X Axis Title(PF)=Main Channel Distance
X Axis Title(XS)=Station
BEGIN DESCRIPTION:
           BACK WATER COMPUTATION
      APPLICATION OF HEC-2 BY Samju Construction Engineering
      wuljun-chun: 10,20,30,50,80 yr
END DESCRIPTION:
DSS Export Rating Curves= 0
DSS Export Rating Curve Sorted= 0
DSS Export Volume Flow Curves= 0
DXF OffsetX= 0
DXF OffsetY= 0
DXF ScaleX= 1
DXF ScaleY= 10

--- WOL.p01 (plan) ---

Plan Title=Imported Plan 01
Version=Version 3.0.1  Mar 2001
Short Identifier=Imported Pla
Geom File=g01
Flow File=f01
Subcritical Flow
K Sum by GR= 0
Std Step Tol= 0.003
Critical Tol= 0.003
Num of Std Step Trials= 20
Max Error Tol= 0.1
Flow Tol Ratio= 0.001
Split Flow NTrial= 30
Split Flow Tol= 0.02
Split Flow Ratio= 0.02
Log Output Level= 0
Friction Slope Method= 1
Unsteady Friction Slope Method= 2
Parabolic Critical Depth
Global Vel Dist= 0 , 0 , 0
Global Log Level= 0
CheckData=True
Encroach Param=-1 ,0,0, 0
Computation Interval=1HOUR
Output Interval=1HOUR
Run HTab= 0
Run UNet= 0
Run PostProcess= 0
UNET Theta= 1
UNET ZTol= 0.02
UNET ZSATol= 0.1
UNET MxIter= 20
UNET MaxInSteps= 20
UNET DtIC= 0
UNET DtMin= 0
UNET MaxCRTS= 20
UNET WFStab= 2
UNET SFStab= 1
UNET WFX= 1
UNET SFX= 1
UNET Convert EG Bridges=-1
UNET Use Existing IB Tables=-1
Instantaneous Interval=1HOUR
Write IC File= 0
Write Velocity= 0
Write Detailed= 0

--- WOL.f01 (steady flow) ---

Flow Title=Imported Flow 01
Version=Version 3.0.1  Mar 2001
Number of Profiles= 5
Profile Names=10YR,20YR,30YR,50YR,80YR
River Rch & RM=RIVER-1,Reach-1         ,1566.00
   11.84   13.04   13.74   14.62   15.43
River Rch & RM=RIVER-1,Reach-1         ,1000.00
   19.36   21.34   22.49   23.95   25.29
Boundary for River Rch & Prof#=RIVER-1,Reach-1         , 1
Up Type= 0
Dn Type= 3
Dn Slope=.042
Boundary for River Rch & Prof#=RIVER-1,Reach-1         , 2
Up Type= 0
Dn Type= 3
Dn Slope=.042
Boundary for River Rch & Prof#=RIVER-1,Reach-1         , 3
Up Type= 0
Dn Type= 3
Dn Slope=.042
Boundary for River Rch & Prof#=RIVER-1,Reach-1         , 4
Up Type= 0
Dn Type= 3
Dn Slope=.042
Boundary for River Rch & Prof#=RIVER-1,Reach-1         , 5
Up Type= 0
Dn Type= 3
Dn Slope=.042
DSS Import GetInterval= 0
DSS Import GetPeak= 0
DSS Import FillOption= 0

--- WOL.g01 (geometry) ---

Geom Title=Imported Geom 01
Version=Version 3.0.1  Mar 2001

River Reach=RIVER-1         ,Reach-1
Reach XY= 2
              .5             .95              .5             .05

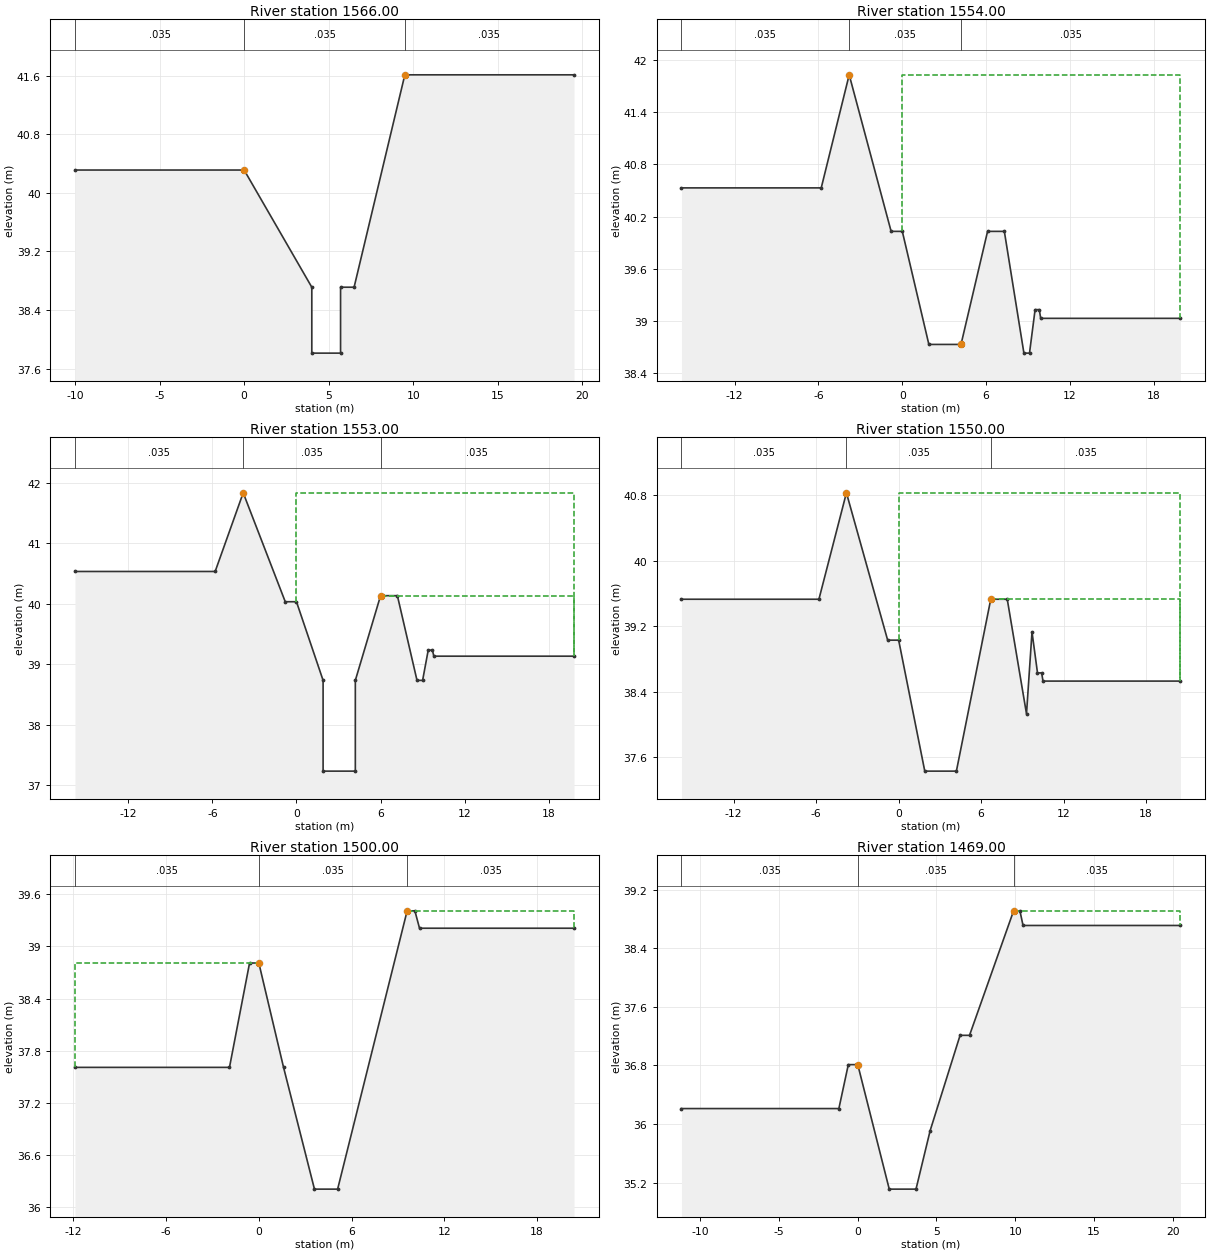
Type RM Length L Ch R = 1 ,1566.00 ,12,12,12
BEGIN DESCRIPTION:
31.016
END DESCRIPTION:
#Sta/Elev= 9
     -10   40.31       0   40.31       4   38.71       4   37.81     5.7   37.81
     5.7   38.71     6.5   38.71     9.5   41.61    19.5   41.61
#Mann= 3 , 0 , 0
     -10    .035       0       0    .035       0     9.5    .035       0
#XS Ineff= 2 , 0
               0   40.31     9.5           41.61
Permanent Ineff=
       F       F
Bank Sta=0,9.5
XS Rating Curve= 0
Exp/Cntr=.3,.1

Type RM Length L Ch R = 1 ,1554.00 ,1,1,1
BEGIN DESCRIPTION:
31.004
END DESCRIPTION:
#Sta/Elev= 15
   -15.8   40.53    -5.8   40.53    -3.8   41.83     -.8   40.03       0   40.03
     1.9   38.73     4.2   38.73     6.1   40.03     7.3   40.03     8.7   38.63
     9.1   38.63     9.5   39.13     9.8   39.13     9.9   39.03    19.9   39.03
#Mann= 3 , 0 , 0
   -15.8    .035       0    -3.8    .035       0     4.2    .035       0
#XS Ineff= 2 , 0
       0    -3.8   41.83     4.2       0   38.73
Permanent Ineff=
       F       F
Bank Sta=-3.8,4.2
XS Rating Curve= 0
Exp/Cntr=.3,.1

Type RM Length L Ch R = 1 ,1553.00 ,3,3,3
BEGIN DESCRIPTION:
31.003
END DESCRIPTION:
#Sta/Elev= 17
   -15.8   40.53    -5.8   40.53    -3.8   41.83     -.8   40.03       0   40.03
     1.9   38.73     1.9   37.23     4.2   37.23     4.2   38.73       6   40.13
     7.2   40.13     8.6   38.73       9   38.73     9.4   39.23     9.7   39.23
     9.8   39.13    19.8   39.13
#Mann= 3 , 0 , 0
   -15.8    .035       0    -3.8    .035       0       6    .035       0
#XS Ineff= 2 , 0
       0    -3.8   41.83       6       0   40.13
Permanent Ineff=
       F       F
Bank Sta=-3.8,6
XS Rating Curve= 0
Exp/Cntr=.3,.1

Type RM Length L Ch R = 1 ,1550.00 ,50,50,50
BEGIN DESCRIPTION:
31
END DESCRIPTION:
#Sta/Elev= 15
   -15.8   39.53    -5.8   39.53    -3.8   40.83     -.8   39.03       0   39.03
     1.9   37.43     4.2   37.43     6.7   39.53     7.9   39.53     9.3   38.13
     9.7   39.13    10.1   38.63    10.4   38.63    10.5   38.53    20.5   38.53
#Mann= 3 , 0 , 0
   -15.8    .035       0    -3.8    .035       0     6.7    .035       0
#XS Ineff= 2 , 0
       0    -3.8   40.83     6.7       0   39.53
Permanent Ineff=
       F       F
Bank Sta=-3.8,6.7
XS Rating Curve= 0
Exp/Cntr=.3,.1

Type RM Length L Ch R = 1 ,1500.00 ,31,31,31
BEGIN DESCRIPTION:
30
END DESCRIPTION:
#Sta/Elev= 11
   -11.9   37.61    -1.9   37.61     -.6   38.81       0   38.81     1.6   37.61
     3.6   36.21     5.1   36.21     9.6   39.41    10.1   39.41    10.4   39.21
    20.4   39.21
#Mann= 3 , 0 , 0
   -11.9    .035       0       0    .035       0     9.6    .035       0
#XS Ineff= 2 , 0
               0   38.81     9.6           39.41
Permanent Ineff=
       F       F
Bank Sta=0,9.6
XS Rating Curve= 0
Exp/Cntr=.3,.1

Type RM Length L Ch R = 1 ,1469.00 ,1,1,1
BEGIN DESCRIPTION:
29.019
END DESCRIPTION:
#Sta/Elev= 13
   -11.2   36.21    -1.2   36.21     -.6   36.81       0   36.81       2   35.11
     3.7   35.11     4.6   35.91     6.5   37.21     7.1   37.21     9.9   38.91
    10.3   38.91    10.5   38.71    20.5   38.71
#Mann= 3 , 0 , 0
   -11.2    .035       0       0    .035       0     9.9    .035       0
#XS Ineff= 2 , 0
       0       0   36.81     9.9       0   38.91
Permanent Ineff=
       F       F
Bank Sta=0,9.9
XS Rating Curve= 0
Exp/Cntr=.3,.1

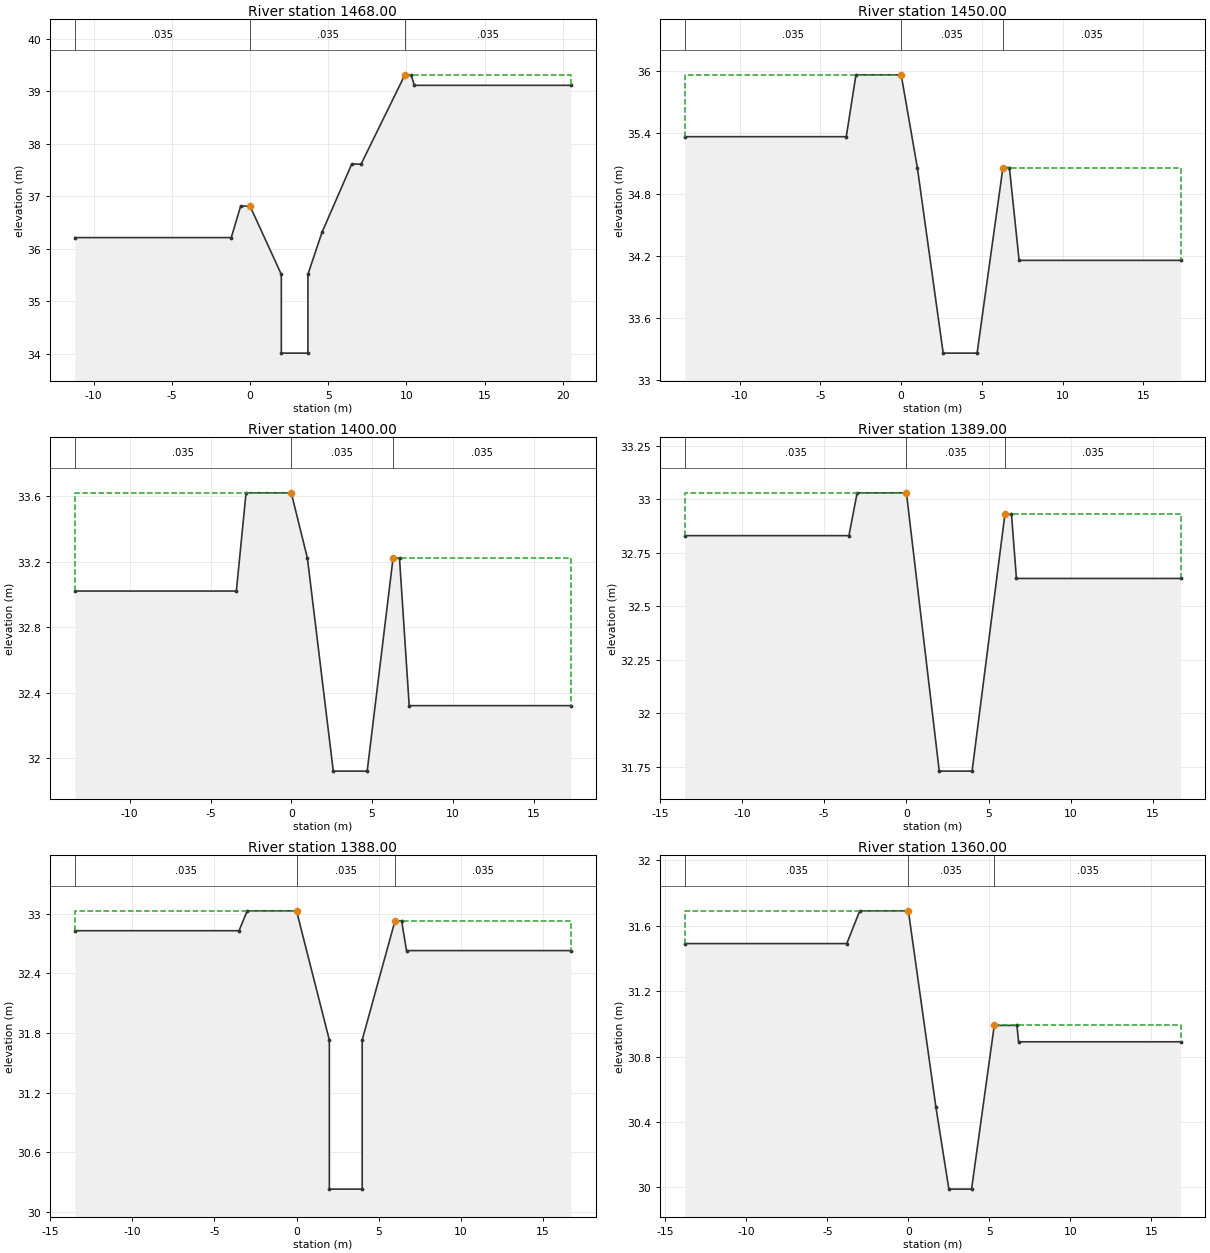
Type RM Length L Ch R = 1 ,1468.00 ,18,18,18
BEGIN DESCRIPTION:
29.018
END DESCRIPTION:
#Sta/Elev= 15
   -11.2   36.21    -1.2   36.21     -.6   36.81       0   36.81       2   35.51
       2   34.01     3.7   34.01     3.7   35.51     4.6   36.31     6.5   37.61
     7.1   37.61     9.9   39.31    10.3   39.31    10.5   39.11    20.5   39.11
#Mann= 3 , 0 , 0
   -11.2    .035       0       0    .035       0     9.9    .035       0
#XS Ineff= 2 , 0
       0       0   36.81     9.9       0   39.31
Permanent Ineff=
       F       F
Bank Sta=0,9.9
XS Rating Curve= 0
Exp/Cntr=.3,.1

Type RM Length L Ch R = 1 ,1450.00 ,50,50,50
BEGIN DESCRIPTION:
29
END DESCRIPTION:
#Sta/Elev= 11
   -13.4   35.36    -3.4   35.36    -2.8   35.96       0   35.96       1   35.06
     2.6   33.26     4.7   33.26     6.3   35.06     6.7   35.06     7.3   34.16
    17.3   34.16
#Mann= 3 , 0 , 0
   -13.4    .035       0       0    .035       0     6.3    .035       0
#XS Ineff= 2 , 0
               0   35.96     6.3           35.06
Permanent Ineff=
       F       F
Bank Sta=0,6.3
XS Rating Curve= 0
Exp/Cntr=.3,.1

Type RM Length L Ch R = 1 ,1400.00 ,11,11,11
BEGIN DESCRIPTION:
28
END DESCRIPTION:
#Sta/Elev= 11
   -13.4   33.02    -3.4   33.02    -2.8   33.62       0   33.62       1   33.22
     2.6   31.92     4.7   31.92     6.3   33.22     6.7   33.22     7.3   32.32
    17.3   32.32
#Mann= 3 , 0 , 0
   -13.4    .035       0       0    .035       0     6.3    .035       0
#XS Ineff= 2 , 0
               0   33.62     6.3           33.22
Permanent Ineff=
       F       F
Bank Sta=0,6.3
XS Rating Curve= 0
Exp/Cntr=.3,.1

Type RM Length L Ch R = 1 ,1389.00 ,1,1,1
BEGIN DESCRIPTION:
27.039
END DESCRIPTION:
#Sta/Elev= 10
   -13.5   32.83    -3.5   32.83      -3   33.03       0   33.03       2   31.73
       4   31.73       6   32.93     6.4   32.93     6.7   32.63    16.7   32.63
#Mann= 3 , 0 , 0
   -13.5    .035       0       0    .035       0       6    .035       0
#XS Ineff= 2 , 0
               0   33.03       6           32.93
Permanent Ineff=
       F       F
Bank Sta=0,6
XS Rating Curve= 0
Exp/Cntr=.3,.1

Type RM Length L Ch R = 1 ,1388.00 ,28,28,28
BEGIN DESCRIPTION:
27.038
END DESCRIPTION:
#Sta/Elev= 12
   -13.5   32.83    -3.5   32.83      -3   33.03       0   33.03       2   31.73
       2   30.23       4   30.23       4   31.73       6   32.93     6.4   32.93
     6.7   32.63    16.7   32.63
#Mann= 3 , 0 , 0
   -13.5    .035       0       0    .035       0       6    .035       0
#XS Ineff= 2 , 0
               0   33.03       6           32.93
Permanent Ineff=
       F       F
Bank Sta=0,6
XS Rating Curve= 0
Exp/Cntr=.3,.1

Type RM Length L Ch R = 1 ,1360.00 ,1,1,1
BEGIN DESCRIPTION:
27.01
END DESCRIPTION:
#Sta/Elev= 11
   -13.8   31.49    -3.8   31.49      -3   31.69       0   31.69     1.7   30.49
     2.5   29.99     3.9   29.99     5.3   30.99     6.7   30.99     6.8   30.89
    16.8   30.89
#Mann= 3 , 0 , 0
   -13.8    .035       0       0    .035       0     5.3    .035       0
#XS Ineff= 2 , 0
               0   31.69     5.3           30.99
Permanent Ineff=
       F       F
Bank Sta=0,5.3
XS Rating Curve= 0
Exp/Cntr=.3,.1

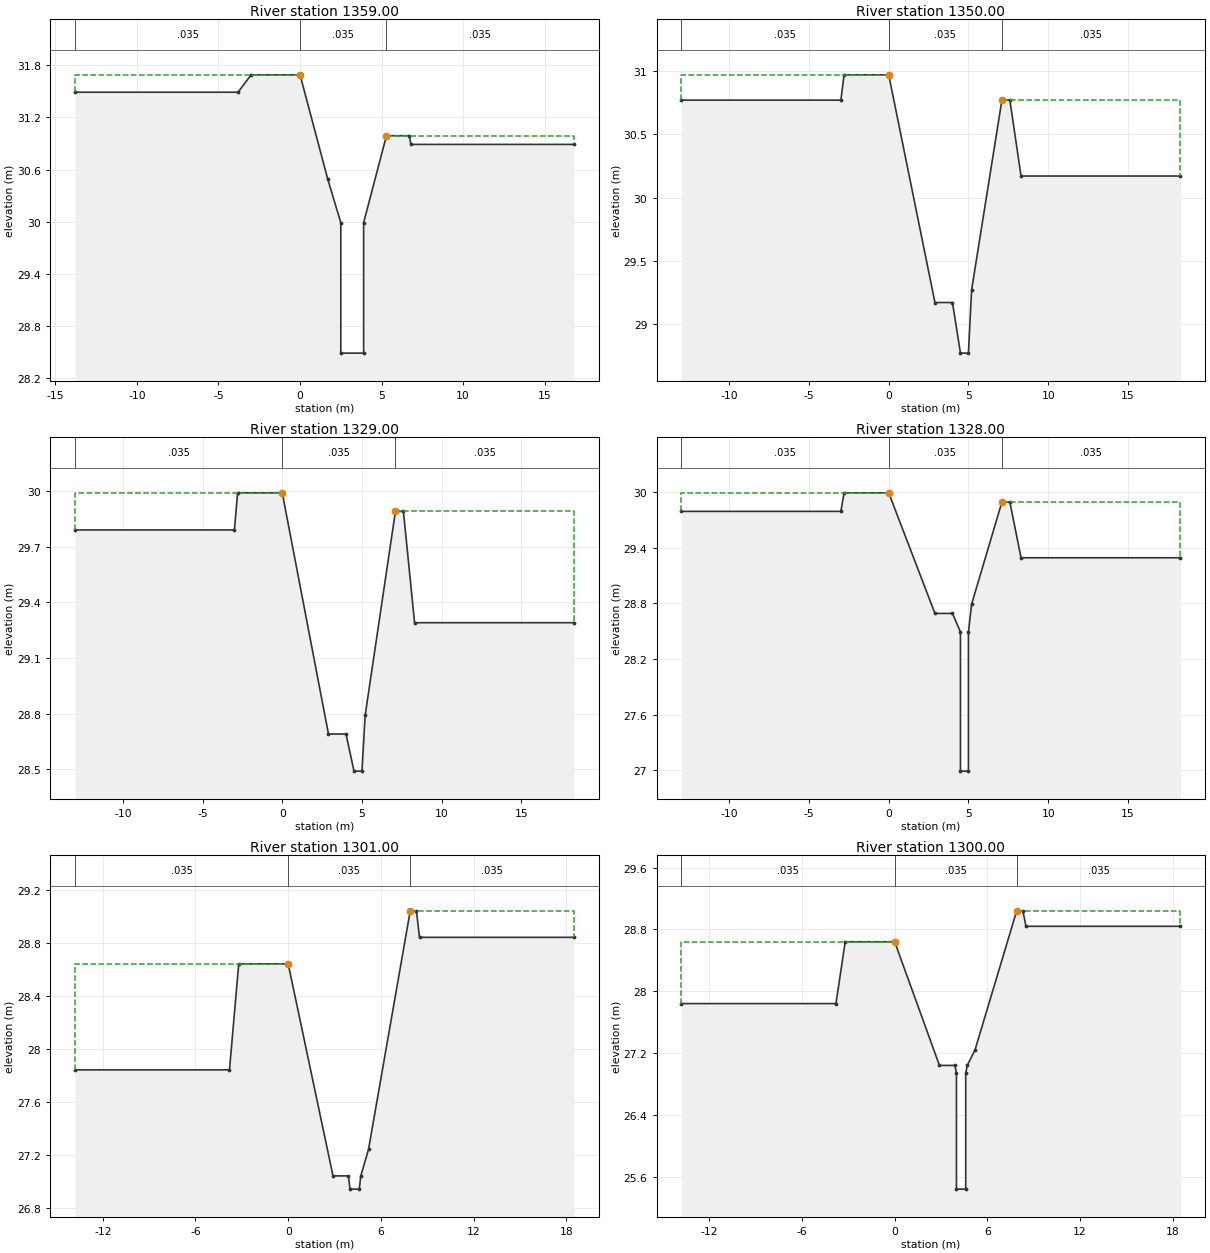
Type RM Length L Ch R = 1 ,1359.00 ,9,9,9
BEGIN DESCRIPTION:
27.009
END DESCRIPTION:
#Sta/Elev= 13
   -13.8   31.49    -3.8   31.49      -3   31.69       0   31.69     1.7   30.49
     2.5   29.99     2.5   28.49     3.9   28.49     3.9   29.99     5.3   30.99
     6.7   30.99     6.8   30.89    16.8   30.89
#Mann= 3 , 0 , 0
   -13.8    .035       0       0    .035       0     5.3    .035       0
#XS Ineff= 2 , 0
               0   31.69     5.3           30.99
Permanent Ineff=
       F       F
Bank Sta=0,5.3
XS Rating Curve= 0
Exp/Cntr=.3,.1

Type RM Length L Ch R = 1 ,1350.00 ,21,21,21
BEGIN DESCRIPTION:
27
END DESCRIPTION:
#Sta/Elev= 13
     -13   30.77      -3   30.77    -2.8   30.97       0   30.97     2.9   29.17
       4   29.17     4.5   28.77       5   28.77     5.2   29.27     7.1   30.77
     7.6   30.77     8.3   30.17    18.3   30.17
#Mann= 3 , 0 , 0
     -13    .035       0       0    .035       0     7.1    .035       0
#XS Ineff= 2 , 0
               0   30.97     7.1           30.77
Permanent Ineff=
       F       F
Bank Sta=0,7.1
XS Rating Curve= 0
Exp/Cntr=.3,.1

Type RM Length L Ch R = 1 ,1329.00 ,1,1,1
BEGIN DESCRIPTION:
26.029
END DESCRIPTION:
#Sta/Elev= 13
     -13   29.79      -3   29.79    -2.8   29.99       0   29.99     2.9   28.69
       4   28.69     4.5   28.49       5   28.49     5.2   28.79     7.1   29.89
     7.6   29.89     8.3   29.29    18.3   29.29
#Mann= 3 , 0 , 0
     -13    .035       0       0    .035       0     7.1    .035       0
#XS Ineff= 2 , 0
               0   29.99     7.1           29.89
Permanent Ineff=
       F       F
Bank Sta=0,7.1
XS Rating Curve= 0
Exp/Cntr=.3,.1

Type RM Length L Ch R = 1 ,1328.00 ,27,27,27
BEGIN DESCRIPTION:
26.028
END DESCRIPTION:
#Sta/Elev= 15
     -13   29.79      -3   29.79    -2.8   29.99       0   29.99     2.9   28.69
       4   28.69     4.5   28.49     4.5   26.99       5   26.99       5   28.49
     5.2   28.79     7.1   29.89     7.6   29.89     8.3   29.29    18.3   29.29
#Mann= 3 , 0 , 0
     -13    .035       0       0    .035       0     7.1    .035       0
#XS Ineff= 2 , 0
               0   29.99     7.1           29.89
Permanent Ineff=
       F       F
Bank Sta=0,7.1
XS Rating Curve= 0
Exp/Cntr=.3,.1

Type RM Length L Ch R = 1 ,1301.00 ,1,1,1
BEGIN DESCRIPTION:
26.001
END DESCRIPTION:
#Sta/Elev= 14
   -13.8   27.84    -3.8   27.84    -3.2   28.64       0   28.64     2.9   27.04
     3.9   27.04       4   26.94     4.6   26.94     4.7   27.04     5.2   27.24
     7.9   29.04     8.3   29.04     8.5   28.84    18.5   28.84
#Mann= 3 , 0 , 0
   -13.8    .035       0       0    .035       0     7.9    .035       0
#XS Ineff= 2 , 0
               0   28.64     7.9           29.04
Permanent Ineff=
       F       F
Bank Sta=0,7.9
XS Rating Curve= 0
Exp/Cntr=.3,.1

Type RM Length L Ch R = 1 ,1300.00 ,33,33,33
BEGIN DESCRIPTION:
26
END DESCRIPTION:
#Sta/Elev= 16
   -13.8   27.84    -3.8   27.84    -3.2   28.64       0   28.64     2.9   27.04
     3.9   27.04       4   26.94       4   25.44     4.6   25.44     4.6   26.94
     4.7   27.04     5.2   27.24     7.9   29.04     8.3   29.04     8.5   28.84
    18.5   28.84
#Mann= 3 , 0 , 0
   -13.8    .035       0       0    .035       0     7.9    .035       0
#XS Ineff= 2 , 0
               0   28.64     7.9           29.04
Permanent Ineff=
       F       F
Bank Sta=0,7.9
XS Rating Curve= 0
Exp/Cntr=.3,.1

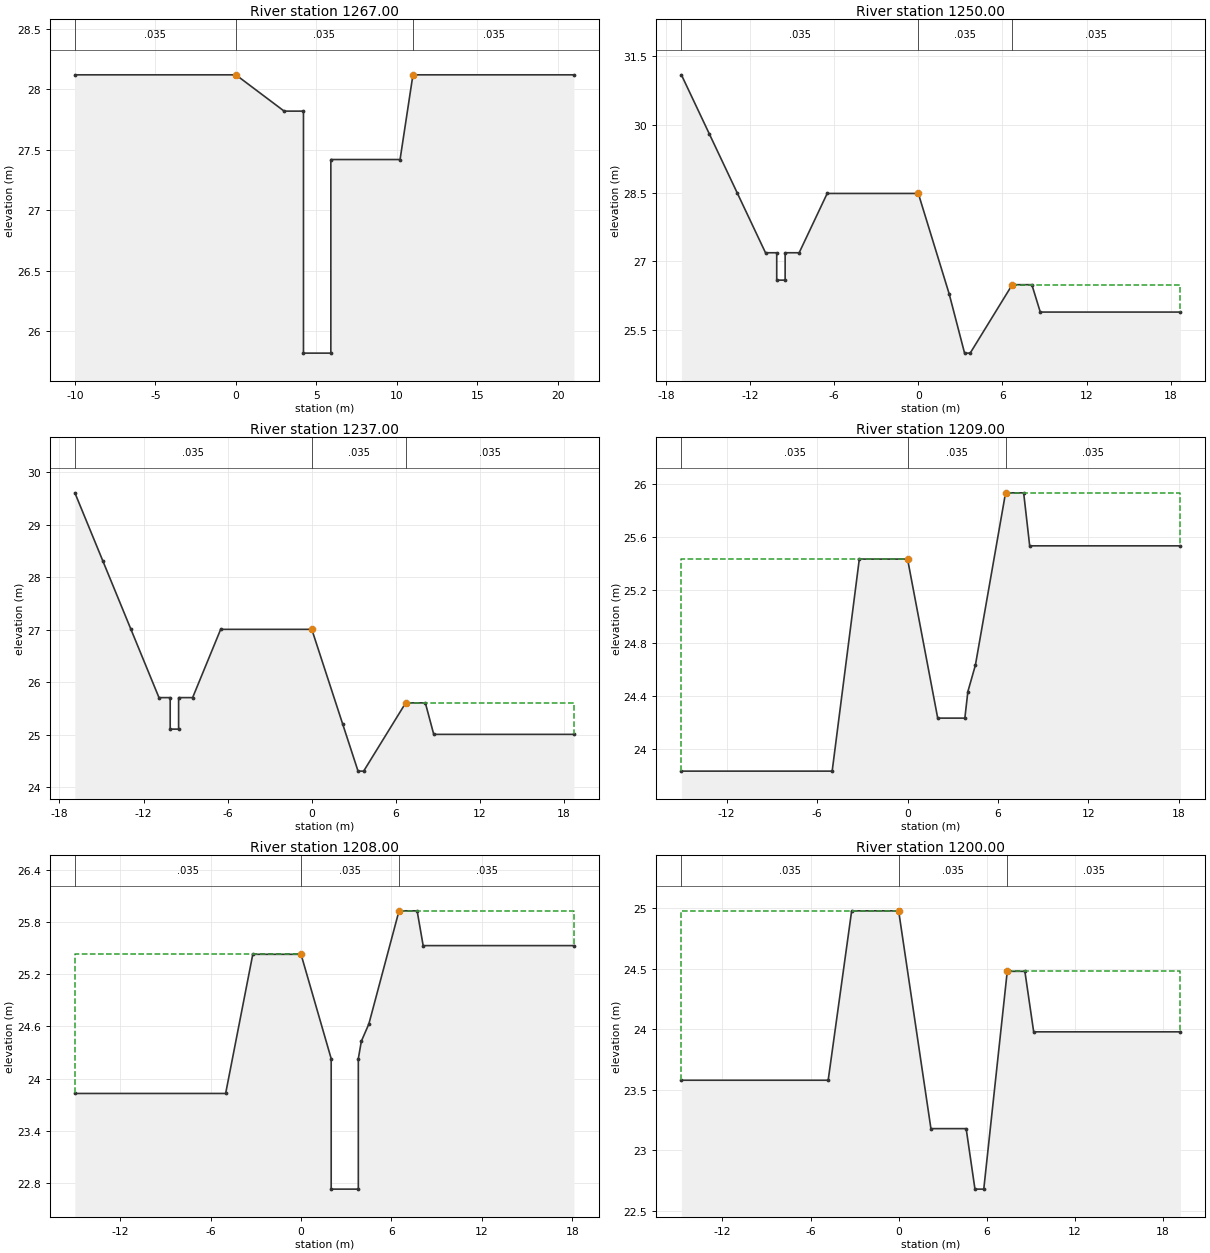
Type RM Length L Ch R = 1 ,1267.00 ,17,17,17
BEGIN DESCRIPTION:
25.017
END DESCRIPTION:
#Sta/Elev= 10
     -10   28.12       0   28.12       3   27.82     4.2   27.82     4.2   25.82
     5.9   25.82     5.9   27.42    10.2   27.42      11   28.12      21   28.12
#Mann= 3 , 0 , 0
     -10    .035       0       0    .035       0      11    .035       0
#XS Ineff= 2 , 0
               0   28.12      11           28.12
Permanent Ineff=
       F       F
Bank Sta=0,11
XS Rating Curve= 0
Exp/Cntr=.3,.1

Type RM Length L Ch R = 1 ,1250.00 ,13,13,13
BEGIN DESCRIPTION:
25
END DESCRIPTION:
#Sta/Elev= 18
   -16.9   31.09   -14.9   29.79   -12.9   28.49   -10.9   27.19   -10.1   27.19
   -10.1   26.59    -9.5   26.59    -9.5   27.19    -8.5   27.19    -6.5   28.49
       0   28.49     2.2   26.29     3.3   24.99     3.7   24.99     6.7   26.49
     8.1   26.49     8.7   25.89    18.7   25.89
#Mann= 3 , 0 , 0
   -16.9    .035       0       0    .035       0     6.7    .035       0
#XS Ineff= 2 , 0
               0   28.49     6.7           26.49
Permanent Ineff=
       F       F
Bank Sta=0,6.7
XS Rating Curve= 0
Exp/Cntr=.3,.1

Type RM Length L Ch R = 1 ,1237.00 ,28,28,28
BEGIN DESCRIPTION:
24.037
END DESCRIPTION:
#Sta/Elev= 18
   -16.9   29.61   -14.9   28.31   -12.9   27.01   -10.9   25.71   -10.1   25.71
   -10.1   25.11    -9.5   25.11    -9.5   25.71    -8.5   25.71    -6.5   27.01
       0   27.01     2.2   25.21     3.3   24.31     3.7   24.31     6.7   25.61
     8.1   25.61     8.7   25.01    18.7   25.01
#Mann= 3 , 0 , 0
   -16.9    .035       0       0    .035       0     6.7    .035       0
#XS Ineff= 2 , 0
               0   27.01     6.7           25.61
Permanent Ineff=
       F       F
Bank Sta=0,6.7
XS Rating Curve= 0
Exp/Cntr=.3,.1

Type RM Length L Ch R = 1 ,1209.00 ,1,1,1
BEGIN DESCRIPTION:
24.009
END DESCRIPTION:
#Sta/Elev= 12
     -15   23.83      -5   23.83    -3.2   25.43       0   25.43       2   24.23
     3.8   24.23       4   24.43     4.5   24.63     6.5   25.93     7.7   25.93
     8.1   25.53    18.1   25.53
#Mann= 3 , 0 , 0
     -15    .035       0       0    .035       0     6.5    .035       0
#XS Ineff= 2 , 0
               0   25.43     6.5           25.93
Permanent Ineff=
       F       F
Bank Sta=0,6.5
XS Rating Curve= 0
Exp/Cntr=.3,.1

Type RM Length L Ch R = 1 ,1208.00 ,8,8,8
BEGIN DESCRIPTION:
24.008
END DESCRIPTION:
#Sta/Elev= 14
     -15   23.83      -5   23.83    -3.2   25.43       0   25.43       2   24.23
       2   22.73     3.8   22.73     3.8   24.23       4   24.43     4.5   24.63
     6.5   25.93     7.7   25.93     8.1   25.53    18.1   25.53
#Mann= 3 , 0 , 0
     -15    .035       0       0    .035       0     6.5    .035       0
#XS Ineff= 2 , 0
               0   25.43     6.5           25.93
Permanent Ineff=
       F       F
Bank Sta=0,6.5
XS Rating Curve= 0
Exp/Cntr=.3,.1

Type RM Length L Ch R = 1 ,1200.00 ,21,21,21
BEGIN DESCRIPTION:
24
END DESCRIPTION:
#Sta/Elev= 12
   -14.8   23.58    -4.8   23.58    -3.2   24.98       0   24.98     2.2   23.18
     4.6   23.18     5.2   22.68     5.8   22.68     7.4   24.48     8.6   24.48
     9.2   23.98    19.2   23.98
#Mann= 3 , 0 , 0
   -14.8    .035       0       0    .035       0     7.4    .035       0
#XS Ineff= 2 , 0
               0   24.98     7.4           24.48
Permanent Ineff=
       F       F
Bank Sta=0,7.4
XS Rating Curve= 0
Exp/Cntr=.3,.1

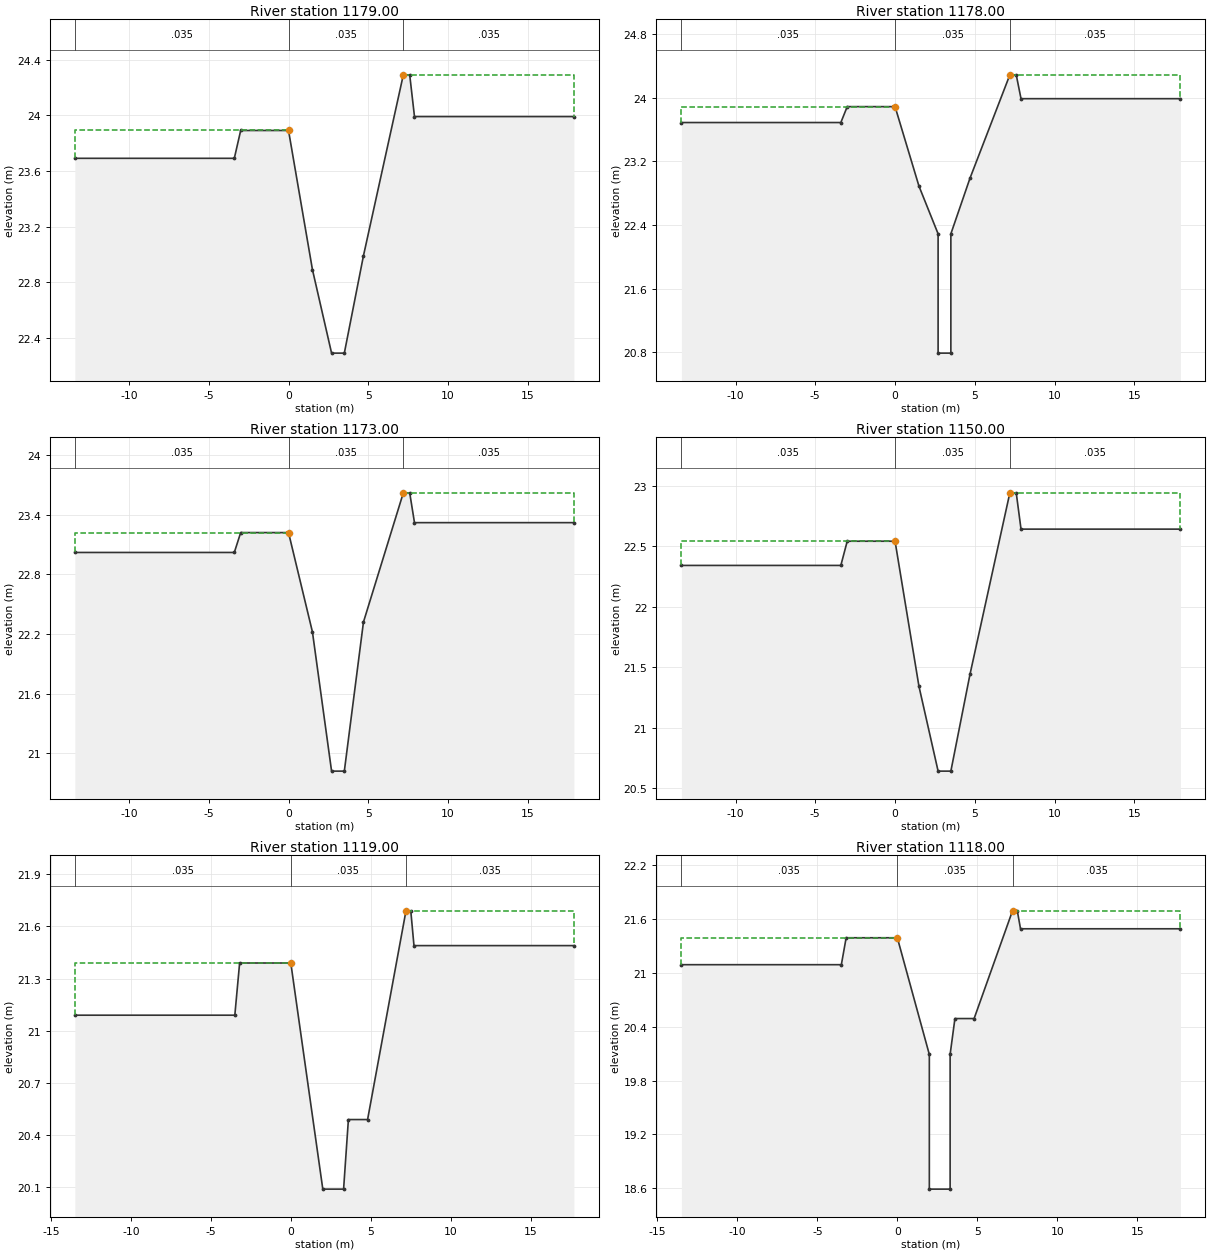
Type RM Length L Ch R = 1 ,1179.00 ,1,1,1
BEGIN DESCRIPTION:
23.029
END DESCRIPTION:
#Sta/Elev= 12
   -13.4   23.69    -3.4   23.69      -3   23.89       0   23.89     1.5   22.89
     2.7   22.29     3.5   22.29     4.7   22.99     7.2   24.29     7.6   24.29
     7.9   23.99    17.9   23.99
#Mann= 3 , 0 , 0
   -13.4    .035       0       0    .035       0     7.2    .035       0
#XS Ineff= 2 , 0
               0   23.89     7.2           24.29
Permanent Ineff=
       F       F
Bank Sta=0,7.2
XS Rating Curve= 0
Exp/Cntr=.3,.1

Type RM Length L Ch R = 1 ,1178.00 ,5,5,5
BEGIN DESCRIPTION:
23.028
END DESCRIPTION:
#Sta/Elev= 14
   -13.4   23.69    -3.4   23.69      -3   23.89       0   23.89     1.5   22.89
     2.7   22.29     2.7   20.79     3.5   20.79     3.5   22.29     4.7   22.99
     7.2   24.29     7.6   24.29     7.9   23.99    17.9   23.99
#Mann= 3 , 0 , 0
   -13.4    .035       0       0    .035       0     7.2    .035       0
#XS Ineff= 2 , 0
               0   23.89     7.2           24.29
Permanent Ineff=
       F       F
Bank Sta=0,7.2
XS Rating Curve= 0
Exp/Cntr=.3,.1

Type RM Length L Ch R = 1 ,1173.00 ,23,23,23
BEGIN DESCRIPTION:
23.023
END DESCRIPTION:
#Sta/Elev= 12
   -13.4   23.02    -3.4   23.02      -3   23.22       0   23.22     1.5   22.22
     2.7   20.82     3.5   20.82     4.7   22.32     7.2   23.62     7.6   23.62
     7.9   23.32    17.9   23.32
#Mann= 3 , 0 , 0
   -13.4    .035       0       0    .035       0     7.2    .035       0
#XS Ineff= 2 , 0
               0   23.22     7.2           23.62
Permanent Ineff=
       F       F
Bank Sta=0,7.2
XS Rating Curve= 0
Exp/Cntr=.3,.1

Type RM Length L Ch R = 1 ,1150.00 ,31,31,31
BEGIN DESCRIPTION:
23
END DESCRIPTION:
#Sta/Elev= 12
   -13.4   22.34    -3.4   22.34      -3   22.54       0   22.54     1.5   21.34
     2.7   20.64     3.5   20.64     4.7   21.44     7.2   22.94     7.6   22.94
     7.9   22.64    17.9   22.64
#Mann= 3 , 0 , 0
   -13.4    .035       0       0    .035       0     7.2    .035       0
#XS Ineff= 2 , 0
               0   22.54     7.2           22.94
Permanent Ineff=
       F       F
Bank Sta=0,7.2
XS Rating Curve= 0
Exp/Cntr=.3,.1

Type RM Length L Ch R = 1 ,1119.00 ,1,1,1
BEGIN DESCRIPTION:
22.019
END DESCRIPTION:
#Sta/Elev= 12
   -13.5   21.09    -3.5   21.09    -3.2   21.39       0   21.39       2   20.09
     3.3   20.09     3.6   20.49     4.8   20.49     7.2   21.69     7.5   21.69
     7.7   21.49    17.7   21.49
#Mann= 3 , 0 , 0
   -13.5    .035       0       0    .035       0     7.2    .035       0
#XS Ineff= 2 , 0
               0   21.39     7.2           21.69
Permanent Ineff=
       F       F
Bank Sta=0,7.2
XS Rating Curve= 0
Exp/Cntr=.3,.1

Type RM Length L Ch R = 1 ,1118.00 ,18,18,18
BEGIN DESCRIPTION:
22.018
END DESCRIPTION:
#Sta/Elev= 14
   -13.5   21.09    -3.5   21.09    -3.2   21.39       0   21.39       2   20.09
       2   18.59     3.3   18.59     3.3   20.09     3.6   20.49     4.8   20.49
     7.2   21.69     7.5   21.69     7.7   21.49    17.7   21.49
#Mann= 3 , 0 , 0
   -13.5    .035       0       0    .035       0     7.2    .035       0
#XS Ineff= 2 , 0
               0   21.39     7.2           21.69
Permanent Ineff=
       F       F
Bank Sta=0,7.2
XS Rating Curve= 0
Exp/Cntr=.3,.1

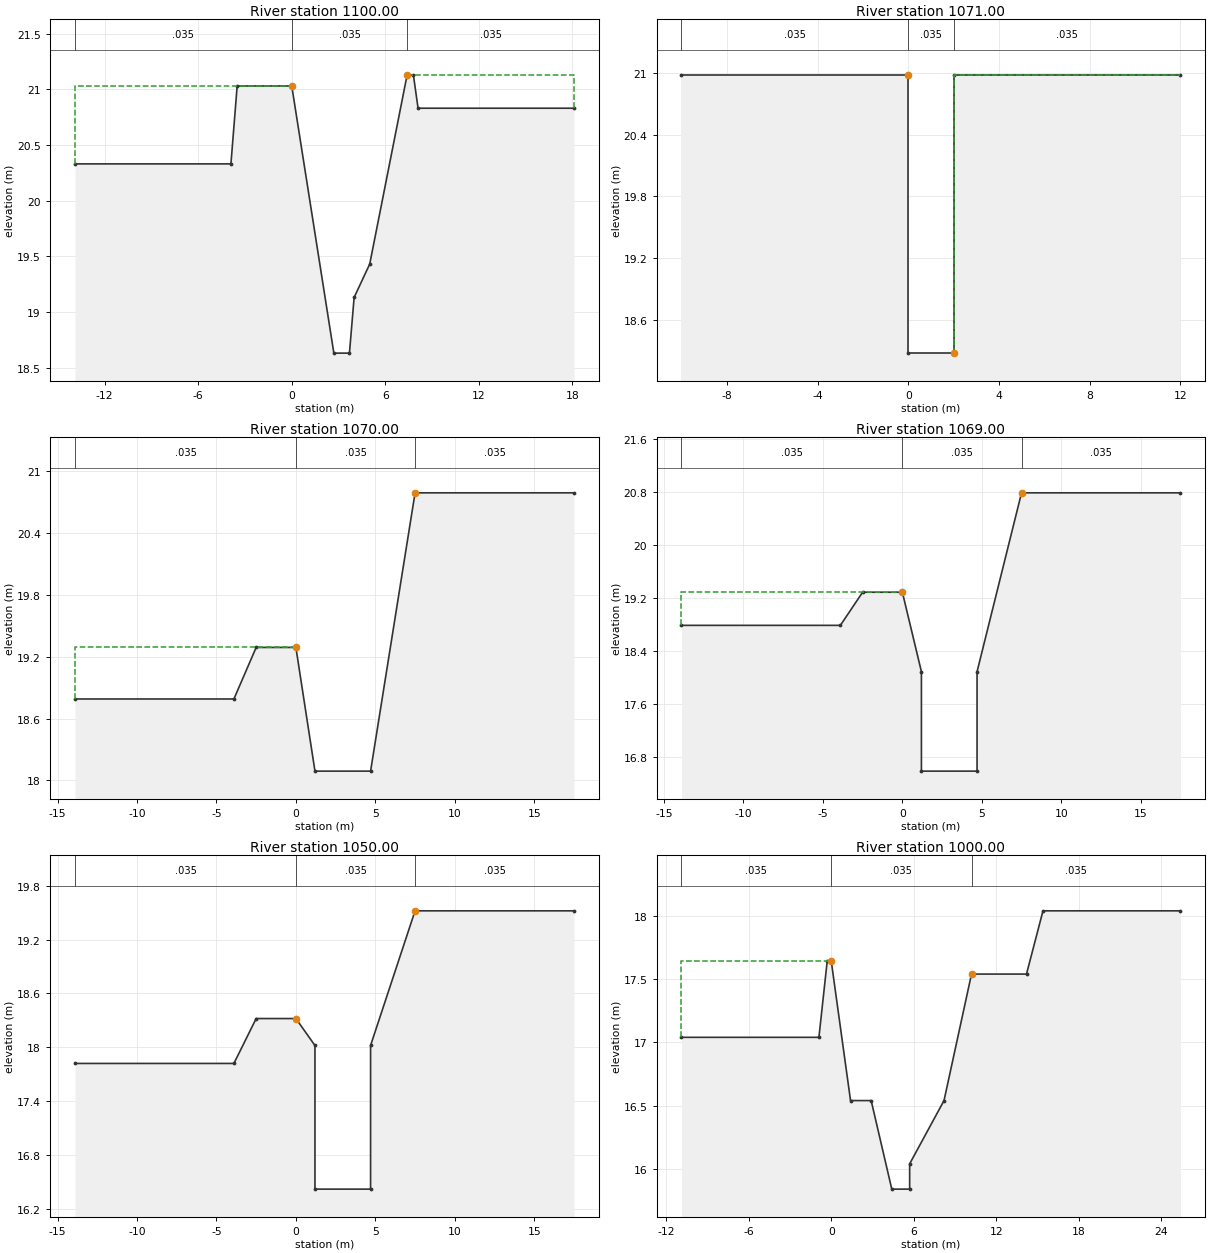
Type RM Length L Ch R = 1 ,1100.00 ,29,29,29
BEGIN DESCRIPTION:
22
END DESCRIPTION:
#Sta/Elev= 12
   -13.9   20.33    -3.9   20.33    -3.5   21.03       0   21.03     2.7   18.63
     3.7   18.63       4   19.13       5   19.43     7.4   21.13     7.8   21.13
     8.1   20.83    18.1   20.83
#Mann= 3 , 0 , 0
   -13.9    .035       0       0    .035       0     7.4    .035       0
#XS Ineff= 2 , 0
               0   21.03     7.4           21.13
Permanent Ineff=
       F       F
Bank Sta=0,7.4
XS Rating Curve= 0
Exp/Cntr=.3,.1

Type RM Length L Ch R = 1 ,1071.00 ,1,1,1
BEGIN DESCRIPTION:
21.021
END DESCRIPTION:
#Sta/Elev= 6
     -10   20.98       0   20.98       0   18.28       2   18.28       2   20.98
      12   20.98
#Mann= 3 , 0 , 0
     -10    .035       0       0    .035       0       2    .035       0
#XS Ineff= 2 , 0
               0   20.98       2           20.98
Permanent Ineff=
       F       F
Bank Sta=0,2
XS Rating Curve= 0
Exp/Cntr=.3,.1

Type RM Length L Ch R = 1 ,1070.00 ,1,1,1
BEGIN DESCRIPTION:
21.02
END DESCRIPTION:
#Sta/Elev= 8
   -13.9   18.79    -3.9   18.79    -2.5   19.29       0   19.29     1.2   18.09
     4.7   18.09     7.5   20.79    17.5   20.79
#Mann= 3 , 0 , 0
   -13.9    .035       0       0    .035       0     7.5    .035       0
#XS Ineff= 2 , 0
               0   19.29     7.5           20.79
Permanent Ineff=
       F       F
Bank Sta=0,7.5
XS Rating Curve= 0
Exp/Cntr=.3,.1

Type RM Length L Ch R = 1 ,1069.00 ,19,19,19
BEGIN DESCRIPTION:
21.019
END DESCRIPTION:
#Sta/Elev= 10
   -13.9   18.79    -3.9   18.79    -2.5   19.29       0   19.29     1.2   18.09
     1.2   16.59     4.7   16.59     4.7   18.09     7.5   20.79    17.5   20.79
#Mann= 3 , 0 , 0
   -13.9    .035       0       0    .035       0     7.5    .035       0
#XS Ineff= 2 , 0
               0   19.29     7.5           20.79
Permanent Ineff=
       F       F
Bank Sta=0,7.5
XS Rating Curve= 0
Exp/Cntr=.3,.1

Type RM Length L Ch R = 1 ,1050.00 ,50,50,50
BEGIN DESCRIPTION:
21
END DESCRIPTION:
#Sta/Elev= 10
   -13.9   17.82    -3.9   17.82    -2.5   18.32       0   18.32     1.2   18.02
     1.2   16.42     4.7   16.42     4.7   18.02     7.5   19.52    17.5   19.52
#Mann= 3 , 0 , 0
   -13.9    .035       0       0    .035       0     7.5    .035       0
#XS Ineff= 2 , 0
       0       0   18.32     7.5       0   19.52
Permanent Ineff=
       F       F
Bank Sta=0,7.5
XS Rating Curve= 0
Exp/Cntr=.3,.1

Type RM Length L Ch R = 1 ,1000.00 ,5,5,5
BEGIN DESCRIPTION:
20
END DESCRIPTION:
#Sta/Elev= 14
   -10.9   17.04     -.9   17.04     -.3   17.64       0   17.64     1.4   16.54
     2.9   16.54     4.4   15.84     5.7   15.84     5.7   16.04     8.2   16.54
    10.2   17.54    14.2   17.54    15.4   18.04    25.4   18.04
#Mann= 3 , 0 , 0
   -10.9    .035       0       0    .035       0    10.2    .035       0
#XS Ineff= 2 , 0
               0   17.64    10.2           17.54
Permanent Ineff=
       F       F
Bank Sta=0,10.2
XS Rating Curve= 0
Exp/Cntr=.3,.1

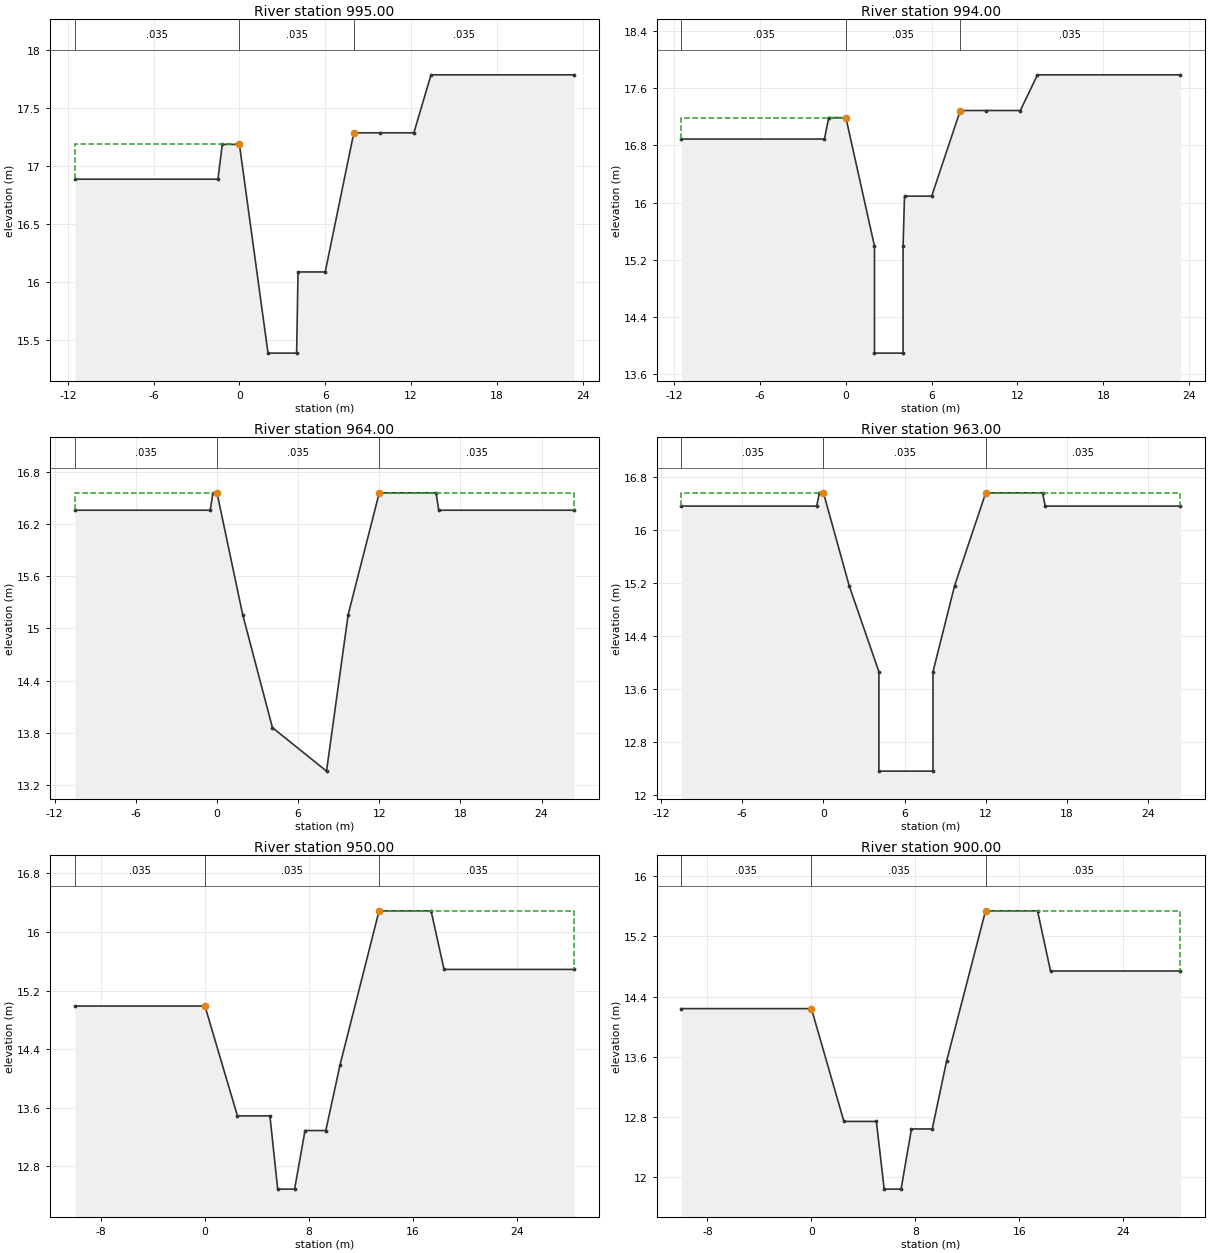
Type RM Length L Ch R = 1 ,995.00  ,1,1,1
BEGIN DESCRIPTION:
19.045
END DESCRIPTION:
#Sta/Elev= 13
   -11.5   16.89    -1.5   16.89    -1.2   17.19       0   17.19       2   15.39
       4   15.39     4.1   16.09       6   16.09       8   17.29     9.8   17.29
    12.2   17.29    13.4   17.79    23.4   17.79
#Mann= 3 , 0 , 0
   -11.5    .035       0       0    .035       0       8    .035       0
#XS Ineff= 2 , 0
               0   17.19       8           17.29
Permanent Ineff=
       F       F
Bank Sta=0,8
XS Rating Curve= 0
Exp/Cntr=.3,.1

Type RM Length L Ch R = 1 ,994.00  ,30,30,30
BEGIN DESCRIPTION:
19.044
END DESCRIPTION:
#Sta/Elev= 15
   -11.5   16.89    -1.5   16.89    -1.2   17.19       0   17.19       2   15.39
       2   13.89       4   13.89       4   15.39     4.1   16.09       6   16.09
       8   17.29     9.8   17.29    12.2   17.29    13.4   17.79    23.4   17.79
#Mann= 3 , 0 , 0
   -11.5    .035       0       0    .035       0       8    .035       0
#XS Ineff= 2 , 0
               0   17.19       8           17.29
Permanent Ineff=
       F       F
Bank Sta=0,8
XS Rating Curve= 0
Exp/Cntr=.3,.1

Type RM Length L Ch R = 1 ,964.00  ,1,1,1
BEGIN DESCRIPTION:
19.014
END DESCRIPTION:
#Sta/Elev= 12
   -10.5   16.36     -.5   16.36     -.3   16.56       0   16.56     1.9   15.16
     4.1   13.86     8.1   13.36     9.7   15.16      12   16.56    16.2   16.56
    16.4   16.36    26.4   16.36
#Mann= 3 , 0 , 0
   -10.5    .035       0       0    .035       0      12    .035       0
#XS Ineff= 2 , 0
               0   16.56      12           16.56
Permanent Ineff=
       F       F
Bank Sta=0,12
XS Rating Curve= 0
Exp/Cntr=.3,.1

Type RM Length L Ch R = 1 ,963.00  ,13,13,13
BEGIN DESCRIPTION:
19.013
END DESCRIPTION:
#Sta/Elev= 14
   -10.5   16.36     -.5   16.36     -.3   16.56       0   16.56     1.9   15.16
     4.1   13.86     4.1   12.36     8.1   12.36     8.1   13.86     9.7   15.16
      12   16.56    16.2   16.56    16.4   16.36    26.4   16.36
#Mann= 3 , 0 , 0
   -10.5    .035       0       0    .035       0      12    .035       0
#XS Ineff= 2 , 0
               0   16.56      12           16.56
Permanent Ineff=
       F       F
Bank Sta=0,12
XS Rating Curve= 0
Exp/Cntr=.3,.1

Type RM Length L Ch R = 1 ,950.00  ,50,50,50
BEGIN DESCRIPTION:
19
END DESCRIPTION:
#Sta/Elev= 13
     -10   14.99       0   14.99     2.5   13.49       5   13.49     5.6   12.49
     6.9   12.49     7.7   13.29     9.3   13.29    10.4   14.19    13.4   16.29
    17.4   16.29    18.4   15.49    28.4   15.49
#Mann= 3 , 0 , 0
     -10    .035       0       0    .035       0    13.4    .035       0
#XS Ineff= 2 , 0
       0       0   14.99    13.4       0   16.29
Permanent Ineff=
       F       F
Bank Sta=0,13.4
XS Rating Curve= 0
Exp/Cntr=.3,.1

Type RM Length L Ch R = 1 ,900.00  ,26,26,26
BEGIN DESCRIPTION:
18
END DESCRIPTION:
#Sta/Elev= 13
     -10   14.24       0   14.24     2.5   12.74       5   12.74     5.6   11.84
     6.9   11.84     7.7   12.64     9.3   12.64    10.4   13.54    13.4   15.54
    17.4   15.54    18.4   14.74    28.4   14.74
#Mann= 3 , 0 , 0
     -10    .035       0       0    .035       0    13.4    .035       0
#XS Ineff= 2 , 0
               0   14.24    13.4           15.54
Permanent Ineff=
       F       F
Bank Sta=0,13.4
XS Rating Curve= 0
Exp/Cntr=.3,.1