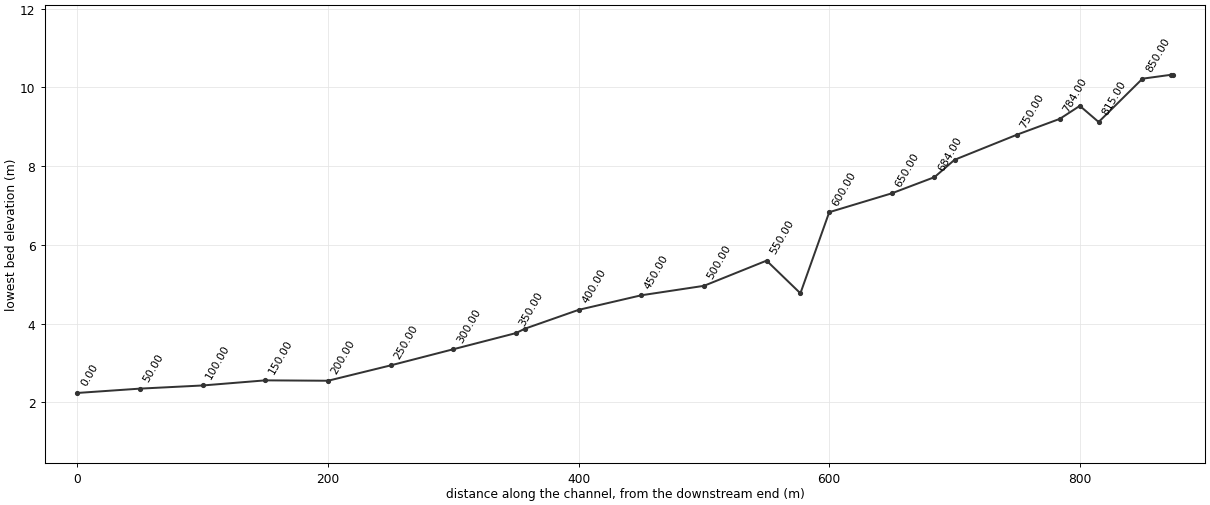
HEC-RAS study WOL.prj: wuljun-chun

--- WOL.g01 (geometry) --- (continued)

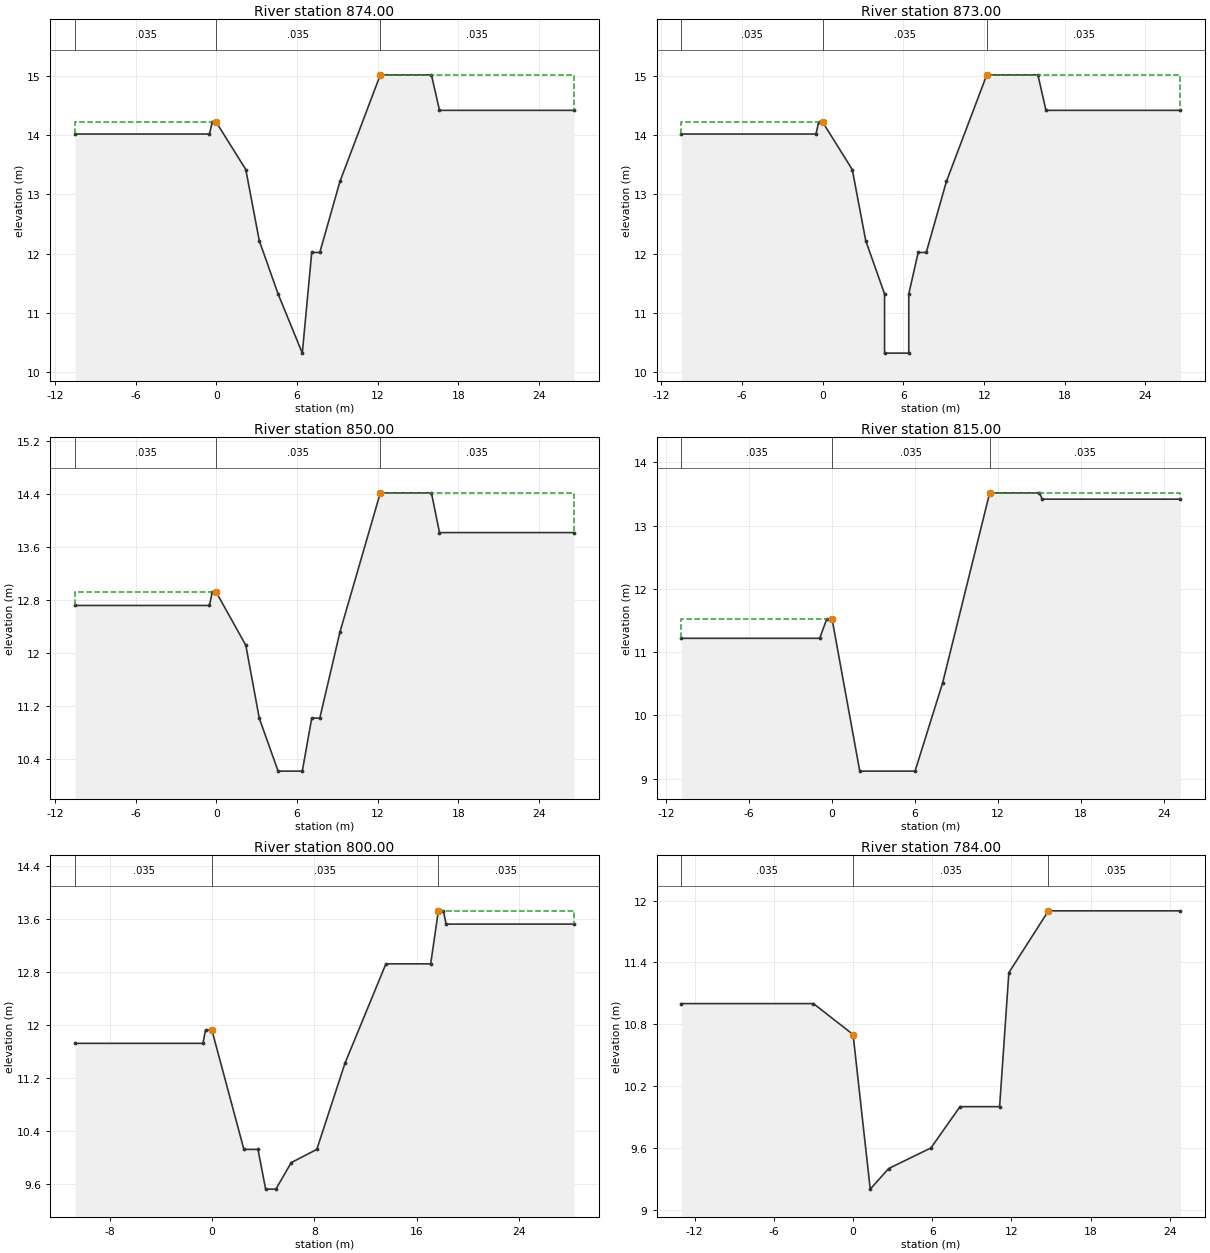
Type RM Length L Ch R = 1 ,874.00  ,1,1,1
BEGIN DESCRIPTION:
17.024
END DESCRIPTION:
#Sta/Elev= 15
   -10.5   14.02     -.5   14.02     -.3   14.22       0   14.22     2.2   13.42
     3.2   12.22     4.6   11.32     6.4   10.32     7.1   12.02     7.7   12.02
     9.2   13.22    12.2   15.02      16   15.02    16.6   14.42    26.6   14.42
#Mann= 3 , 0 , 0
   -10.5    .035       0       0    .035       0    12.2    .035       0
#XS Ineff= 2 , 0
               0   14.22    12.2           15.02
Permanent Ineff=
       F       F
Bank Sta=0,12.2
XS Rating Curve= 0
Exp/Cntr=.3,.1

Type RM Length L Ch R = 1 ,873.00  ,23,23,23
BEGIN DESCRIPTION:
17.023
END DESCRIPTION:
#Sta/Elev= 17
   -10.5   14.02     -.5   14.02     -.3   14.22       0   14.22     2.2   13.42
     3.2   12.22     4.6   11.32     4.6   10.32     6.4   10.32     6.4   11.32
     7.1   12.02     7.7   12.02     9.2   13.22    12.2   15.02      16   15.02
    16.6   14.42    26.6   14.42
#Mann= 3 , 0 , 0
   -10.5    .035       0       0    .035       0    12.2    .035       0
#XS Ineff= 2 , 0
               0   14.22    12.2           15.02
Permanent Ineff=
       F       F
Bank Sta=0,12.2
XS Rating Curve= 0
Exp/Cntr=.3,.1

Type RM Length L Ch R = 1 ,850.00  ,35,35,35
BEGIN DESCRIPTION:
17
END DESCRIPTION:
#Sta/Elev= 15
   -10.5   12.72     -.5   12.72     -.3   12.92       0   12.92     2.2   12.12
     3.2   11.02     4.6   10.22     6.4   10.22     7.1   11.02     7.7   11.02
     9.2   12.32    12.2   14.42      16   14.42    16.6   13.82    26.6   13.82
#Mann= 3 , 0 , 0
   -10.5    .035       0       0    .035       0    12.2    .035       0
#XS Ineff= 2 , 0
               0   12.92    12.2           14.42
Permanent Ineff=
       F       F
Bank Sta=0,12.2
XS Rating Curve= 0
Exp/Cntr=.3,.1

Type RM Length L Ch R = 1 ,815.00  ,15,15,15
BEGIN DESCRIPTION:
16.015
END DESCRIPTION:
#Sta/Elev= 11
   -10.9   11.22     -.9   11.22     -.4   11.52       0   11.52       2    9.12
       6    9.12       8   10.52    11.4   13.52      15   13.52    15.2   13.42
    25.2   13.42
#Mann= 3 , 0 , 0
   -10.9    .035       0       0    .035       0    11.4    .035       0
#XS Ineff= 2 , 0
               0   11.52    11.4           13.52
Permanent Ineff=
       F       F
Bank Sta=0,11.4
XS Rating Curve= 0
Exp/Cntr=.3,.1

Type RM Length L Ch R = 1 ,800.00  ,16,16,16
BEGIN DESCRIPTION:
16
END DESCRIPTION:
#Sta/Elev= 17
   -10.7   11.73     -.7   11.73     -.5   11.93       0   11.93     2.5   10.13
     3.6   10.13     4.2    9.53       5    9.53     6.2    9.93     8.2   10.13
    10.4   11.43    13.6   12.93    17.1   12.93    17.7   13.73    18.1   13.73
    18.3   13.53    28.3   13.53
#Mann= 3 , 0 , 0
   -10.7    .035       0       0    .035       0    17.7    .035       0
#XS Ineff= 2 , 0
       0       0   11.93    17.7       0   13.73
Permanent Ineff=
       F       F
Bank Sta=0,17.7
XS Rating Curve= 0
Exp/Cntr=.3,.1

Type RM Length L Ch R = 1 ,784.00  ,34,34,34
BEGIN DESCRIPTION:
15.034
END DESCRIPTION:
#Sta/Elev= 11
     -13      11      -3      11       0    10.7     1.3     9.2     2.7     9.4
     5.9     9.6     8.1      10    11.1      10    11.8    11.3    14.8    11.9
    24.8    11.9
#Mann= 3 , 0 , 0
     -13    .035       0       0    .035       0    14.8    .035       0
#XS Ineff= 2 , 0
               0    10.7    14.8            11.9
Permanent Ineff=
       F       F
Bank Sta=0,14.8
XS Rating Curve= 0
Exp/Cntr=.3,.1

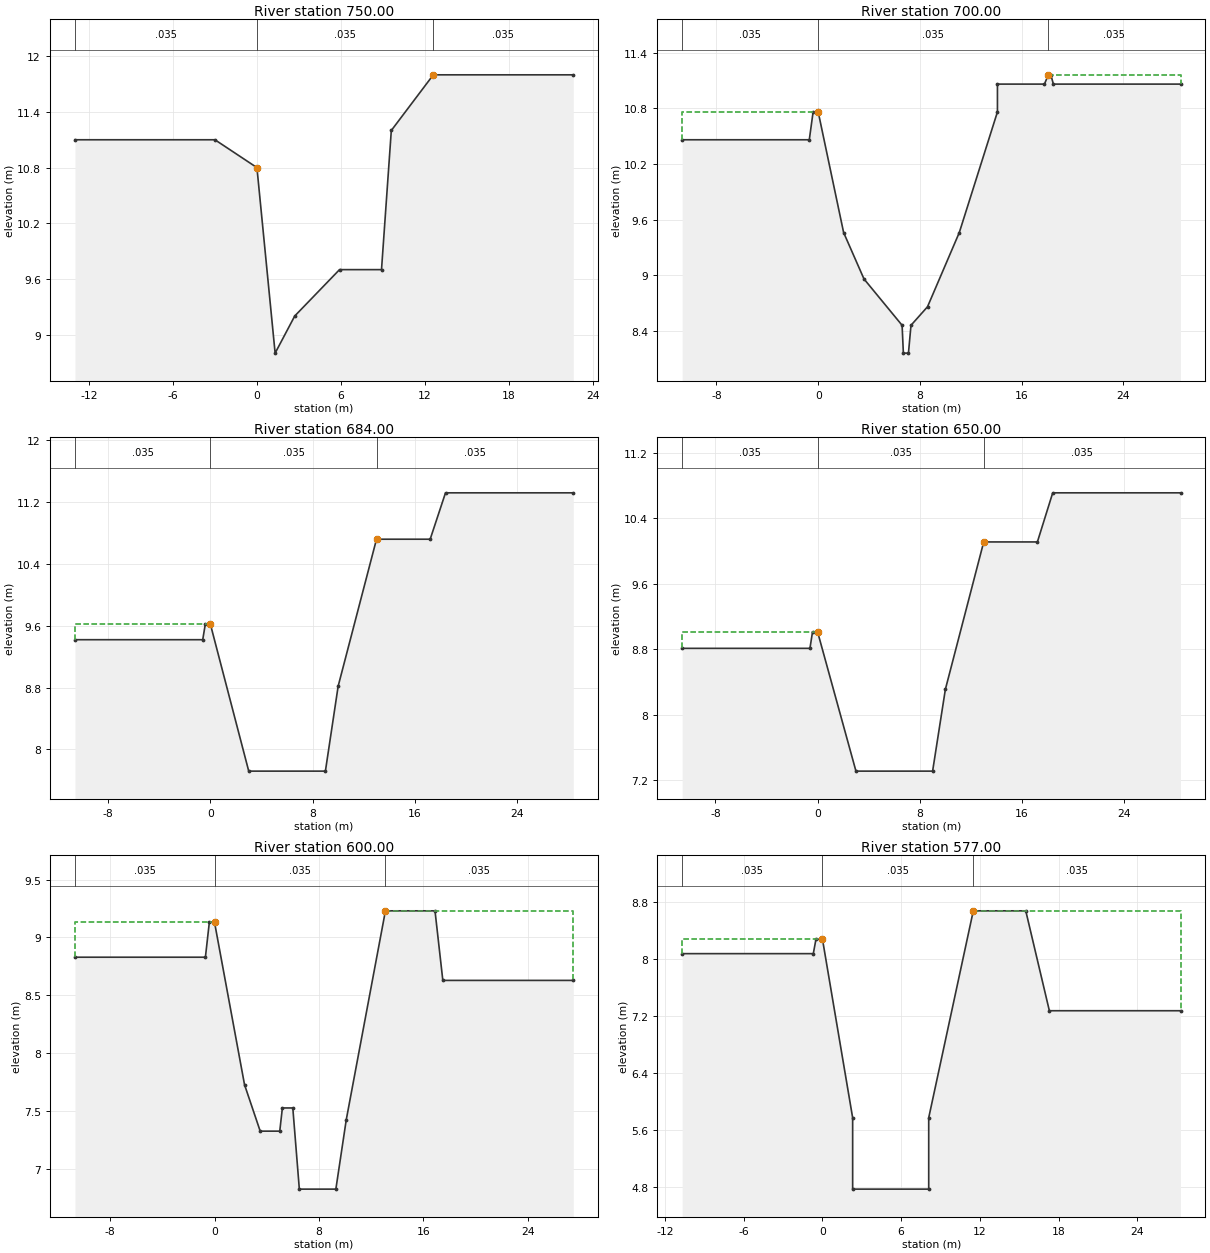
Type RM Length L Ch R = 1 ,750.00  ,50,50,50
BEGIN DESCRIPTION:
15
END DESCRIPTION:
#Sta/Elev= 10
     -13    11.1      -3    11.1       0    10.8     1.3     8.8     2.7     9.2
     5.9     9.7     8.9     9.7     9.6    11.2    12.6    11.8    22.6    11.8
#Mann= 3 , 0 , 0
     -13    .035       0       0    .035       0    12.6    .035       0
#XS Ineff= 2 , 0
       0       0    10.8    12.6       0    11.8
Permanent Ineff=
       F       F
Bank Sta=0,12.6
XS Rating Curve= 0
Exp/Cntr=.3,.1

Type RM Length L Ch R = 1 ,700.00  ,16,16,16
BEGIN DESCRIPTION:
14
END DESCRIPTION:
#Sta/Elev= 19
   -10.7   10.46     -.7   10.46     -.4   10.76       0   10.76       2    9.46
     3.6    8.96     6.6    8.46     6.7    8.16     7.1    8.16     7.3    8.46
     8.6    8.66    11.1    9.46    14.1   10.76    14.1   11.06    17.8   11.06
    18.1   11.16    18.3   11.16    18.5   11.06    28.5   11.06
#Mann= 3 , 0 , 0
   -10.7    .035       0       0    .035       0    18.1    .035       0
#XS Ineff= 2 , 0
               0   10.76    18.1           11.16
Permanent Ineff=
       F       F
Bank Sta=0,18.1
XS Rating Curve= 0
Exp/Cntr=.3,.1

Type RM Length L Ch R = 1 ,684.00  ,34,34,34
BEGIN DESCRIPTION:
13.034
END DESCRIPTION:
#Sta/Elev= 11
   -10.6    9.42     -.6    9.42     -.4    9.62       0    9.62       3    7.72
       9    7.72      10    8.82      13   10.72    17.2   10.72    18.4   11.32
    28.4   11.32
#Mann= 3 , 0 , 0
   -10.6    .035       0       0    .035       0      13    .035       0
#XS Ineff= 2 , 0
               0    9.62      13           10.72
Permanent Ineff=
       F       F
Bank Sta=0,13
XS Rating Curve= 0
Exp/Cntr=.3,.1

Type RM Length L Ch R = 1 ,650.00  ,50,50,50
BEGIN DESCRIPTION:
13
END DESCRIPTION:
#Sta/Elev= 11
   -10.6    8.81     -.6    8.81     -.4    9.01       0    9.01       3    7.31
       9    7.31      10    8.31      13   10.11    17.2   10.11    18.4   10.71
    28.4   10.71
#Mann= 3 , 0 , 0
   -10.6    .035       0       0    .035       0      13    .035       0
#XS Ineff= 2 , 0
               0    9.01      13           10.11
Permanent Ineff=
       F       F
Bank Sta=0,13
XS Rating Curve= 0
Exp/Cntr=.3,.1

Type RM Length L Ch R = 1 ,600.00  ,23,23,23
BEGIN DESCRIPTION:
12
END DESCRIPTION:
#Sta/Elev= 16
   -10.7    8.83     -.7    8.83     -.4    9.13       0    9.13     2.3    7.73
     3.5    7.33       5    7.33     5.2    7.53       6    7.53     6.5    6.83
     9.3    6.83    10.1    7.43    13.1    9.23    16.9    9.23    17.5    8.63
    27.5    8.63
#Mann= 3 , 0 , 0
   -10.7    .035       0       0    .035       0    13.1    .035       0
#XS Ineff= 2 , 0
               0    9.13    13.1            9.23
Permanent Ineff=
       F       F
Bank Sta=0,13.1
XS Rating Curve= 0
Exp/Cntr=.3,.1

Type RM Length L Ch R = 1 ,577.00  ,27,27,27
BEGIN DESCRIPTION:
11.027
END DESCRIPTION:
#Sta/Elev= 12
   -10.7    8.07     -.7    8.07     -.5    8.27       0    8.27     2.3    5.77
     2.3    4.77     8.1    4.77     8.1    5.77    11.5    8.67    15.5    8.67
    17.3    7.27    27.3    7.27
#Mann= 3 , 0 , 0
   -10.7    .035       0       0    .035       0    11.5    .035       0
#XS Ineff= 2 , 0
               0    8.27    11.5            8.67
Permanent Ineff=
       F       F
Bank Sta=0,11.5
XS Rating Curve= 0
Exp/Cntr=.3,.1

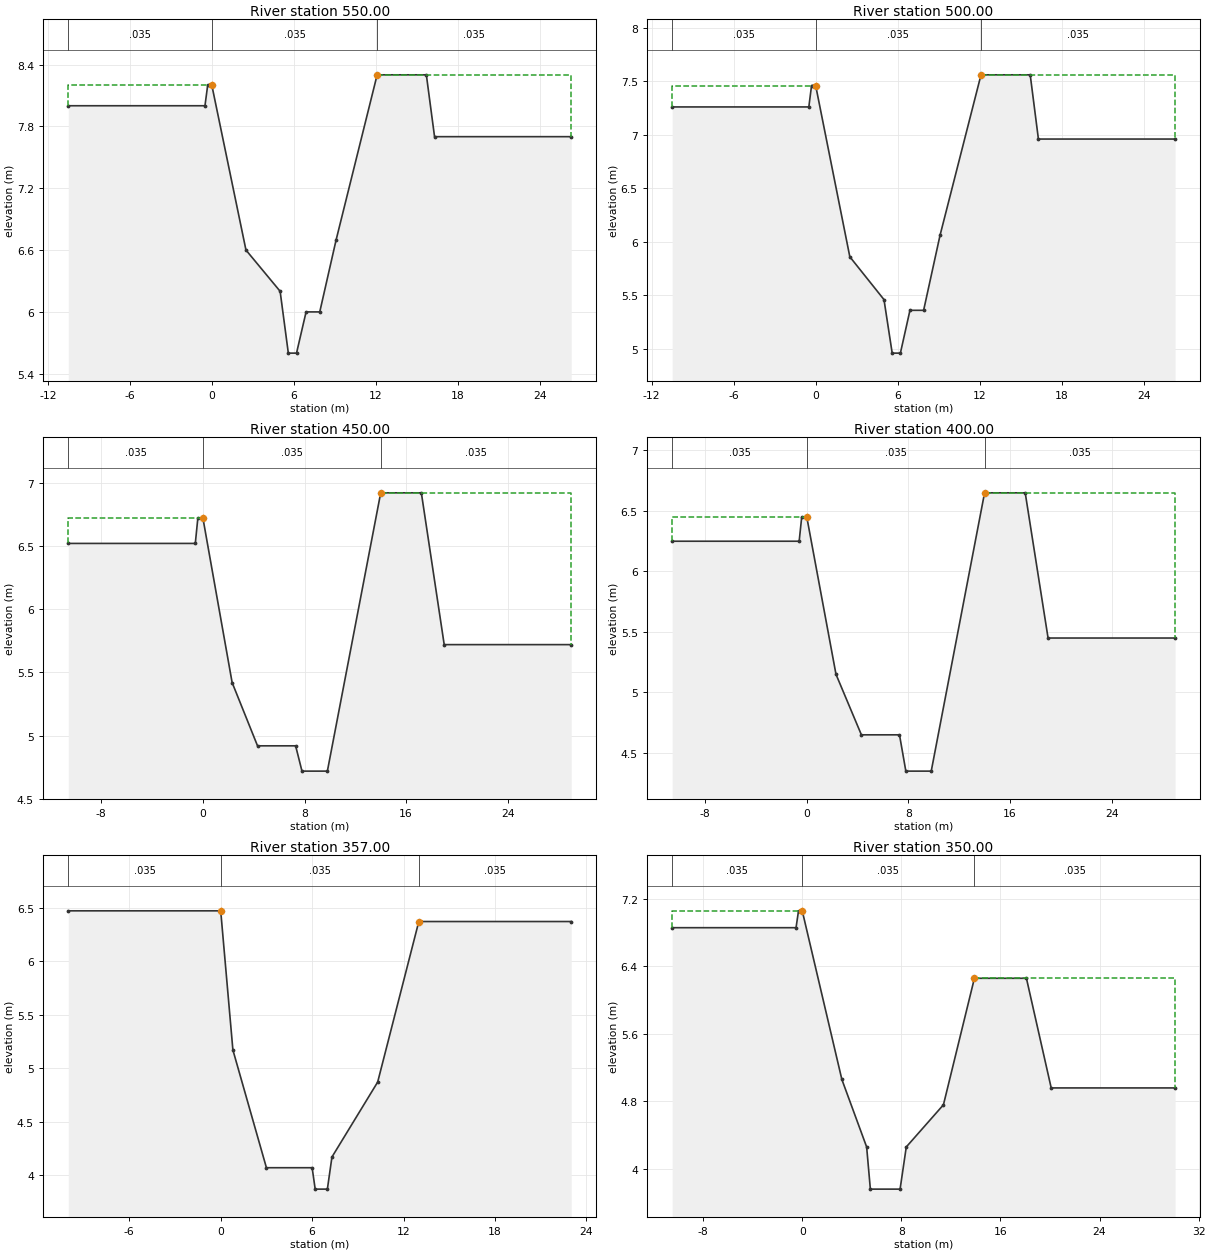
Type RM Length L Ch R = 1 ,550.00  ,50,50,50
BEGIN DESCRIPTION:
11
END DESCRIPTION:
#Sta/Elev= 15
   -10.5       8     -.5       8     -.3     8.2       0     8.2     2.5     6.6
       5     6.2     5.6     5.6     6.2     5.6     6.9       6     7.9       6
     9.1     6.7    12.1     8.3    15.7     8.3    16.3     7.7    26.3     7.7
#Mann= 3 , 0 , 0
   -10.5    .035       0       0    .035       0    12.1    .035       0
#XS Ineff= 2 , 0
               0     8.2    12.1             8.3
Permanent Ineff=
       F       F
Bank Sta=0,12.1
XS Rating Curve= 0
Exp/Cntr=.3,.1

Type RM Length L Ch R = 1 ,500.00  ,50,50,50
BEGIN DESCRIPTION:
10
END DESCRIPTION:
#Sta/Elev= 15
   -10.5    7.26     -.5    7.26     -.3    7.46       0    7.46     2.5    5.86
       5    5.46     5.6    4.96     6.2    4.96     6.9    5.36     7.9    5.36
     9.1    6.06    12.1    7.56    15.7    7.56    16.3    6.96    26.3    6.96
#Mann= 3 , 0 , 0
   -10.5    .035       0       0    .035       0    12.1    .035       0
#XS Ineff= 2 , 0
               0    7.46    12.1            7.56
Permanent Ineff=
       F       F
Bank Sta=0,12.1
XS Rating Curve= 0
Exp/Cntr=.3,.1

Type RM Length L Ch R = 1 ,450.00  ,50,50,50
BEGIN DESCRIPTION:
9
END DESCRIPTION:
#Sta/Elev= 13
   -10.6    6.52     -.6    6.52     -.4    6.72       0    6.72     2.3    5.42
     4.3    4.92     7.3    4.92     7.8    4.72     9.8    4.72      14    6.92
    17.2    6.92      19    5.72      29    5.72
#Mann= 3 , 0 , 0
   -10.6    .035       0       0    .035       0      14    .035       0
#XS Ineff= 2 , 0
               0    6.72      14            6.92
Permanent Ineff=
       F       F
Bank Sta=0,14
XS Rating Curve= 0
Exp/Cntr=.3,.1

Type RM Length L Ch R = 1 ,400.00  ,43,43,43
BEGIN DESCRIPTION:
8
END DESCRIPTION:
#Sta/Elev= 13
   -10.6    6.25     -.6    6.25     -.4    6.45       0    6.45     2.3    5.15
     4.3    4.65     7.3    4.65     7.8    4.35     9.8    4.35      14    6.65
    17.2    6.65      19    5.45      29    5.45
#Mann= 3 , 0 , 0
   -10.6    .035       0       0    .035       0      14    .035       0
#XS Ineff= 2 , 0
               0    6.45      14            6.65
Permanent Ineff=
       F       F
Bank Sta=0,14
XS Rating Curve= 0
Exp/Cntr=.3,.1

Type RM Length L Ch R = 1 ,357.00  ,7,7,7
BEGIN DESCRIPTION:
7.007
END DESCRIPTION:
#Sta/Elev= 11
     -10    6.47       0    6.47      .8    5.17       3    4.07       6    4.07
     6.2    3.87       7    3.87     7.3    4.17    10.3    4.87      13    6.37
      23    6.37
#Mann= 3 , 0 , 0
     -10    .035       0       0    .035       0      13    .035       0
#XS Ineff= 2 , 0
               0    6.47      13            6.37
Permanent Ineff=
       F       F
Bank Sta=0,13
XS Rating Curve= 0
Exp/Cntr=.3,.1

Type RM Length L Ch R = 1 ,350.00  ,50,50,50
BEGIN DESCRIPTION:
7
END DESCRIPTION:
#Sta/Elev= 14
   -10.5    6.86     -.5    6.86     -.3    7.06       0    7.06     3.2    5.06
     5.2    4.26     5.5    3.76     7.9    3.76     8.4    4.26    11.4    4.76
    13.9    6.26    18.1    6.26    20.1    4.96    30.1    4.96
#Mann= 3 , 0 , 0
   -10.5    .035       0       0    .035       0    13.9    .035       0
#XS Ineff= 2 , 0
               0    7.06    13.9            6.26
Permanent Ineff=
       F       F
Bank Sta=0,13.9
XS Rating Curve= 0
Exp/Cntr=.3,.1

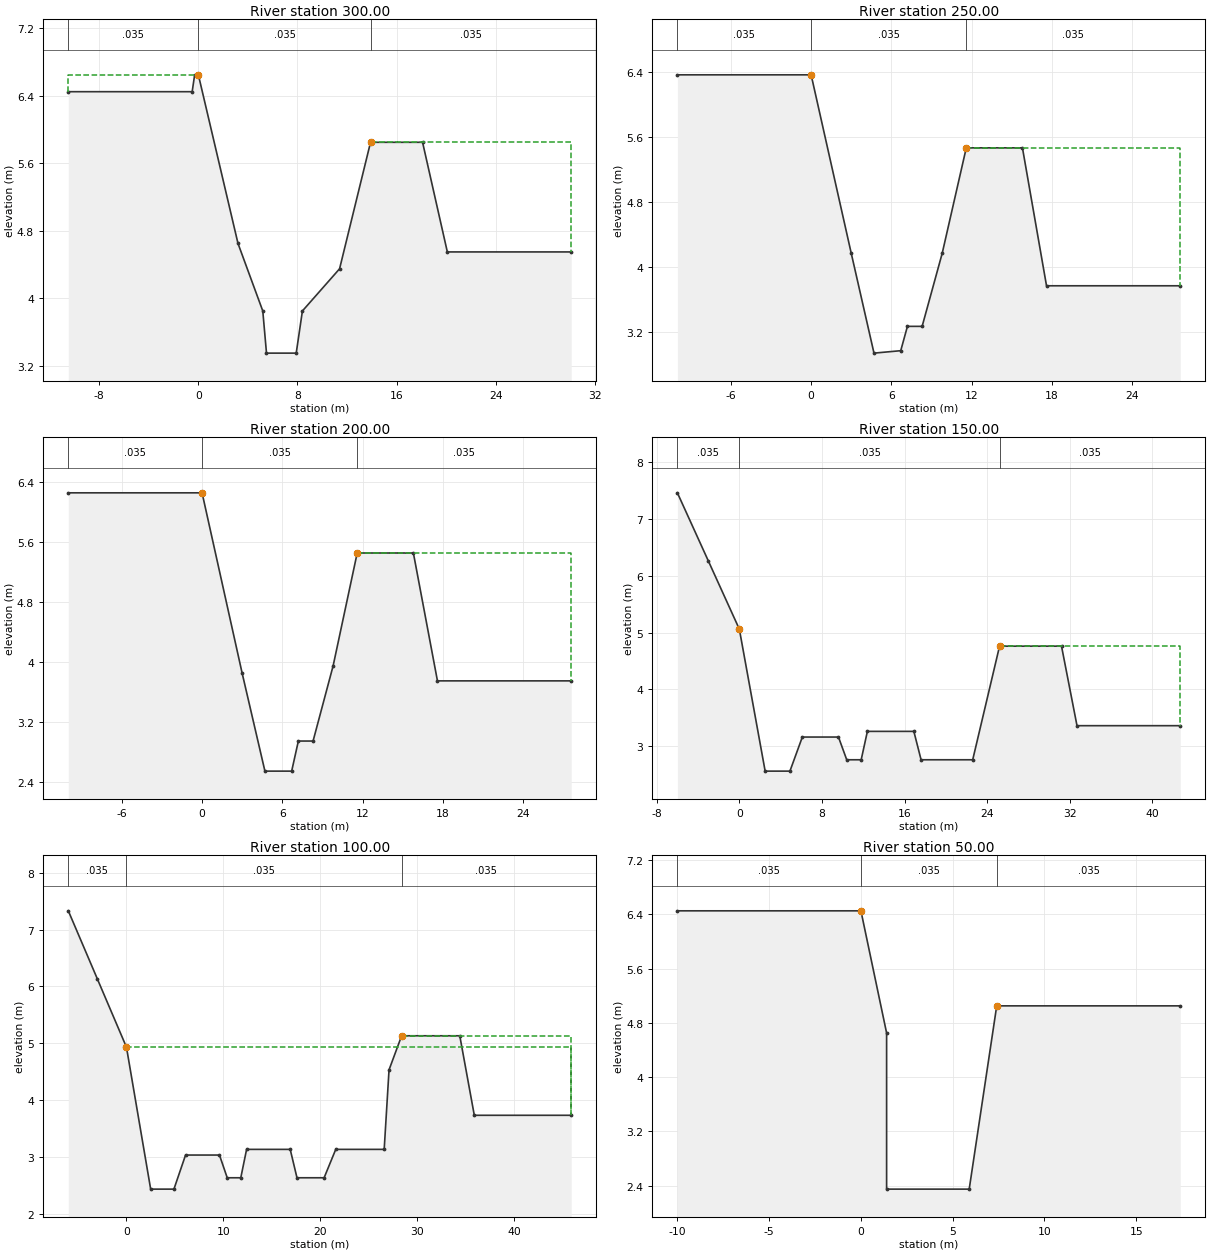
Type RM Length L Ch R = 1 ,300.00  ,50,50,50
BEGIN DESCRIPTION:
6
END DESCRIPTION:
#Sta/Elev= 14
   -10.5    6.45     -.5    6.45     -.3    6.65       0    6.65     3.2    4.65
     5.2    3.85     5.5    3.35     7.9    3.35     8.4    3.85    11.4    4.35
    13.9    5.85    18.1    5.85    20.1    4.55    30.1    4.55
#Mann= 3 , 0 , 0
   -10.5    .035       0       0    .035       0    13.9    .035       0
#XS Ineff= 2 , 0
               0    6.65    13.9            5.85
Permanent Ineff=
       F       F
Bank Sta=0,13.9
XS Rating Curve= 0
Exp/Cntr=.3,.1

Type RM Length L Ch R = 1 ,250.00  ,50,50,50
BEGIN DESCRIPTION:
5
END DESCRIPTION:
#Sta/Elev= 12
     -10    6.37       0    6.37       3    4.17     4.7    2.94     6.7    2.97
     7.2    3.27     8.3    3.27     9.8    4.17    11.6    5.47    15.8    5.47
    17.6    3.77    27.6    3.77
#Mann= 3 , 0 , 0
     -10    .035       0       0    .035       0    11.6    .035       0
#XS Ineff= 2 , 0
               0    6.37    11.6            5.47
Permanent Ineff=
       F       F
Bank Sta=0,11.6
XS Rating Curve= 0
Exp/Cntr=.3,.1

Type RM Length L Ch R = 1 ,200.00  ,50,50,50
BEGIN DESCRIPTION:
4
END DESCRIPTION:
#Sta/Elev= 12
     -10    6.25       0    6.25       3    3.85     4.7    2.55     6.7    2.55
     7.2    2.95     8.3    2.95     9.8    3.95    11.6    5.45    15.8    5.45
    17.6    3.75    27.6    3.75
#Mann= 3 , 0 , 0
     -10    .035       0       0    .035       0    11.6    .035       0
#XS Ineff= 2 , 0
               0    6.25    11.6            5.45
Permanent Ineff=
       F       F
Bank Sta=0,11.6
XS Rating Curve= 0
Exp/Cntr=.3,.1

Type RM Length L Ch R = 1 ,150.00  ,50,50,50
BEGIN DESCRIPTION:
3
END DESCRIPTION:
#Sta/Elev= 17
      -6    7.46      -3    6.26       0    5.06     2.5    2.56     4.9    2.56
     6.1    3.16     9.6    3.16    10.4    2.76    11.8    2.76    12.4    3.26
    16.9    3.26    17.6    2.76    22.6    2.76    25.2    4.76    31.2    4.76
    32.7    3.36    42.7    3.36
#Mann= 3 , 0 , 0
      -6    .035       0       0    .035       0    25.2    .035       0
#XS Ineff= 2 , 0
               0    5.06    25.2            4.76
Permanent Ineff=
       F       F
Bank Sta=0,25.2
XS Rating Curve= 0
Exp/Cntr=.3,.1

Type RM Length L Ch R = 1 ,100.00  ,50,50,50
BEGIN DESCRIPTION:
2
END DESCRIPTION:
#Sta/Elev= 20
      -6    7.33      -3    6.13       0    4.93     2.5    2.43     4.9    2.43
     6.1    3.03     9.6    3.03    10.4    2.63    11.8    2.63    12.4    3.13
    16.9    3.13    17.6    2.63    20.4    2.63    21.6    3.13    26.6    3.13
    27.1    4.53    28.4    5.13    34.4    5.13    35.9    3.73    45.9    3.73
#Mann= 3 , 0 , 0
      -6    .035       0       0    .035       0    28.4    .035       0
#XS Ineff= 2 , 0
       0       0    4.93    28.4       0    5.13
Permanent Ineff=
       F       F
Bank Sta=0,28.4
XS Rating Curve= 0
Exp/Cntr=.3,.1

Type RM Length L Ch R = 1 ,50.00   ,50,50,50
BEGIN DESCRIPTION:
1
END DESCRIPTION:
#Sta/Elev= 7
     -10    6.45       0    6.45     1.4    4.65     1.4    2.35     5.9    2.35
     7.4    5.05    17.4    5.05
#Mann= 3 , 0 , 0
     -10    .035       0       0    .035       0     7.4    .035       0
#XS Ineff= 2 , 0
               0    6.45     7.4            5.05
Permanent Ineff=
       F       F
Bank Sta=0,7.4
XS Rating Curve= 0
Exp/Cntr=.3,.1

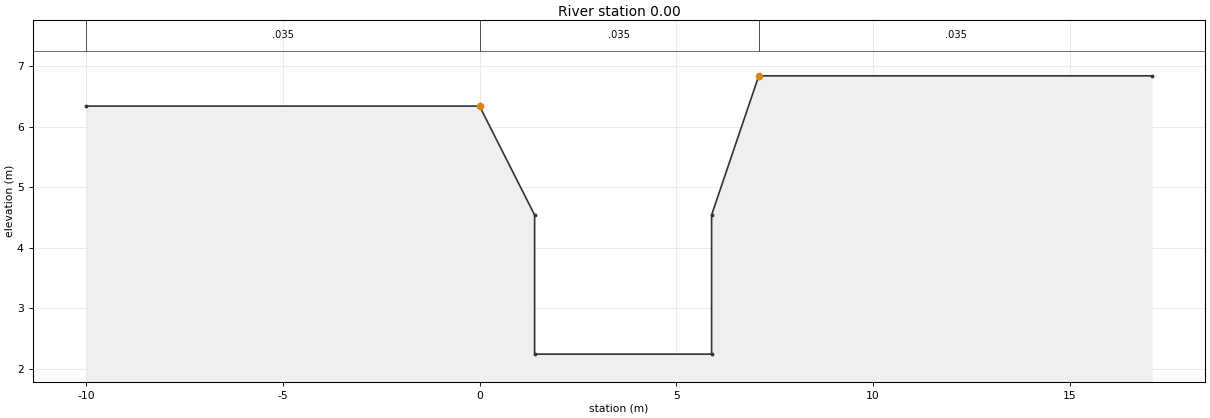
Type RM Length L Ch R = 1 ,0.00    ,0,0,0
BEGIN DESCRIPTION:
0
END DESCRIPTION:
#Sta/Elev= 8
     -10    6.34       0    6.34     1.4    4.54     1.4    2.24     5.9    2.24
     5.9    4.54     7.1    6.84    17.1    6.84
#Mann= 3 , 0 , 0
     -10    .035       0       0    .035       0     7.1    .035       0
#XS Ineff= 2 , 0
               0    6.34     7.1            6.84
Permanent Ineff=
       F       F
Bank Sta=0,7.1
XS Rating Curve= 0
Exp/Cntr=.3,.1

Chan Stop Cuts=-1