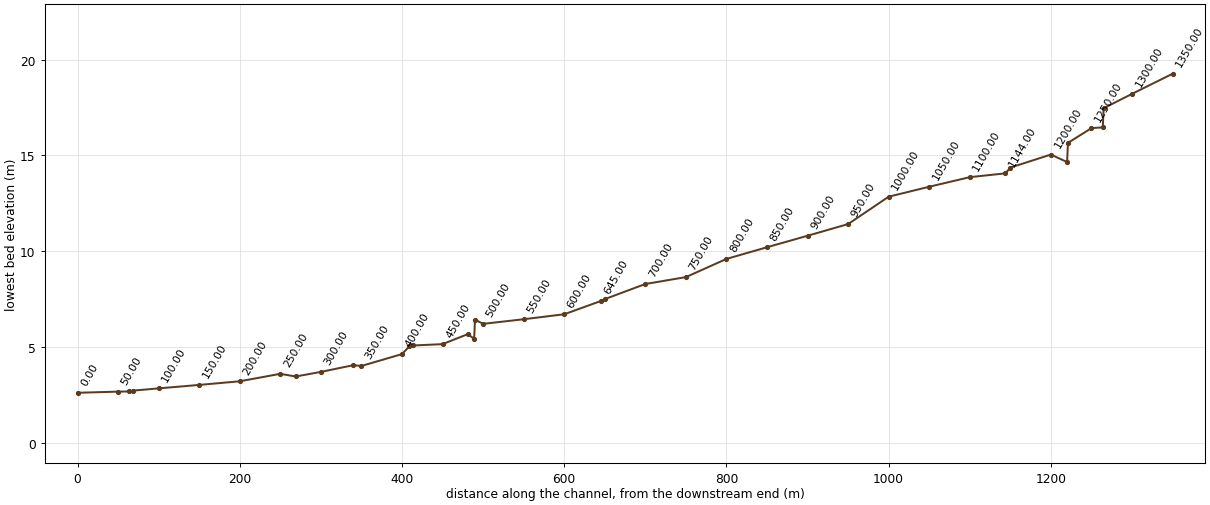
--- UKC.prj (project) ---

Proj Title=UKC
Current Plan=p01
Default Exp/Contr=.3,.1
SI Units
Geom File=g01
Flow File=f01
Plan File=p01
Y Axis Title=Elevation
X Axis Title(PF)=Main Channel Distance
X Axis Title(XS)=Station
BEGIN DESCRIPTION:
           BACK WATER COMPUTATION
      APPLICATION OF HEC-2 BY Samju Construction Engineering
      YOUKOKG-STREEM : 30 YR
END DESCRIPTION:
DSS Export Rating Curves= 0
DSS Export Rating Curve Sorted= 0
DSS Export Volume Flow Curves= 0
DXF OffsetX= 0
DXF OffsetY= 0
DXF ScaleX= 1
DXF ScaleY= 10

--- UKC.p01 (plan) ---

Plan Title=Imported Plan 01
Version=Version 3.0.1  Mar 2001
Short Identifier=Imported Pla
Geom File=g01
Flow File=f01
Subcritical Flow
K Sum by GR= 0
Std Step Tol= 0.003
Critical Tol= 0.003
Num of Std Step Trials= 20
Max Error Tol= 0.1
Flow Tol Ratio= 0.001
Split Flow NTrial= 30
Split Flow Tol= 0.02
Split Flow Ratio= 0.02
Log Output Level= 0
Friction Slope Method= 1
Unsteady Friction Slope Method= 2
Parabolic Critical Depth
Global Vel Dist= 0 , 0 , 0
Global Log Level= 0
CheckData=True
Encroach Param=-1 ,0,0, 0
Computation Interval=1HOUR
Output Interval=1HOUR
Run HTab= 0
Run UNet= 0
Run PostProcess= 0
UNET Theta= 1
UNET ZTol= 0.02
UNET ZSATol= 0.1
UNET MxIter= 20
UNET MaxInSteps= 20
UNET DtIC= 0
UNET DtMin= 0
UNET MaxCRTS= 20
UNET WFStab= 2
UNET SFStab= 1
UNET WFX= 1
UNET SFX= 1
UNET Convert EG Bridges=-1
UNET Use Existing IB Tables=-1
Instantaneous Interval=1HOUR
Write IC File= 0
Write Velocity= 0
Write Detailed= 0

--- UKC.f01 (steady flow) ---

Flow Title=Imported Flow 01
Version=Version 3.0.1  Mar 2001
Number of Profiles= 5
Profile Names=10YR,20YR,30YR,50YR,80YR
River Rch & RM=RIVER-1,Reach-1         ,1350.00
    2.25    2.48    2.61    2.78    2.93
Boundary for River Rch & Prof#=RIVER-1,Reach-1         , 1
Up Type= 0
Dn Type= 3
Dn Slope=.028
Boundary for River Rch & Prof#=RIVER-1,Reach-1         , 2
Up Type= 0
Dn Type= 3
Dn Slope=.028
Boundary for River Rch & Prof#=RIVER-1,Reach-1         , 3
Up Type= 0
Dn Type= 3
Dn Slope=.028
Boundary for River Rch & Prof#=RIVER-1,Reach-1         , 4
Up Type= 0
Dn Type= 3
Dn Slope=.028
Boundary for River Rch & Prof#=RIVER-1,Reach-1         , 5
Up Type= 0
Dn Type= 3
Dn Slope=.028
DSS Import GetInterval= 0
DSS Import GetPeak= 0
DSS Import FillOption= 0

--- UKC.g01 (geometry) ---

Geom Title=Imported Geom 01
Version=Version 3.0.1  Mar 2001

River Reach=RIVER-1         ,Reach-1
Reach XY= 2
              .5             .95              .5             .05

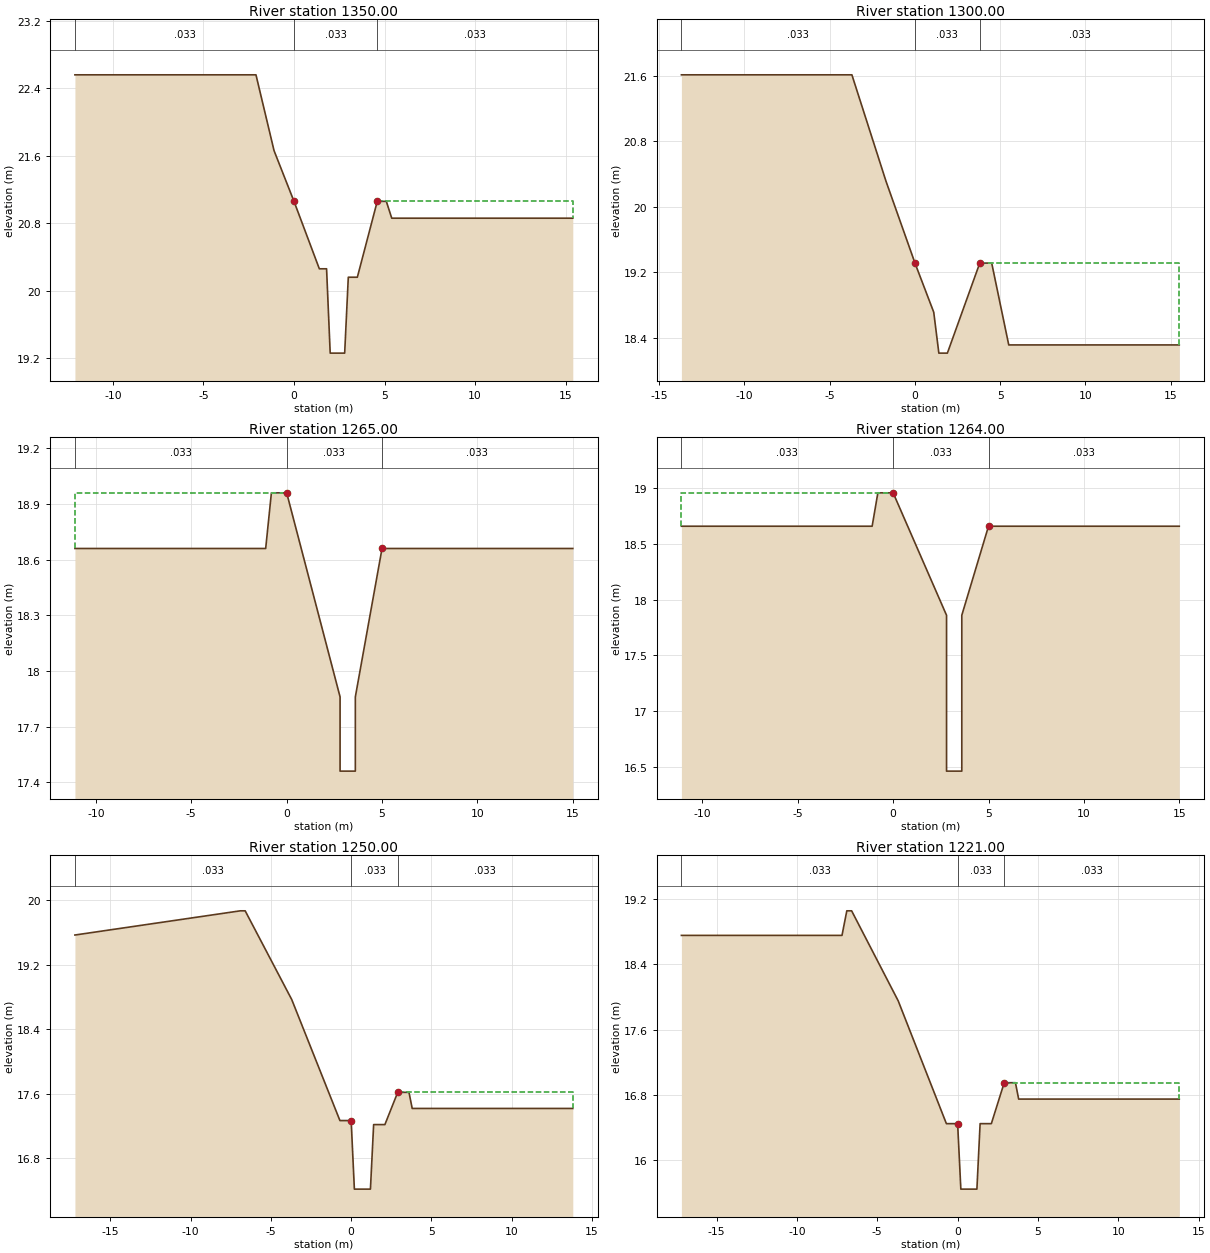
Type RM Length L Ch R = 1 ,1350.00 ,50,50,50
BEGIN DESCRIPTION:
27
END DESCRIPTION:
#Sta/Elev= 14
   -12.1   22.56    -2.1   22.56    -1.1   21.66       0   21.06     1.4   20.26
     1.8   20.26       2   19.26     2.8   19.26       3   20.16     3.5   20.16
     4.6   21.06     5.1   21.06     5.4   20.86    15.4   20.86
#Mann= 3 , 0 , 0
   -12.1    .033       0       0    .033       0     4.6    .033       0
#XS Ineff= 2 , 0
               0   21.06     4.6           21.06
Permanent Ineff=
       F       F
Bank Sta=0,4.6
XS Rating Curve= 0
Exp/Cntr=.3,.1

Type RM Length L Ch R = 1 ,1300.00 ,35,35,35
BEGIN DESCRIPTION:
26
END DESCRIPTION:
#Sta/Elev= 11
   -13.7   21.61    -3.7   21.61    -1.7   20.31       0   19.31     1.1   18.71
     1.4   18.21     1.9   18.21     3.8   19.31     4.5   19.31     5.5   18.31
    15.5   18.31
#Mann= 3 , 0 , 0
   -13.7    .033       0       0    .033       0     3.8    .033       0
#XS Ineff= 2 , 0
               0   19.31     3.8           19.31
Permanent Ineff=
       F       F
Bank Sta=0,3.8
XS Rating Curve= 0
Exp/Cntr=.3,.1

Type RM Length L Ch R = 1 ,1265.00 ,1,1,1
BEGIN DESCRIPTION:
25.015
END DESCRIPTION:
#Sta/Elev= 10
   -11.1   18.66    -1.1   18.66     -.8   18.96       0   18.96     2.8   17.86
     2.8   17.46     3.6   17.46     3.6   17.86       5   18.66      15   18.66
#Mann= 3 , 0 , 0
   -11.1    .033       0       0    .033       0       5    .033       0
#XS Ineff= 2 , 0
               0   18.96       5           18.66
Permanent Ineff=
       F       F
Bank Sta=0,5
XS Rating Curve= 0
Exp/Cntr=.3,.1

Type RM Length L Ch R = 1 ,1264.00 ,14,14,14
BEGIN DESCRIPTION:
25.014
END DESCRIPTION:
#Sta/Elev= 12
   -11.1   18.66    -1.1   18.66     -.8   18.96       0   18.96     2.8   17.86
     2.8   17.46     2.8   16.46     3.6   16.46     3.6   17.46     3.6   17.86
       5   18.66      15   18.66
#Mann= 3 , 0 , 0
   -11.1    .033       0       0    .033       0       5    .033       0
#XS Ineff= 2 , 0
               0   18.96       5           18.66
Permanent Ineff=
       F       F
Bank Sta=0,5
XS Rating Curve= 0
Exp/Cntr=.3,.1

Type RM Length L Ch R = 1 ,1250.00 ,29,29,29
BEGIN DESCRIPTION:
25
END DESCRIPTION:
#Sta/Elev= 14
   -17.2   19.57    -6.9   19.87    -6.6   19.87    -3.7   18.77     -.7   17.27
       0   17.27      .2   16.42     1.2   16.42     1.4   17.22     2.1   17.22
     2.9   17.62     3.6   17.62     3.8   17.42    13.8   17.42
#Mann= 3 , 0 , 0
   -17.2    .033       0       0    .033       0     2.9    .033       0
#XS Ineff= 2 , 0
               0   17.27     2.9           17.62
Permanent Ineff=
       F       F
Bank Sta=0,2.9
XS Rating Curve= 0
Exp/Cntr=.3,.1

Type RM Length L Ch R = 1 ,1221.00 ,1,1,1
BEGIN DESCRIPTION:
24.021
END DESCRIPTION:
#Sta/Elev= 15
   -17.2   18.75    -7.2   18.75    -6.9   19.05    -6.6   19.05    -3.7   17.95
     -.7   16.45       0   16.45      .2   15.65     1.2   15.65     1.4   16.45
     2.1   16.45     2.9   16.95     3.6   16.95     3.8   16.75    13.8   16.75
#Mann= 3 , 0 , 0
   -17.2    .033       0       0    .033       0     2.9    .033       0
#XS Ineff= 2 , 0
               0   16.45     2.9           16.95
Permanent Ineff=
       F       F
Bank Sta=0,2.9
XS Rating Curve= 0
Exp/Cntr=.3,.1

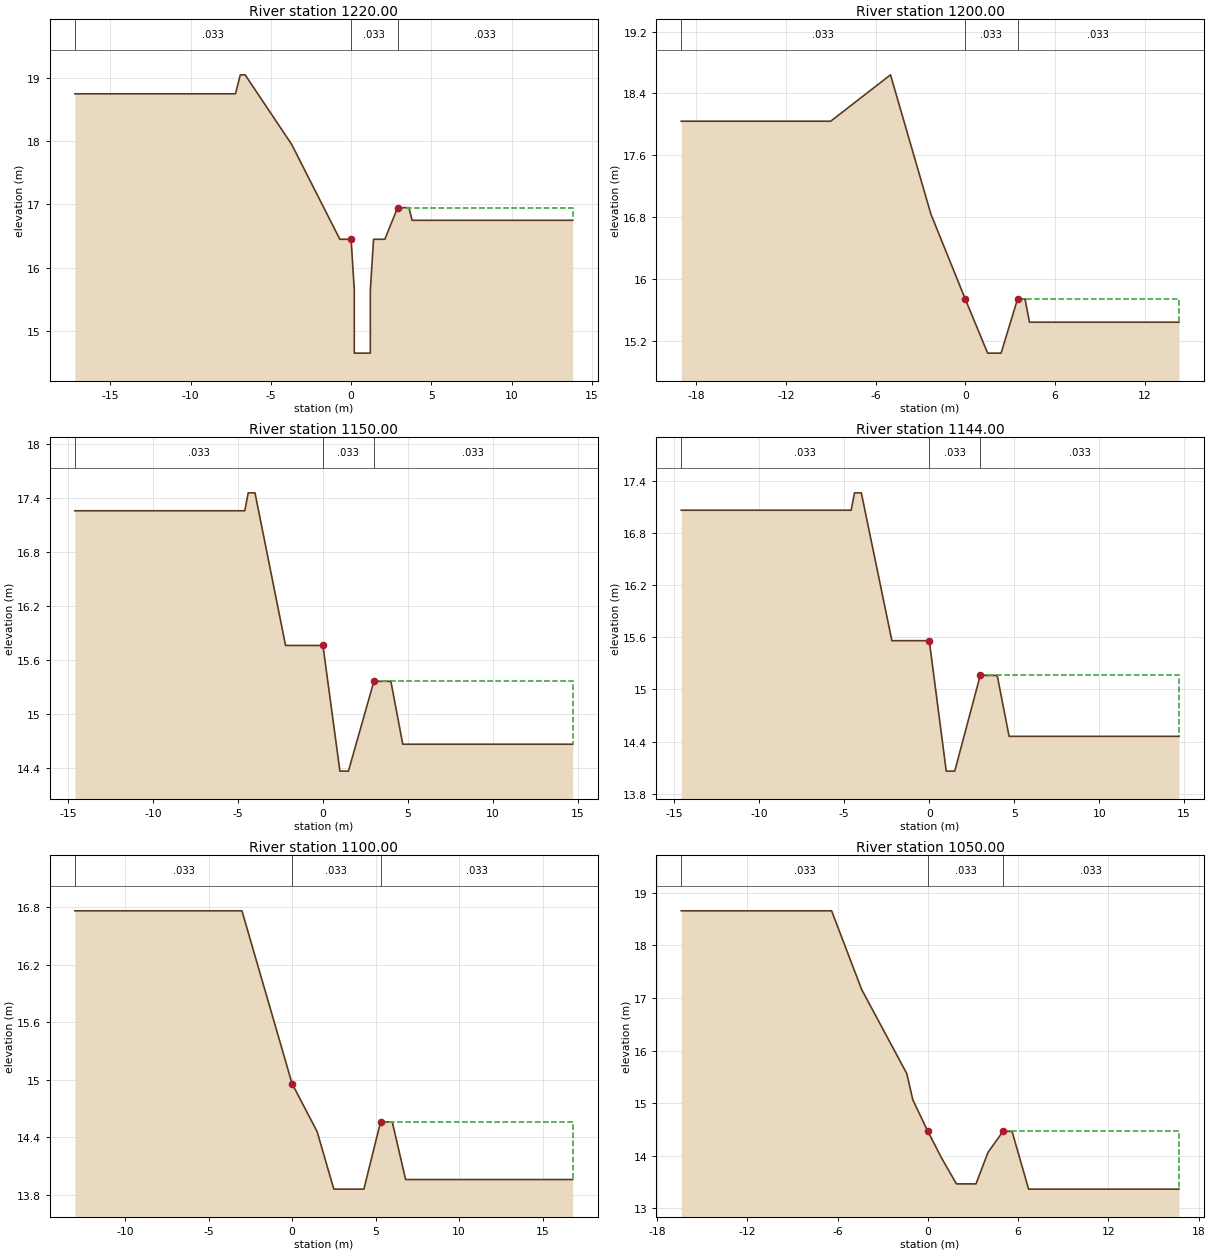
Type RM Length L Ch R = 1 ,1220.00 ,20,20,20
BEGIN DESCRIPTION:
24.02
END DESCRIPTION:
#Sta/Elev= 17
   -17.2   18.75    -7.2   18.75    -6.9   19.05    -6.6   19.05    -3.7   17.95
     -.7   16.45       0   16.45      .2   15.65      .2   14.65     1.2   14.65
     1.2   15.65     1.4   16.45     2.1   16.45     2.9   16.95     3.6   16.95
     3.8   16.75    13.8   16.75
#Mann= 3 , 0 , 0
   -17.2    .033       0       0    .033       0     2.9    .033       0
#XS Ineff= 2 , 0
               0   16.45     2.9           16.95
Permanent Ineff=
       F       F
Bank Sta=0,2.9
XS Rating Curve= 0
Exp/Cntr=.3,.1

Type RM Length L Ch R = 1 ,1200.00 ,50,50,50
BEGIN DESCRIPTION:
24
END DESCRIPTION:
#Sta/Elev= 11
     -19   18.04      -9   18.04      -5   18.64    -2.3   16.84       0   15.74
     1.5   15.04     2.4   15.04     3.5   15.74       4   15.74     4.3   15.44
    14.3   15.44
#Mann= 3 , 0 , 0
     -19    .033       0       0    .033       0     3.5    .033       0
#XS Ineff= 2 , 0
               0   15.74     3.5           15.74
Permanent Ineff=
       F       F
Bank Sta=0,3.5
XS Rating Curve= 0
Exp/Cntr=.3,.1

Type RM Length L Ch R = 1 ,1150.00 ,6,6,6
BEGIN DESCRIPTION:
23
END DESCRIPTION:
#Sta/Elev= 12
   -14.6   17.26    -4.6   17.26    -4.4   17.46      -4   17.46    -2.2   15.76
       0   15.76       1   14.36     1.5   14.36       3   15.36       4   15.36
     4.7   14.66    14.7   14.66
#Mann= 3 , 0 , 0
   -14.6    .033       0       0    .033       0       3    .033       0
#XS Ineff= 2 , 0
               0   15.76       3           15.36
Permanent Ineff=
       F       F
Bank Sta=0,3
XS Rating Curve= 0
Exp/Cntr=.3,.1

Type RM Length L Ch R = 1 ,1144.00 ,44,44,44
BEGIN DESCRIPTION:
22.044
END DESCRIPTION:
#Sta/Elev= 12
   -14.6   17.06    -4.6   17.06    -4.4   17.26      -4   17.26    -2.2   15.56
       0   15.56       1   14.06     1.5   14.06       3   15.16       4   15.16
     4.7   14.46    14.7   14.46
#Mann= 3 , 0 , 0
   -14.6    .033       0       0    .033       0       3    .033       0
#XS Ineff= 2 , 0
               0   15.56       3           15.16
Permanent Ineff=
       F       F
Bank Sta=0,3
XS Rating Curve= 0
Exp/Cntr=.3,.1

Type RM Length L Ch R = 1 ,1100.00 ,50,50,50
BEGIN DESCRIPTION:
22
END DESCRIPTION:
#Sta/Elev= 10
     -13   16.76      -3   16.76       0   14.96     1.5   14.46     2.5   13.86
     4.3   13.86     5.3   14.56       6   14.56     6.8   13.96    16.8   13.96
#Mann= 3 , 0 , 0
     -13    .033       0       0    .033       0     5.3    .033       0
#XS Ineff= 2 , 0
               0   14.96     5.3           14.56
Permanent Ineff=
       F       F
Bank Sta=0,5.3
XS Rating Curve= 0
Exp/Cntr=.3,.1

Type RM Length L Ch R = 1 ,1050.00 ,50,50,50
BEGIN DESCRIPTION:
21
END DESCRIPTION:
#Sta/Elev= 14
   -16.4   18.66    -6.4   18.66    -4.4   17.16    -1.4   15.56      -1   15.06
       0   14.46      .9   13.96     1.9   13.46     3.2   13.46       4   14.06
       5   14.46     5.6   14.46     6.7   13.36    16.7   13.36
#Mann= 3 , 0 , 0
   -16.4    .033       0       0    .033       0       5    .033       0
#XS Ineff= 2 , 0
               0   14.46       5           14.46
Permanent Ineff=
       F       F
Bank Sta=0,5
XS Rating Curve= 0
Exp/Cntr=.3,.1

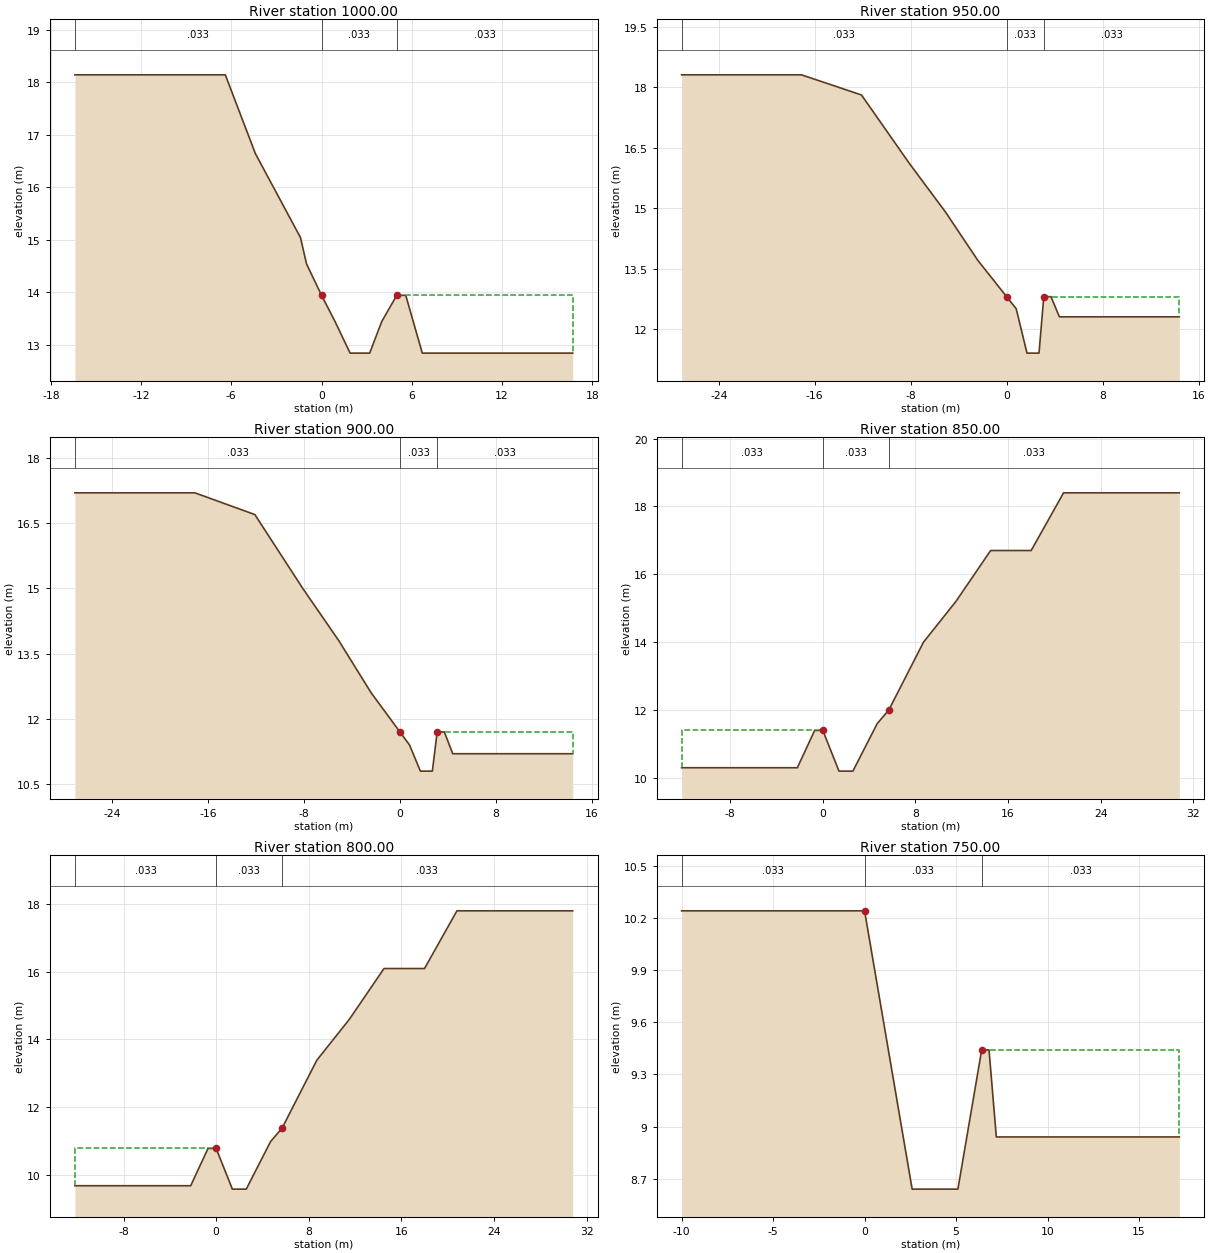
Type RM Length L Ch R = 1 ,1000.00 ,50,50,50
BEGIN DESCRIPTION:
20
END DESCRIPTION:
#Sta/Elev= 14
   -16.4   18.14    -6.4   18.14    -4.4   16.64    -1.4   15.04      -1   14.54
       0   13.94      .9   13.44     1.9   12.84     3.2   12.84       4   13.44
       5   13.94     5.6   13.94     6.7   12.84    16.7   12.84
#Mann= 3 , 0 , 0
   -16.4    .033       0       0    .033       0       5    .033       0
#XS Ineff= 2 , 0
               0   13.94       5           13.94
Permanent Ineff=
       F       F
Bank Sta=0,5
XS Rating Curve= 0
Exp/Cntr=.3,.1

Type RM Length L Ch R = 1 ,950.00  ,50,50,50
BEGIN DESCRIPTION:
19
END DESCRIPTION:
#Sta/Elev= 14
   -27.1   18.31   -17.1   18.31   -12.1   17.81    -8.1   16.11    -5.1   14.91
    -2.4   13.71       0   12.81      .8   12.51     1.7   11.41     2.7   11.41
     3.1   12.81     3.7   12.81     4.4   12.31    14.4   12.31
#Mann= 3 , 0 , 0
   -27.1    .033       0       0    .033       0     3.1    .033       0
#XS Ineff= 2 , 0
               0   12.81     3.1           12.81
Permanent Ineff=
       F       F
Bank Sta=0,3.1
XS Rating Curve= 0
Exp/Cntr=.3,.1

Type RM Length L Ch R = 1 ,900.00  ,50,50,50
BEGIN DESCRIPTION:
18
END DESCRIPTION:
#Sta/Elev= 14
   -27.1    17.2   -17.1    17.2   -12.1    16.7    -8.1      15    -5.1    13.8
    -2.4    12.6       0    11.7      .8    11.4     1.7    10.8     2.7    10.8
     3.1    11.7     3.7    11.7     4.4    11.2    14.4    11.2
#Mann= 3 , 0 , 0
   -27.1    .033       0       0    .033       0     3.1    .033       0
#XS Ineff= 2 , 0
               0    11.7     3.1            11.7
Permanent Ineff=
       F       F
Bank Sta=0,3.1
XS Rating Curve= 0
Exp/Cntr=.3,.1

Type RM Length L Ch R = 1 ,850.00  ,50,50,50
BEGIN DESCRIPTION:
17
END DESCRIPTION:
#Sta/Elev= 14
   -12.2    10.3    -2.2    10.3     -.7    11.4       0    11.4     1.4    10.2
     2.6    10.2     4.7    11.6     5.7      12     8.7      14    11.5    15.2
    14.5    16.7      18    16.7    20.8    18.4    30.8    18.4
#Mann= 3 , 0 , 0
   -12.2    .033       0       0    .033       0     5.7    .033       0
#XS Ineff= 2 , 0
               0    11.4     5.7              12
Permanent Ineff=
       F       F
Bank Sta=0,5.7
XS Rating Curve= 0
Exp/Cntr=.3,.1

Type RM Length L Ch R = 1 ,800.00  ,50,50,50
BEGIN DESCRIPTION:
16
END DESCRIPTION:
#Sta/Elev= 14
   -12.2    9.69    -2.2    9.69     -.7   10.79       0   10.79     1.4    9.59
     2.6    9.59     4.7   10.99     5.7   11.39     8.7   13.39    11.5   14.59
    14.5   16.09      18   16.09    20.8   17.79    30.8   17.79
#Mann= 3 , 0 , 0
   -12.2    .033       0       0    .033       0     5.7    .033       0
#XS Ineff= 2 , 0
               0   10.79     5.7           11.39
Permanent Ineff=
       F       F
Bank Sta=0,5.7
XS Rating Curve= 0
Exp/Cntr=.3,.1

Type RM Length L Ch R = 1 ,750.00  ,50,50,50
BEGIN DESCRIPTION:
15
END DESCRIPTION:
#Sta/Elev= 8
     -10   10.24       0   10.24     2.6    8.64     5.1    8.64     6.4    9.44
     6.8    9.44     7.2    8.94    17.2    8.94
#Mann= 3 , 0 , 0
     -10    .033       0       0    .033       0     6.4    .033       0
#XS Ineff= 2 , 0
               0   10.24     6.4            9.44
Permanent Ineff=
       F       F
Bank Sta=0,6.4
XS Rating Curve= 0
Exp/Cntr=.3,.1

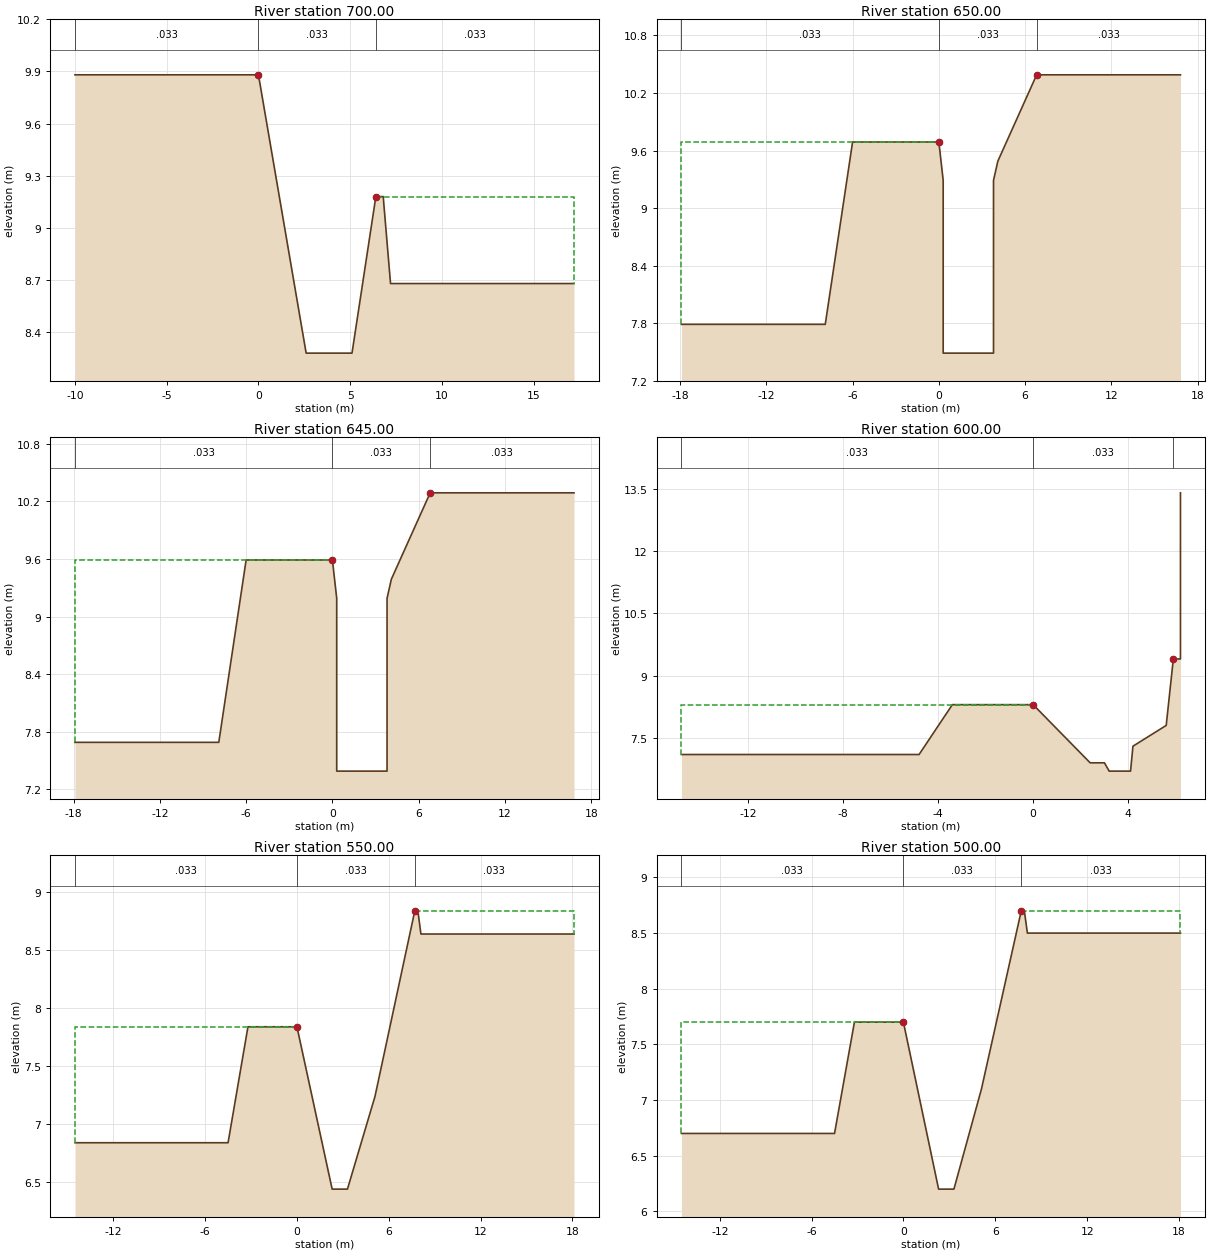
Type RM Length L Ch R = 1 ,700.00  ,50,50,50
BEGIN DESCRIPTION:
14
END DESCRIPTION:
#Sta/Elev= 8
     -10    9.88       0    9.88     2.6    8.28     5.1    8.28     6.4    9.18
     6.8    9.18     7.2    8.68    17.2    8.68
#Mann= 3 , 0 , 0
     -10    .033       0       0    .033       0     6.4    .033       0
#XS Ineff= 2 , 0
               0    9.88     6.4            9.18
Permanent Ineff=
       F       F
Bank Sta=0,6.4
XS Rating Curve= 0
Exp/Cntr=.3,.1

Type RM Length L Ch R = 1 ,650.00  ,5,5,5
BEGIN DESCRIPTION:
13
END DESCRIPTION:
#Sta/Elev= 11
   -17.9    7.79    -7.9    7.79      -6    9.69       0    9.69      .3    9.29
      .3    7.49     3.8    7.49     3.8    9.29     4.1    9.49     6.8   10.39
    16.8   10.39
#Mann= 3 , 0 , 0
   -17.9    .033       0       0    .033       0     6.8    .033       0
#XS Ineff= 2 , 0
               0    9.69     6.8           10.39
Permanent Ineff=
       F       F
Bank Sta=0,6.8
XS Rating Curve= 0
Exp/Cntr=.3,.1

Type RM Length L Ch R = 1 ,645.00  ,45,45,45
BEGIN DESCRIPTION:
12.045
END DESCRIPTION:
#Sta/Elev= 11
   -17.9    7.69    -7.9    7.69      -6    9.59       0    9.59      .3    9.19
      .3    7.39     3.8    7.39     3.8    9.19     4.1    9.39     6.8   10.29
    16.8   10.29
#Mann= 3 , 0 , 0
   -17.9    .033       0       0    .033       0     6.8    .033       0
#XS Ineff= 2 , 0
               0    9.59     6.8           10.29
Permanent Ineff=
       F       F
Bank Sta=0,6.8
XS Rating Curve= 0
Exp/Cntr=.3,.1

Type RM Length L Ch R = 1 ,600.00  ,50,50,50
BEGIN DESCRIPTION:
12
END DESCRIPTION:
#Sta/Elev= 13
   -14.8     7.1    -4.8     7.1    -3.4     8.3       0     8.3     2.4     6.9
       3     6.9     3.2     6.7     4.1     6.7     4.2     7.3     5.6     7.8
     5.9     9.4     6.2     9.4     6.2    13.4
#Mann= 3 , 0 , 0
   -14.8    .033       0       0    .033       0     5.9    .033       0
#XS Ineff= 2 , 0
               0     8.3     5.9             9.4
Permanent Ineff=
       F       F
Bank Sta=0,5.9
XS Rating Curve= 0
Exp/Cntr=.3,.1

Type RM Length L Ch R = 1 ,550.00  ,50,50,50
BEGIN DESCRIPTION:
11
END DESCRIPTION:
#Sta/Elev= 11
   -14.5    6.84    -4.5    6.84    -3.2    7.84       0    7.84     2.3    6.44
     3.3    6.44     5.1    7.24     7.7    8.84     7.9    8.84     8.1    8.64
    18.1    8.64
#Mann= 3 , 0 , 0
   -14.5    .033       0       0    .033       0     7.7    .033       0
#XS Ineff= 2 , 0
               0    7.84     7.7            8.84
Permanent Ineff=
       F       F
Bank Sta=0,7.7
XS Rating Curve= 0
Exp/Cntr=.3,.1

Type RM Length L Ch R = 1 ,500.00  ,10,10,10
BEGIN DESCRIPTION:
10
END DESCRIPTION:
#Sta/Elev= 11
   -14.5     6.7    -4.5     6.7    -3.2     7.7       0     7.7     2.3     6.2
     3.3     6.2     5.1     7.1     7.7     8.7     7.9     8.7     8.1     8.5
    18.1     8.5
#Mann= 3 , 0 , 0
   -14.5    .033       0       0    .033       0     7.7    .033       0
#XS Ineff= 2 , 0
               0     7.7     7.7             8.7
Permanent Ineff=
       F       F
Bank Sta=0,7.7
XS Rating Curve= 0
Exp/Cntr=.3,.1

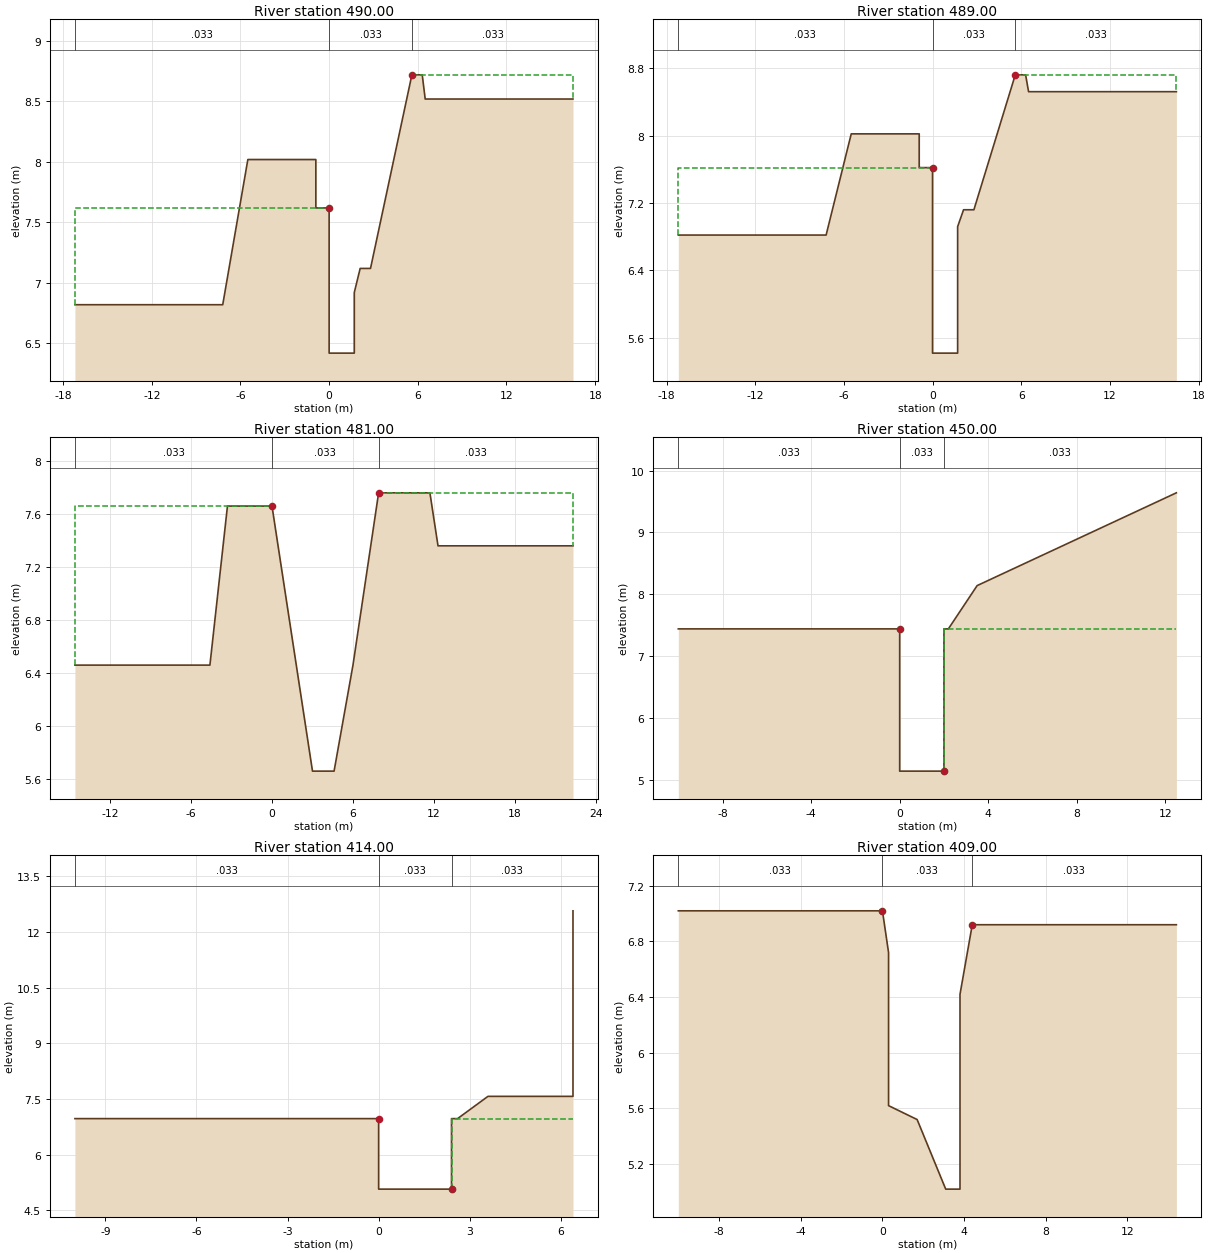
Type RM Length L Ch R = 1 ,490.00  ,1,1,1
BEGIN DESCRIPTION:
9.04
END DESCRIPTION:
#Sta/Elev= 15
   -17.2    6.82    -7.2    6.82    -5.5    8.02     -.9    8.02     -.9    7.62
       0    7.62       0    6.42     1.7    6.42     1.7    6.92     2.1    7.12
     2.8    7.12     5.6    8.72     6.3    8.72     6.5    8.52    16.5    8.52
#Mann= 3 , 0 , 0
   -17.2    .033       0       0    .033       0     5.6    .033       0
#XS Ineff= 2 , 0
               0    7.62     5.6            8.72
Permanent Ineff=
       F       F
Bank Sta=0,5.6
XS Rating Curve= 0
Exp/Cntr=.3,.1

Type RM Length L Ch R = 1 ,489.00  ,8,8,8
BEGIN DESCRIPTION:
9.039
END DESCRIPTION:
#Sta/Elev= 17
   -17.2    6.82    -7.2    6.82    -5.5    8.02     -.9    8.02     -.9    7.62
       0    7.62       0    6.42       0    5.42     1.7    5.42     1.7    6.42
     1.7    6.92     2.1    7.12     2.8    7.12     5.6    8.72     6.3    8.72
     6.5    8.52    16.5    8.52
#Mann= 3 , 0 , 0
   -17.2    .033       0       0    .033       0     5.6    .033       0
#XS Ineff= 2 , 0
               0    7.62     5.6            8.72
Permanent Ineff=
       F       F
Bank Sta=0,5.6
XS Rating Curve= 0
Exp/Cntr=.3,.1

Type RM Length L Ch R = 1 ,481.00  ,31,31,31
BEGIN DESCRIPTION:
9.031
END DESCRIPTION:
#Sta/Elev= 11
   -14.6    6.46    -4.6    6.46    -3.3    7.66       0    7.66       3    5.66
     4.6    5.66       6    6.46     7.9    7.76    11.7    7.76    12.3    7.36
    22.3    7.36
#Mann= 3 , 0 , 0
   -14.6    .033       0       0    .033       0     7.9    .033       0
#XS Ineff= 2 , 0
               0    7.66     7.9            7.76
Permanent Ineff=
       F       F
Bank Sta=0,7.9
XS Rating Curve= 0
Exp/Cntr=.3,.1

Type RM Length L Ch R = 1 ,450.00  ,36,36,36
BEGIN DESCRIPTION:
9
END DESCRIPTION:
#Sta/Elev= 10
     -10    7.44       0    7.44       0    5.14       2    5.14       2    7.44
     2.2    7.44     3.5    8.14     6.5    8.64     9.5    9.14    12.5    9.64
#Mann= 3 , 0 , 0
     -10    .033       0       0    .033       0       2    .033       0
#XS Ineff= 2 , 0
               0    7.44       2            7.44
Permanent Ineff=
       F       F
Bank Sta=0,2
XS Rating Curve= 0
Exp/Cntr=.3,.1

Type RM Length L Ch R = 1 ,414.00  ,5,5,5
BEGIN DESCRIPTION:
8.014
END DESCRIPTION:
#Sta/Elev= 9
     -10    6.97       0    6.97       0    5.07     2.4    5.07     2.4    6.97
     2.6    6.97     3.6    7.57     6.4    7.57     6.4   12.57
#Mann= 3 , 0 , 0
     -10    .033       0       0    .033       0     2.4    .033       0
#XS Ineff= 2 , 0
               0    6.97     2.4            6.97
Permanent Ineff=
       F       F
Bank Sta=0,2.4
XS Rating Curve= 0
Exp/Cntr=.3,.1

Type RM Length L Ch R = 1 ,409.00  ,9,9,9
BEGIN DESCRIPTION:
8.009
END DESCRIPTION:
#Sta/Elev= 10
     -10    7.02       0    7.02      .3    6.72      .3    5.62     1.7    5.52
     3.1    5.02     3.8    5.02     3.8    6.42     4.4    6.92    14.4    6.92
#Mann= 3 , 0 , 0
     -10    .033       0       0    .033       0     4.4    .033       0
#XS Ineff= 2 , 0
               0    7.02     4.4            6.92
Permanent Ineff=
       F       F
Bank Sta=0,4.4
XS Rating Curve= 0
Exp/Cntr=.3,.1

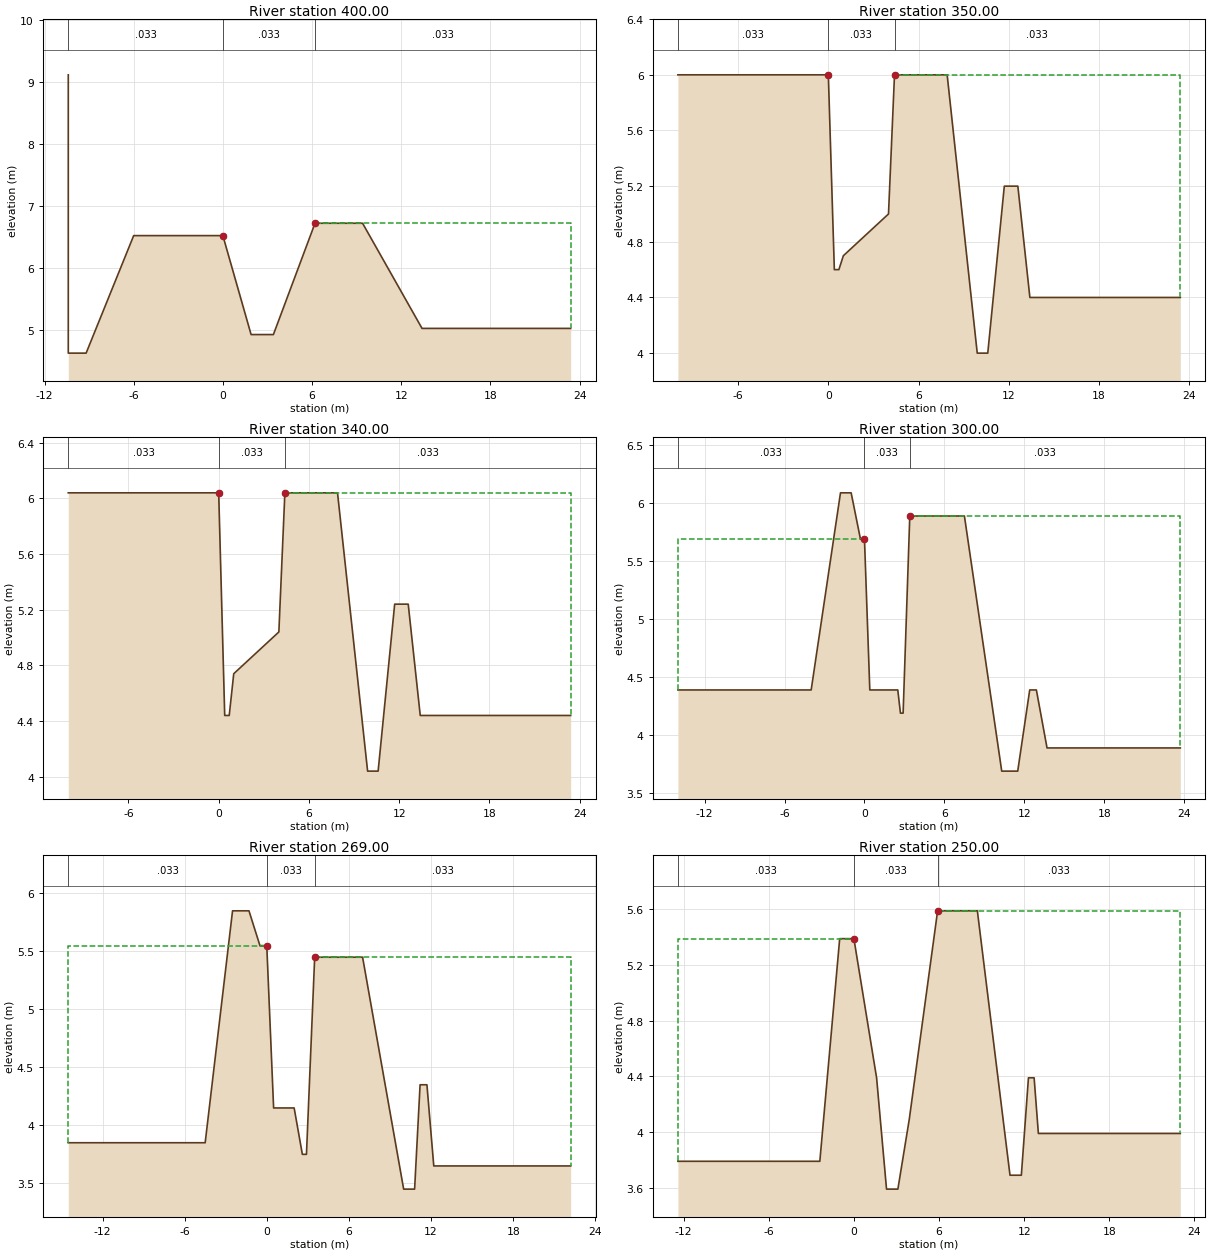
Type RM Length L Ch R = 1 ,400.00  ,50,50,50
BEGIN DESCRIPTION:
8
END DESCRIPTION:
#Sta/Elev= 11
   -10.4    9.12   -10.4    4.62    -9.2    4.62      -6    6.52       0    6.52
     1.9    4.92     3.4    4.92     6.2    6.72     9.4    6.72    13.4    5.02
    23.4    5.02
#Mann= 3 , 0 , 0
   -10.4    .033       0       0    .033       0     6.2    .033       0
#XS Ineff= 2 , 0
               0    6.52     6.2            6.72
Permanent Ineff=
       F       F
Bank Sta=0,6.2
XS Rating Curve= 0
Exp/Cntr=.3,.1

Type RM Length L Ch R = 1 ,350.00  ,10,10,10
BEGIN DESCRIPTION:
7
END DESCRIPTION:
#Sta/Elev= 14
     -10       6       0       6      .4     4.6      .7     4.6       1     4.7
       4       5     4.4       6     7.9       6     9.9       4    10.6       4
    11.7     5.2    12.6     5.2    13.4     4.4    23.4     4.4
#Mann= 3 , 0 , 0
     -10    .033       0       0    .033       0     4.4    .033       0
#XS Ineff= 2 , 0
               0       6     4.4               6
Permanent Ineff=
       F       F
Bank Sta=0,4.4
XS Rating Curve= 0
Exp/Cntr=.3,.1

Type RM Length L Ch R = 1 ,340.00  ,40,40,40
BEGIN DESCRIPTION:
6.04
END DESCRIPTION:
#Sta/Elev= 14
     -10    6.04       0    6.04      .4    4.44      .7    4.44       1    4.74
       4    5.04     4.4    6.04     7.9    6.04     9.9    4.04    10.6    4.04
    11.7    5.24    12.6    5.24    13.4    4.44    23.4    4.44
#Mann= 3 , 0 , 0
     -10    .033       0       0    .033       0     4.4    .033       0
#XS Ineff= 2 , 0
               0    6.04     4.4            6.04
Permanent Ineff=
       F       F
Bank Sta=0,4.4
XS Rating Curve= 0
Exp/Cntr=.3,.1

Type RM Length L Ch R = 1 ,300.00  ,31,31,31
BEGIN DESCRIPTION:
6
END DESCRIPTION:
#Sta/Elev= 19
     -14    4.39      -4    4.39    -1.8    6.09      -1    6.09     -.3    5.69
       0    5.69      .4    4.39     2.5    4.39     2.7    4.19     2.9    4.19
     3.4    5.89     3.8    5.89     7.5    5.89    10.3    3.69    11.5    3.69
    12.4    4.39    12.9    4.39    13.7    3.89    23.7    3.89
#Mann= 3 , 0 , 0
     -14    .033       0       0    .033       0     3.4    .033       0
#XS Ineff= 2 , 0
               0    5.69     3.4            5.89
Permanent Ineff=
       F       F
Bank Sta=0,3.4
XS Rating Curve= 0
Exp/Cntr=.3,.1

Type RM Length L Ch R = 1 ,269.00  ,19,19,19
BEGIN DESCRIPTION:
5.019
END DESCRIPTION:
#Sta/Elev= 18
   -14.5    3.85    -4.5    3.85    -2.5    5.85    -1.3    5.85     -.5    5.55
       0    5.55      .5    4.15       2    4.15     2.6    3.75     2.9    3.75
     3.5    5.45       7    5.45      10    3.45    10.8    3.45    11.2    4.35
    11.7    4.35    12.2    3.65    22.2    3.65
#Mann= 3 , 0 , 0
   -14.5    .033       0       0    .033       0     3.5    .033       0
#XS Ineff= 2 , 0
               0    5.55     3.5            5.45
Permanent Ineff=
       F       F
Bank Sta=0,3.5
XS Rating Curve= 0
Exp/Cntr=.3,.1

Type RM Length L Ch R = 1 ,250.00  ,50,50,50
BEGIN DESCRIPTION:
5
END DESCRIPTION:
#Sta/Elev= 16
   -12.4    3.79    -2.4    3.79      -1    5.39       0    5.39     1.6    4.39
     2.3    3.59     3.1    3.59     3.9    4.09     5.9    5.59     8.7    5.59
      11    3.69    11.8    3.69    12.3    4.39    12.7    4.39      13    3.99
      23    3.99
#Mann= 3 , 0 , 0
   -12.4    .033       0       0    .033       0     5.9    .033       0
#XS Ineff= 2 , 0
               0    5.39     5.9            5.59
Permanent Ineff=
       F       F
Bank Sta=0,5.9
XS Rating Curve= 0
Exp/Cntr=.3,.1

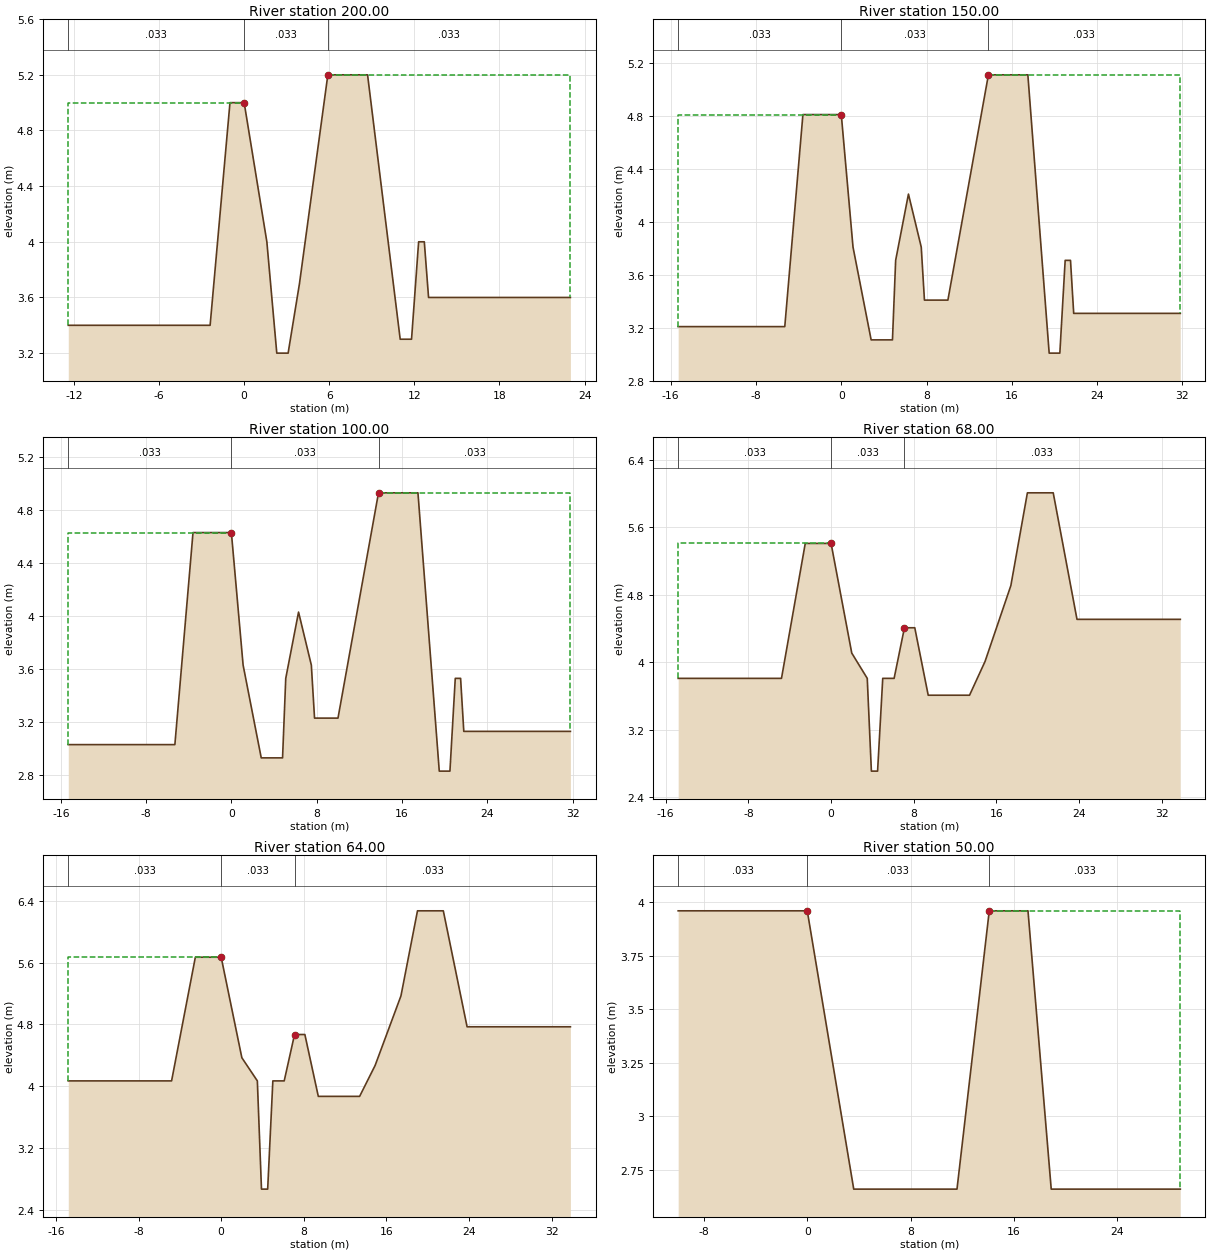
Type RM Length L Ch R = 1 ,200.00  ,50,50,50
BEGIN DESCRIPTION:
4
END DESCRIPTION:
#Sta/Elev= 16
   -12.4     3.4    -2.4     3.4      -1       5       0       5     1.6       4
     2.3     3.2     3.1     3.2     3.9     3.7     5.9     5.2     8.7     5.2
      11     3.3    11.8     3.3    12.3       4    12.7       4      13     3.6
      23     3.6
#Mann= 3 , 0 , 0
   -12.4    .033       0       0    .033       0     5.9    .033       0
#XS Ineff= 2 , 0
               0       5     5.9             5.2
Permanent Ineff=
       F       F
Bank Sta=0,5.9
XS Rating Curve= 0
Exp/Cntr=.3,.1

Type RM Length L Ch R = 1 ,150.00  ,50,50,50
BEGIN DESCRIPTION:
3
END DESCRIPTION:
#Sta/Elev= 20
   -15.3    3.21    -5.3    3.21    -3.6    4.81       0    4.81     1.1    3.81
     2.8    3.11     4.8    3.11     5.1    3.71     6.3    4.21     7.5    3.81
     7.8    3.41      10    3.41    13.8    5.11    17.5    5.11    19.5    3.01
    20.5    3.01      21    3.71    21.5    3.71    21.8    3.31    31.8    3.31
#Mann= 3 , 0 , 0
   -15.3    .033       0       0    .033       0    13.8    .033       0
#XS Ineff= 2 , 0
               0    4.81    13.8            5.11
Permanent Ineff=
       F       F
Bank Sta=0,13.8
XS Rating Curve= 0
Exp/Cntr=.3,.1

Type RM Length L Ch R = 1 ,100.00  ,32,32,32
BEGIN DESCRIPTION:
2
END DESCRIPTION:
#Sta/Elev= 20
   -15.3    3.03    -5.3    3.03    -3.6    4.63       0    4.63     1.1    3.63
     2.8    2.93     4.8    2.93     5.1    3.53     6.3    4.03     7.5    3.63
     7.8    3.23      10    3.23    13.8    4.93    17.5    4.93    19.5    2.83
    20.5    2.83      21    3.53    21.5    3.53    21.8    3.13    31.8    3.13
#Mann= 3 , 0 , 0
   -15.3    .033       0       0    .033       0    13.8    .033       0
#XS Ineff= 2 , 0
               0    4.63    13.8            4.93
Permanent Ineff=
       F       F
Bank Sta=0,13.8
XS Rating Curve= 0
Exp/Cntr=.3,.1

Type RM Length L Ch R = 1 ,68.00   ,4,4,4
BEGIN DESCRIPTION:
1.018
END DESCRIPTION:
#Sta/Elev= 20
   -14.8    3.81    -4.8    3.81    -2.5    5.41       0    5.41       2    4.11
     3.5    3.81     3.9    2.71     4.5    2.71       5    3.81     6.1    3.81
     7.1    4.41     8.1    4.41     9.4    3.61    13.4    3.61    14.9    4.01
    17.4    4.91      19    6.01    21.5    6.01    23.8    4.51    33.8    4.51
#Mann= 3 , 0 , 0
   -14.8    .033       0       0    .033       0     7.1    .033       0
#XS Ineff= 2 , 0
               0    5.41     7.1            4.41
Permanent Ineff=
       F       F
Bank Sta=0,7.1
XS Rating Curve= 0
Exp/Cntr=.3,.1

Type RM Length L Ch R = 1 ,64.00   ,14,14,14
BEGIN DESCRIPTION:
1.014
END DESCRIPTION:
#Sta/Elev= 20
   -14.8    4.07    -4.8    4.07    -2.5    5.67       0    5.67       2    4.37
     3.5    4.07     3.9    2.67     4.5    2.67       5    4.07     6.1    4.07
     7.1    4.67     8.1    4.67     9.4    3.87    13.4    3.87    14.9    4.27
    17.4    5.17      19    6.27    21.5    6.27    23.8    4.77    33.8    4.77
#Mann= 3 , 0 , 0
   -14.8    .033       0       0    .033       0     7.1    .033       0
#XS Ineff= 2 , 0
               0    5.67     7.1            4.67
Permanent Ineff=
       F       F
Bank Sta=0,7.1
XS Rating Curve= 0
Exp/Cntr=.3,.1

Type RM Length L Ch R = 1 ,50.00   ,50,50,50
BEGIN DESCRIPTION:
1
END DESCRIPTION:
#Sta/Elev= 8
     -10    3.96       0    3.96     3.6    2.66    11.6    2.66    14.1    3.96
    17.1    3.96    18.9    2.66    28.9    2.66
#Mann= 3 , 0 , 0
     -10    .033       0       0    .033       0    14.1    .033       0
#XS Ineff= 2 , 0
               0    3.96    14.1            3.96
Permanent Ineff=
       F       F
Bank Sta=0,14.1
XS Rating Curve= 0
Exp/Cntr=.3,.1

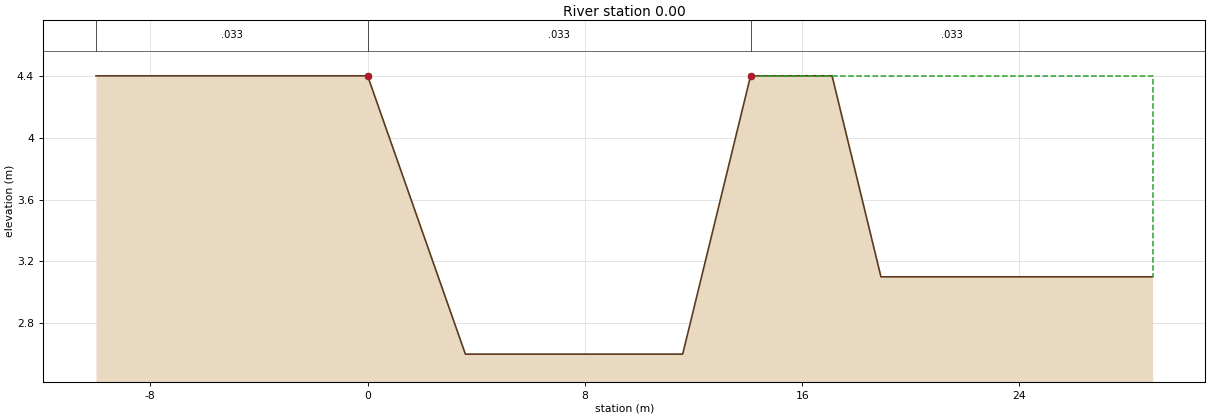
Type RM Length L Ch R = 1 ,0.00    ,0,0,0
BEGIN DESCRIPTION:
0
END DESCRIPTION:
#Sta/Elev= 8
     -10     4.4       0     4.4     3.6     2.6    11.6     2.6    14.1     4.4
    17.1     4.4    18.9     3.1    28.9     3.1
#Mann= 3 , 0 , 0
     -10    .033       0       0    .033       0    14.1    .033       0
#XS Ineff= 2 , 0
               0     4.4    14.1             4.4
Permanent Ineff=
       F       F
Bank Sta=0,14.1
XS Rating Curve= 0
Exp/Cntr=.3,.1

Chan Stop Cuts=-1