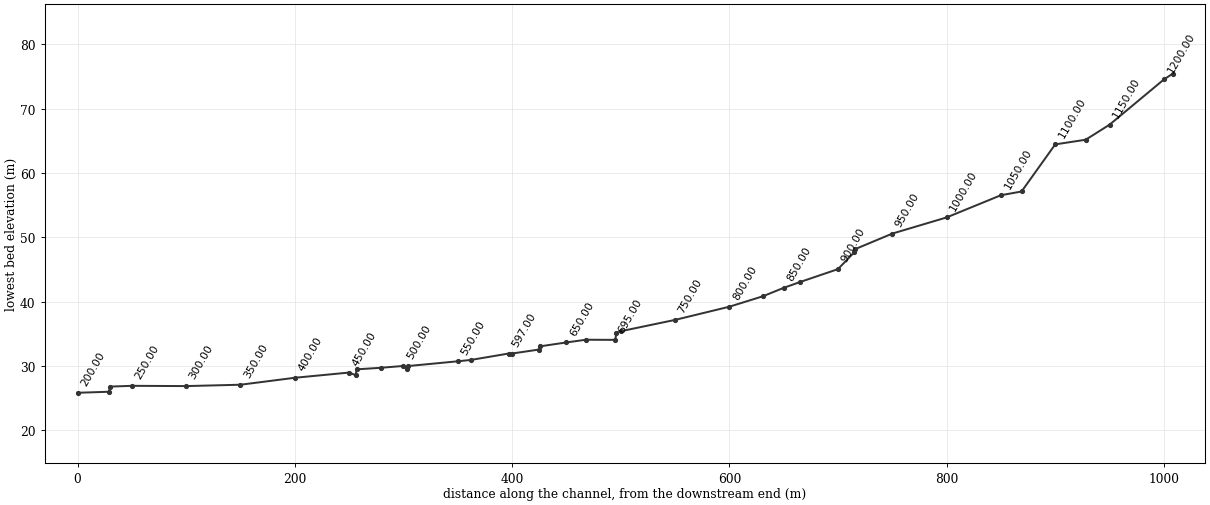
--- SIN.prj (project) ---

Proj Title=SIN
Current Plan=p01
Default Exp/Contr=.3,.1
SI Units
Geom File=g01
Flow File=f01
Plan File=p01
Y Axis Title=Elevation
X Axis Title(PF)=Main Channel Distance
X Axis Title(XS)=Station
BEGIN DESCRIPTION:
           BACK WATER COMPUTATION
      APPLICATION OF HEC-2 BY Samju Construction Engineering
      SINGOO-STREEM : 30 YR
END DESCRIPTION:
DSS Export Rating Curves= 0
DSS Export Rating Curve Sorted= 0
DSS Export Volume Flow Curves= 0
DXF OffsetX= 0
DXF OffsetY= 0
DXF ScaleX= 1
DXF ScaleY= 10

--- SIN.p01 (plan) ---

Plan Title=Imported Plan 01
Version=Version 3.0.1  Mar 2001
Short Identifier=Imported Pla
Geom File=g01
Flow File=f01
Subcritical Flow
K Sum by GR= 0
Std Step Tol= 0.003
Critical Tol= 0.003
Num of Std Step Trials= 20
Max Error Tol= 0.1
Flow Tol Ratio= 0.001
Split Flow NTrial= 30
Split Flow Tol= 0.02
Split Flow Ratio= 0.02
Log Output Level= 0
Friction Slope Method= 1
Unsteady Friction Slope Method= 2
Parabolic Critical Depth
Global Vel Dist= 0 , 0 , 0
Global Log Level= 0
CheckData=True
Encroach Param=-1 ,0,0, 0
Computation Interval=1HOUR
Output Interval=1HOUR
Run HTab= 0
Run UNet= 0
Run PostProcess= 0
UNET Theta= 1
UNET ZTol= 0.02
UNET ZSATol= 0.1
UNET MxIter= 20
UNET MaxInSteps= 20
UNET DtIC= 0
UNET DtMin= 0
UNET MaxCRTS= 20
UNET WFStab= 2
UNET SFStab= 1
UNET WFX= 1
UNET SFX= 1
UNET Convert EG Bridges=-1
UNET Use Existing IB Tables=-1
Instantaneous Interval=1HOUR
Write IC File= 0
Write Velocity= 0
Write Detailed= 0

--- SIN.f01 (steady flow) ---

Flow Title=Imported Flow 01
Version=Version 3.0.1  Mar 2001
Number of Profiles= 5
Profile Names=10YR,20YR,30YR,50YR,80YR
River Rch & RM=RIVER-1,Reach-1         ,1208.00
   11.89    13.1   13.81    14.7   15.52
Boundary for River Rch & Prof#=RIVER-1,Reach-1         , 1
Up Type= 0
Dn Type= 3
Dn Slope=.014
Boundary for River Rch & Prof#=RIVER-1,Reach-1         , 2
Up Type= 0
Dn Type= 3
Dn Slope=.014
Boundary for River Rch & Prof#=RIVER-1,Reach-1         , 3
Up Type= 0
Dn Type= 3
Dn Slope=.014
Boundary for River Rch & Prof#=RIVER-1,Reach-1         , 4
Up Type= 0
Dn Type= 3
Dn Slope=.014
Boundary for River Rch & Prof#=RIVER-1,Reach-1         , 5
Up Type= 0
Dn Type= 3
Dn Slope=.014
DSS Import GetInterval= 0
DSS Import GetPeak= 0
DSS Import FillOption= 0

--- SIN.g01 (geometry) ---

Geom Title=Imported Geom 01
Version=Version 3.0.1  Mar 2001

River Reach=RIVER-1         ,Reach-1
Reach XY= 2
              .5             .95              .5             .05

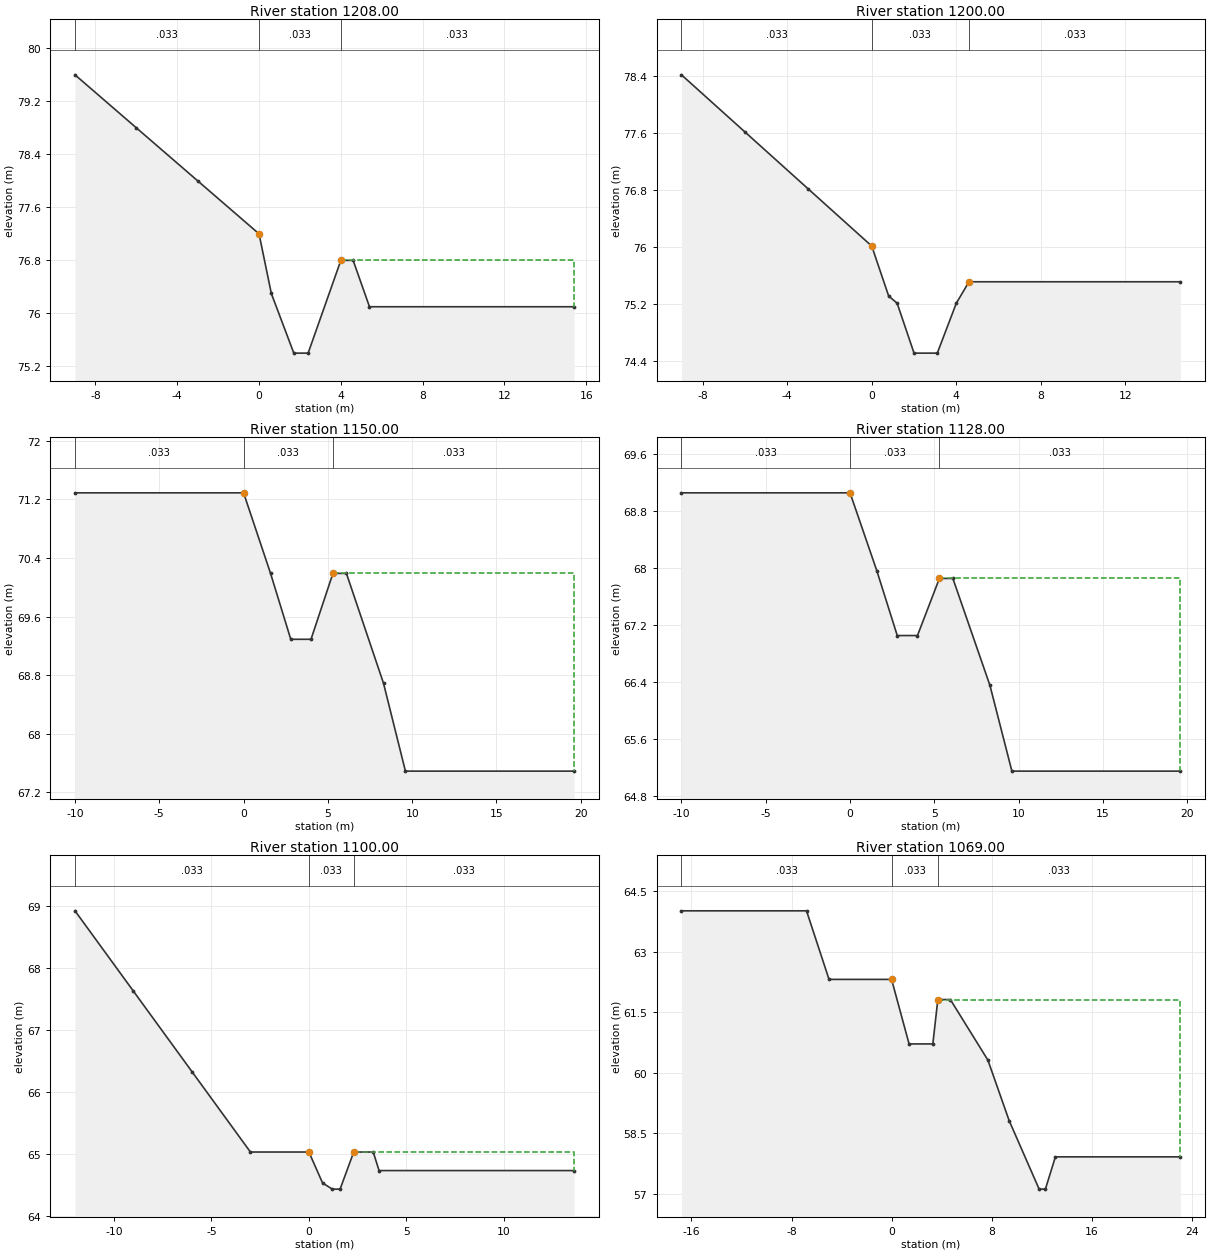
Type RM Length L Ch R = 1 ,1208.00 ,8,8,8
BEGIN DESCRIPTION:
24.008
END DESCRIPTION:
#Sta/Elev= 11
      -9    79.6      -6    78.8      -3      78       0    77.2      .6    76.3
     1.7    75.4     2.4    75.4       4    76.8     4.6    76.8     5.4    76.1
    15.4    76.1
#Mann= 3 , 0 , 0
      -9    .033       0       0    .033       0       4    .033       0
#XS Ineff= 2 , 0
               0    77.2       4            76.8
Permanent Ineff=
       F       F
Bank Sta=0,4
XS Rating Curve= 0
Exp/Cntr=.3,.1

Type RM Length L Ch R = 1 ,1200.00 ,50,50,50
BEGIN DESCRIPTION:
24
END DESCRIPTION:
#Sta/Elev= 11
      -9   78.41      -6   77.61      -3   76.81       0   76.01      .8   75.31
     1.2   75.21       2   74.51     3.1   74.51       4   75.21     4.6   75.51
    14.6   75.51
#Mann= 3 , 0 , 0
      -9    .033       0       0    .033       0     4.6    .033       0
#XS Ineff= 2 , 0
               0   76.01     4.6           75.51
Permanent Ineff=
       F       F
Bank Sta=0,4.6
XS Rating Curve= 0
Exp/Cntr=.3,.1

Type RM Length L Ch R = 1 ,1150.00 ,22,22,22
BEGIN DESCRIPTION:
23
END DESCRIPTION:
#Sta/Elev= 10
     -10   71.29       0   71.29     1.6   70.19     2.8   69.29       4   69.29
     5.3   70.19     6.1   70.19     8.3   68.69     9.6   67.49    19.6   67.49
#Mann= 3 , 0 , 0
     -10    .033       0       0    .033       0     5.3    .033       0
#XS Ineff= 2 , 0
               0   71.29     5.3           70.19
Permanent Ineff=
       F       F
Bank Sta=0,5.3
XS Rating Curve= 0
Exp/Cntr=.3,.1

Type RM Length L Ch R = 1 ,1128.00 ,28,28,28
BEGIN DESCRIPTION:
22.028
END DESCRIPTION:
#Sta/Elev= 10
     -10   69.05       0   69.05     1.6   67.95     2.8   67.05       4   67.05
     5.3   67.85     6.1   67.85     8.3   66.35     9.6   65.15    19.6   65.15
#Mann= 3 , 0 , 0
     -10    .033       0       0    .033       0     5.3    .033       0
#XS Ineff= 2 , 0
               0   69.05     5.3           67.85
Permanent Ineff=
       F       F
Bank Sta=0,5.3
XS Rating Curve= 0
Exp/Cntr=.3,.1

Type RM Length L Ch R = 1 ,1100.00 ,31,31,31
BEGIN DESCRIPTION:
22
END DESCRIPTION:
#Sta/Elev= 12
     -12   68.93      -9   67.63      -6   66.33      -3   65.03       0   65.03
      .7   64.53     1.2   64.43     1.6   64.43     2.3   65.03     3.3   65.03
     3.6   64.73    13.6   64.73
#Mann= 3 , 0 , 0
     -12    .033       0       0    .033       0     2.3    .033       0
#XS Ineff= 2 , 0
               0   65.03     2.3           65.03
Permanent Ineff=
       F       F
Bank Sta=0,2.3
XS Rating Curve= 0
Exp/Cntr=.3,.1

Type RM Length L Ch R = 1 ,1069.00 ,19,19,19
BEGIN DESCRIPTION:
21.019
END DESCRIPTION:
#Sta/Elev= 14
   -16.8   64.01    -6.8   64.01      -5   62.31       0   62.31     1.4   60.71
     3.3   60.71     3.7   61.81     4.7   61.81     7.7   60.31     9.4   58.81
    11.8   57.11    12.3   57.11    13.1   57.91    23.1   57.91
#Mann= 3 , 0 , 0
   -16.8    .033       0       0    .033       0     3.7    .033       0
#XS Ineff= 2 , 0
               0   62.31     3.7           61.81
Permanent Ineff=
       F       F
Bank Sta=0,3.7
XS Rating Curve= 0
Exp/Cntr=.3,.1

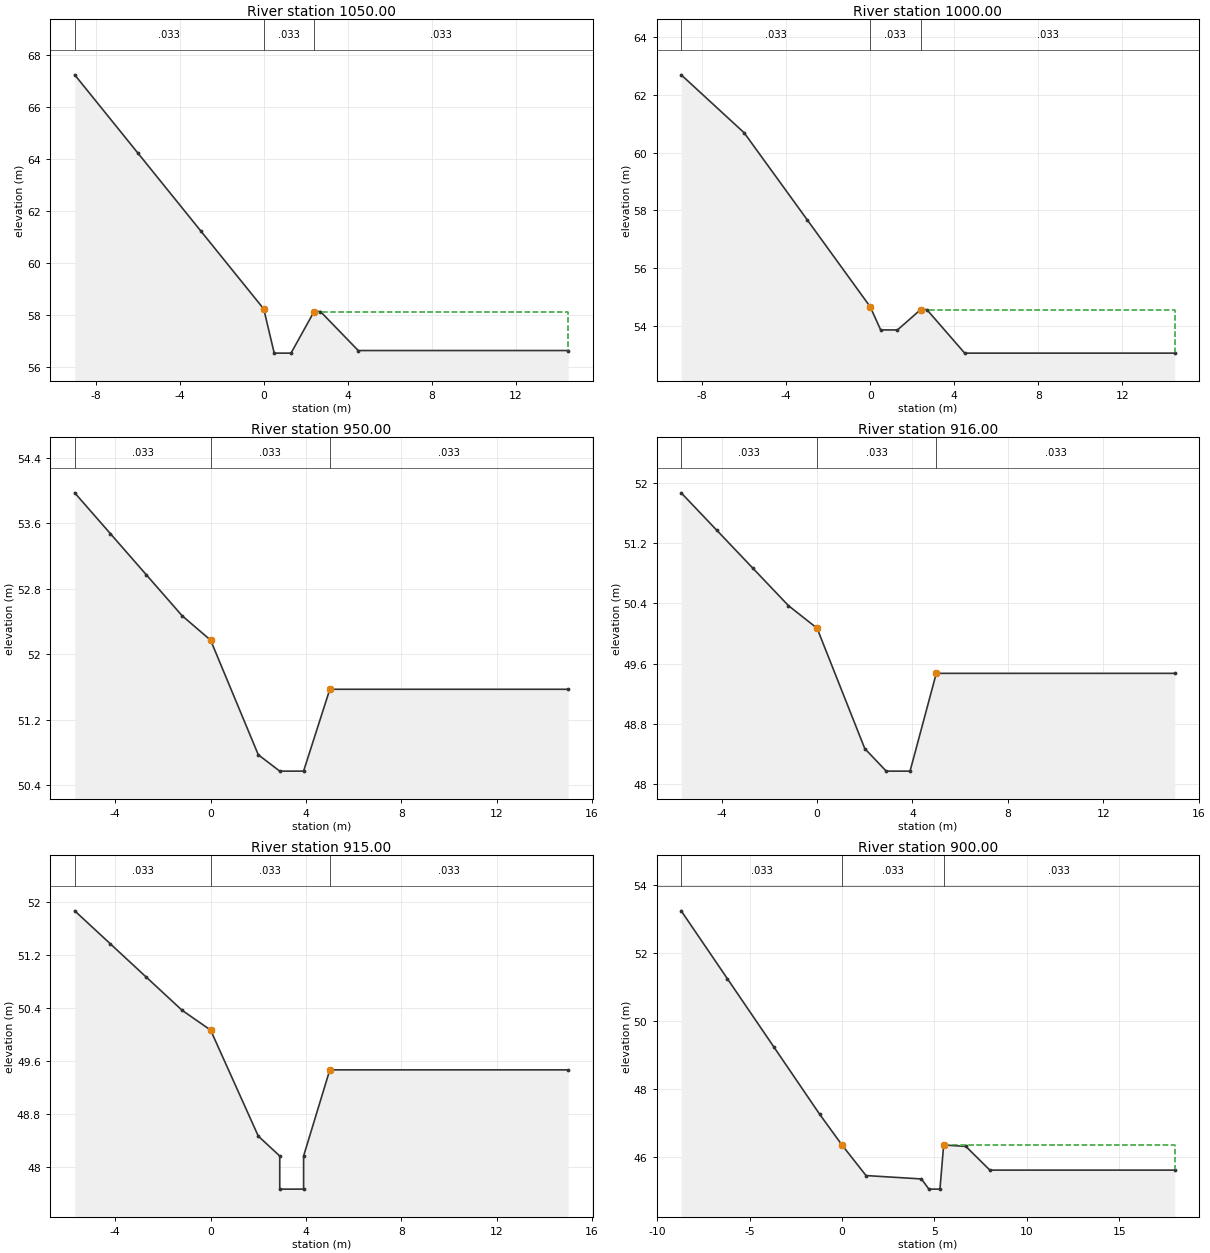
Type RM Length L Ch R = 1 ,1050.00 ,50,50,50
BEGIN DESCRIPTION:
21
END DESCRIPTION:
#Sta/Elev= 10
      -9   67.23      -6   64.23      -3   61.23       0   58.23      .5   56.53
     1.3   56.53     2.4   58.13     2.7   58.13     4.5   56.63    14.5   56.63
#Mann= 3 , 0 , 0
      -9    .033       0       0    .033       0     2.4    .033       0
#XS Ineff= 2 , 0
               0   58.23     2.4           58.13
Permanent Ineff=
       F       F
Bank Sta=0,2.4
XS Rating Curve= 0
Exp/Cntr=.3,.1

Type RM Length L Ch R = 1 ,1000.00 ,50,50,50
BEGIN DESCRIPTION:
20
END DESCRIPTION:
#Sta/Elev= 10
      -9   62.68      -6   60.68      -3   57.68       0   54.68      .5   53.88
     1.3   53.88     2.4   54.58     2.7   54.58     4.5   53.08    14.5   53.08
#Mann= 3 , 0 , 0
      -9    .033       0       0    .033       0     2.4    .033       0
#XS Ineff= 2 , 0
               0   54.68     2.4           54.58
Permanent Ineff=
       F       F
Bank Sta=0,2.4
XS Rating Curve= 0
Exp/Cntr=.3,.1

Type RM Length L Ch R = 1 ,950.00  ,34,34,34
BEGIN DESCRIPTION:
19
END DESCRIPTION:
#Sta/Elev= 10
    -5.7   53.97    -4.2   53.47    -2.7   52.97    -1.2   52.47       0   52.17
       2   50.77     2.9   50.57     3.9   50.57       5   51.57      15   51.57
#Mann= 3 , 0 , 0
    -5.7    .033       0       0    .033       0       5    .033       0
#XS Ineff= 2 , 0
               0   52.17       5           51.57
Permanent Ineff=
       F       F
Bank Sta=0,5
XS Rating Curve= 0
Exp/Cntr=.3,.1

Type RM Length L Ch R = 1 ,916.00  ,1,1,1
BEGIN DESCRIPTION:
18.016
END DESCRIPTION:
#Sta/Elev= 10
    -5.7   51.87    -4.2   51.37    -2.7   50.87    -1.2   50.37       0   50.07
       2   48.47     2.9   48.17     3.9   48.17       5   49.47      15   49.47
#Mann= 3 , 0 , 0
    -5.7    .033       0       0    .033       0       5    .033       0
#XS Ineff= 2 , 0
               0   50.07       5           49.47
Permanent Ineff=
       F       F
Bank Sta=0,5
XS Rating Curve= 0
Exp/Cntr=.3,.1

Type RM Length L Ch R = 1 ,915.00  ,15,15,15
BEGIN DESCRIPTION:
18.015
END DESCRIPTION:
#Sta/Elev= 12
    -5.7   51.87    -4.2   51.37    -2.7   50.87    -1.2   50.37       0   50.07
       2   48.47     2.9   48.17     2.9   47.67     3.9   47.67     3.9   48.17
       5   49.47      15   49.47
#Mann= 3 , 0 , 0
    -5.7    .033       0       0    .033       0       5    .033       0
#XS Ineff= 2 , 0
               0   50.07       5           49.47
Permanent Ineff=
       F       F
Bank Sta=0,5
XS Rating Curve= 0
Exp/Cntr=.3,.1

Type RM Length L Ch R = 1 ,900.00  ,35,35,35
BEGIN DESCRIPTION:
18
END DESCRIPTION:
#Sta/Elev= 13
    -8.7   53.25    -6.2   51.25    -3.7   49.25    -1.2   47.25       0   46.35
     1.3   45.45     4.3   45.35     4.7   45.05     5.3   45.05     5.5   46.35
     6.7   46.31       8   45.61      18   45.61
#Mann= 3 , 0 , 0
    -8.7    .033       0       0    .033       0     5.5    .033       0
#XS Ineff= 2 , 0
               0   46.35     5.5           46.35
Permanent Ineff=
       F       F
Bank Sta=0,5.5
XS Rating Curve= 0
Exp/Cntr=.3,.1

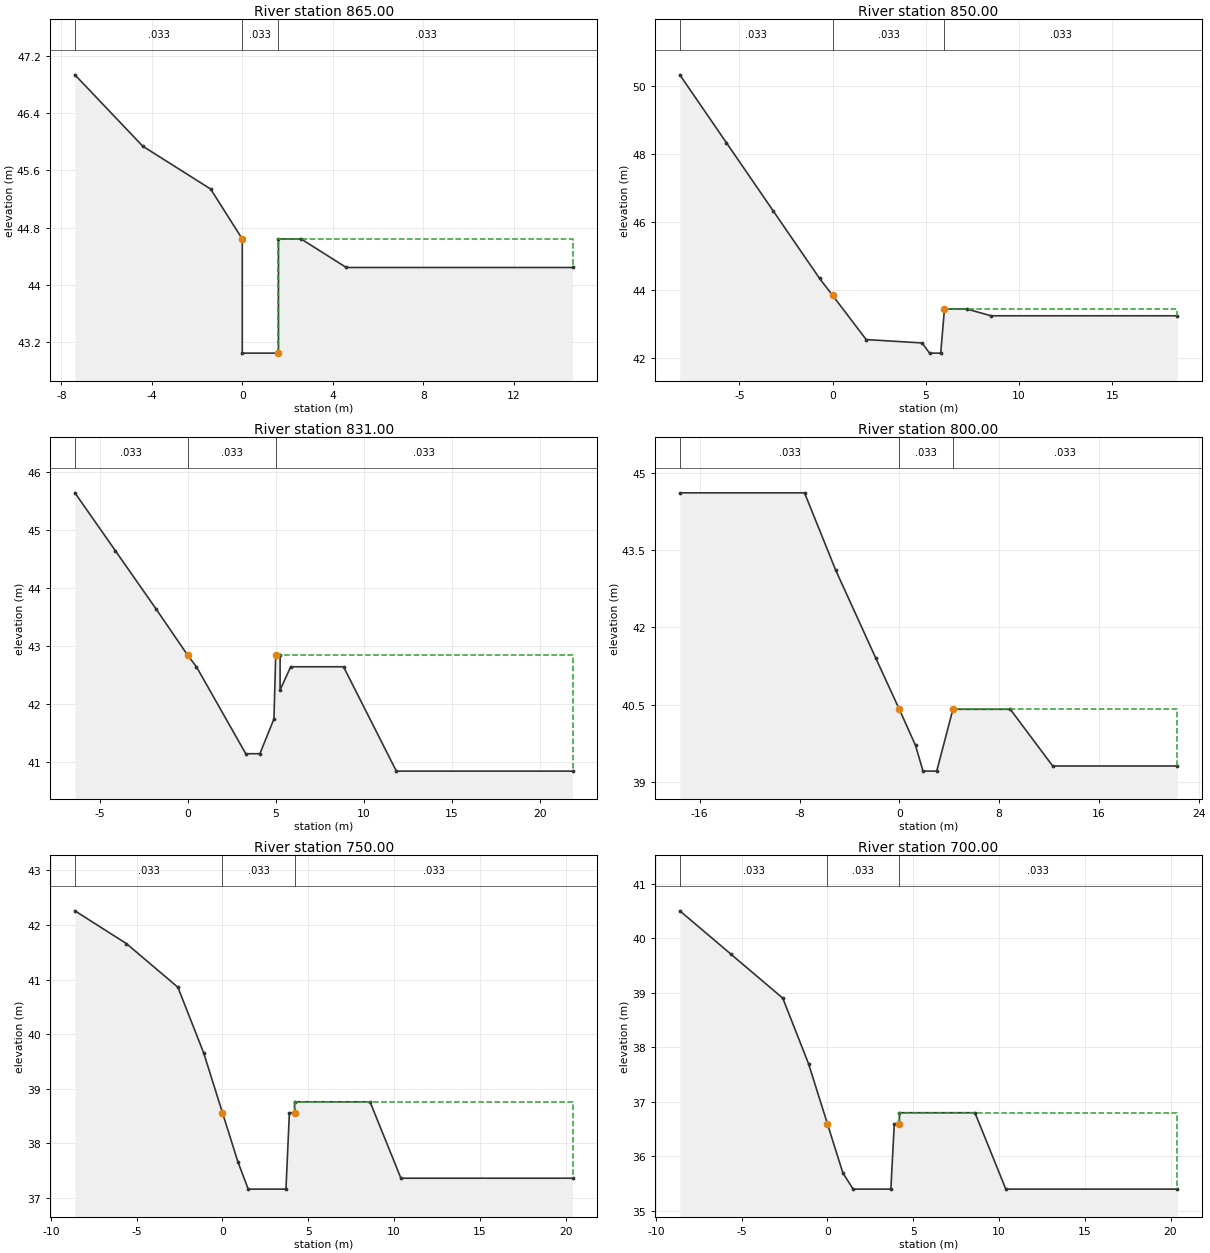
Type RM Length L Ch R = 1 ,865.00  ,15,15,15
BEGIN DESCRIPTION:
17.015
END DESCRIPTION:
#Sta/Elev= 10
    -7.4   46.94    -4.4   45.94    -1.4   45.34       0   44.64       0   43.04
     1.6   43.04     1.6   44.64     2.6   44.64     4.6   44.24    14.6   44.24
#Mann= 3 , 0 , 0
    -7.4    .033       0       0    .033       0     1.6    .033       0
#XS Ineff= 2 , 0
               0   44.64     1.6           44.64
Permanent Ineff=
       F       F
Bank Sta=0,1.6
XS Rating Curve= 0
Exp/Cntr=.3,.1

Type RM Length L Ch R = 1 ,850.00  ,19,19,19
BEGIN DESCRIPTION:
17
END DESCRIPTION:
#Sta/Elev= 13
    -8.2   50.34    -5.7   48.34    -3.2   46.34     -.7   44.34       0   43.84
     1.8   42.54     4.8   42.44     5.2   42.14     5.8   42.14       6   43.44
     7.2   43.44     8.5   43.24    18.5   43.24
#Mann= 3 , 0 , 0
    -8.2    .033       0       0    .033       0       6    .033       0
#XS Ineff= 2 , 0
               0   43.84       6           43.44
Permanent Ineff=
       F       F
Bank Sta=0,6
XS Rating Curve= 0
Exp/Cntr=.3,.1

Type RM Length L Ch R = 1 ,831.00  ,31,31,31
BEGIN DESCRIPTION:
16.031
END DESCRIPTION:
#Sta/Elev= 15
    -6.4   45.64    -4.1   44.64    -1.8   43.64       0   42.84      .5   42.64
     3.3   41.14     4.1   41.14     4.9   41.74       5   42.84    5.25   42.84
    5.25   42.24    5.85   42.64    8.85   42.64   11.85   40.84   21.85   40.84
#Mann= 3 , 0 , 0
    -6.4    .033       0       0    .033       0       5    .033       0
#XS Ineff= 2 , 0
               0   42.84       5           42.84
Permanent Ineff=
       F       F
Bank Sta=0,5
XS Rating Curve= 0
Exp/Cntr=.3,.1

Type RM Length L Ch R = 1 ,800.00  ,50,50,50
BEGIN DESCRIPTION:
16
END DESCRIPTION:
#Sta/Elev= 12
   -17.6   44.61    -7.6   44.61    -5.1   43.11    -1.9   41.41       0   40.41
     1.3   39.71     1.9   39.21       3   39.21     4.3   40.41     8.9   40.41
    12.3   39.31    22.3   39.31
#Mann= 3 , 0 , 0
   -17.6    .033       0       0    .033       0     4.3    .033       0
#XS Ineff= 2 , 0
               0   40.41     4.3           40.41
Permanent Ineff=
       F       F
Bank Sta=0,4.3
XS Rating Curve= 0
Exp/Cntr=.3,.1

Type RM Length L Ch R = 1 ,750.00  ,50,50,50
BEGIN DESCRIPTION:
15
END DESCRIPTION:
#Sta/Elev= 14
    -8.6   42.26    -5.6   41.66    -2.6   40.86    -1.1   39.66       0   38.56
      .9   37.66     1.5   37.16     3.7   37.16     3.9   38.56     4.2   38.56
     4.2   38.76     8.6   38.76    10.4   37.36    20.4   37.36
#Mann= 3 , 0 , 0
    -8.6    .033       0       0    .033       0     4.2    .033       0
#XS Ineff= 2 , 0
               0   38.56     4.2           38.76
Permanent Ineff=
       F       F
Bank Sta=0,4.2
XS Rating Curve= 0
Exp/Cntr=.3,.1

Type RM Length L Ch R = 1 ,700.00  ,4,4,4
BEGIN DESCRIPTION:
14
END DESCRIPTION:
#Sta/Elev= 14
    -8.6    40.5    -5.6    39.7    -2.6    38.9    -1.1    37.7       0    36.6
      .9    35.7     1.5    35.4     3.7    35.4     3.9    36.6     4.2    36.6
     4.2    36.8     8.6    36.8    10.4    35.4    20.4    35.4
#Mann= 3 , 0 , 0
    -8.6    .033       0       0    .033       0     4.2    .033       0
#XS Ineff= 2 , 0
               0    36.6     4.2            36.8
Permanent Ineff=
       F       F
Bank Sta=0,4.2
XS Rating Curve= 0
Exp/Cntr=.3,.1

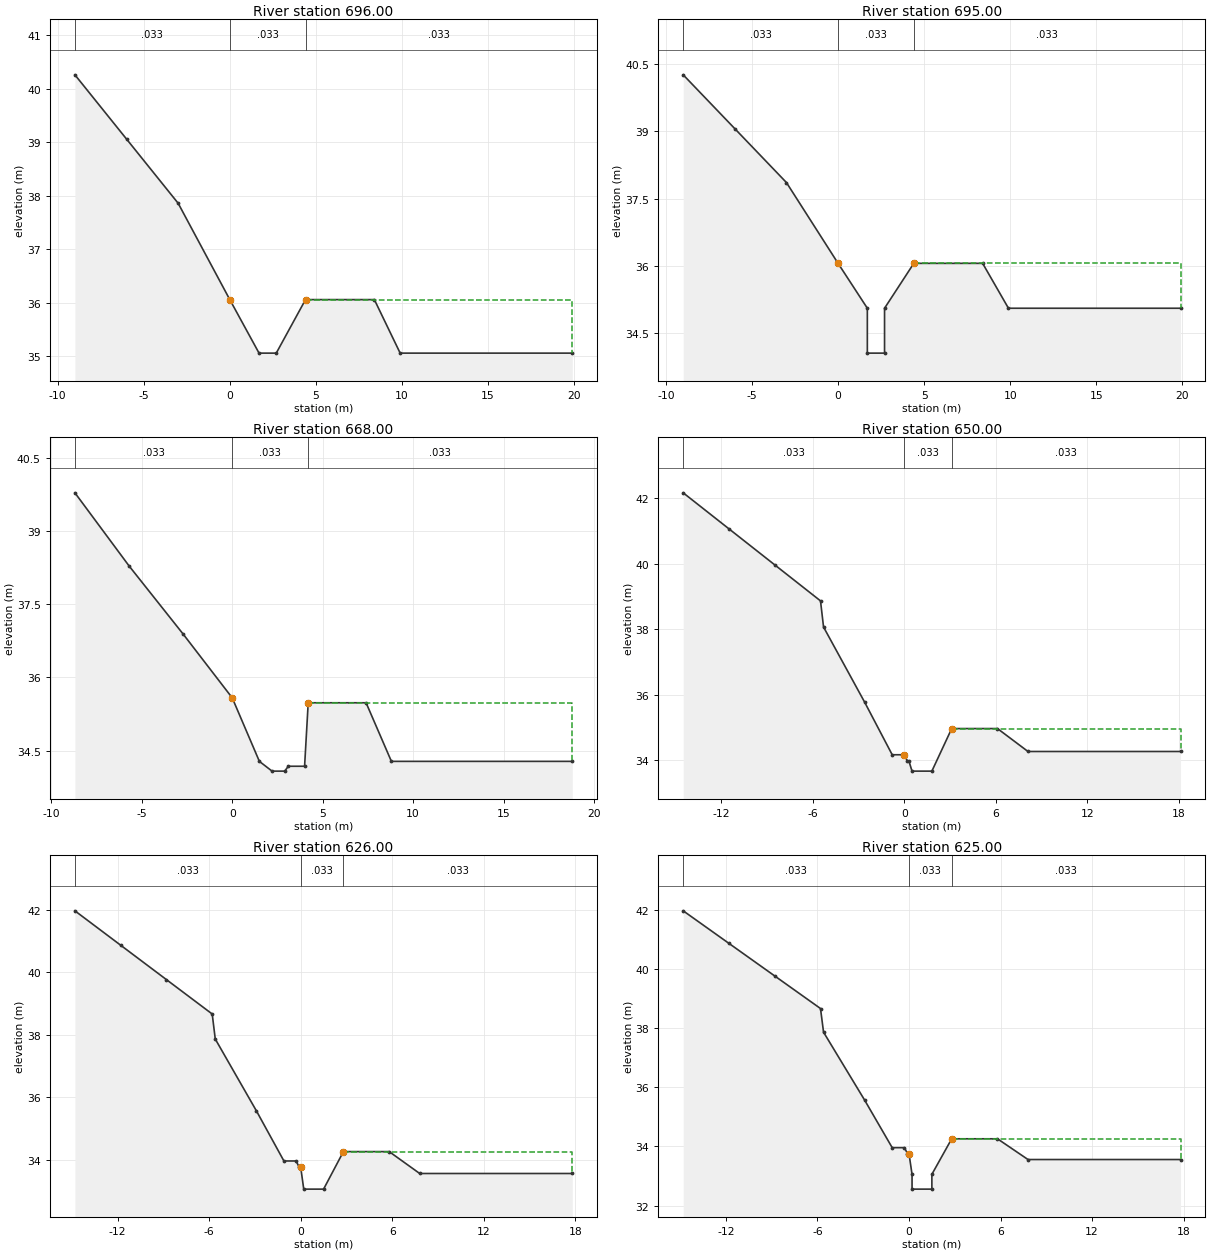
Type RM Length L Ch R = 1 ,696.00  ,1,1,1
BEGIN DESCRIPTION:
13.046
END DESCRIPTION:
#Sta/Elev= 10
      -9   40.26      -6   39.06      -3   37.86       0   36.06     1.7   35.06
     2.7   35.06     4.4   36.06     8.4   36.06     9.9   35.06    19.9   35.06
#Mann= 3 , 0 , 0
      -9    .033       0       0    .033       0     4.4    .033       0
#XS Ineff= 2 , 0
               0   36.06     4.4           36.06
Permanent Ineff=
       F       F
Bank Sta=0,4.4
XS Rating Curve= 0
Exp/Cntr=.3,.1

Type RM Length L Ch R = 1 ,695.00  ,27,27,27
BEGIN DESCRIPTION:
13.045
END DESCRIPTION:
#Sta/Elev= 12
      -9   40.26      -6   39.06      -3   37.86       0   36.06     1.7   35.06
     1.7   34.06     2.7   34.06     2.7   35.06     4.4   36.06     8.4   36.06
     9.9   35.06    19.9   35.06
#Mann= 3 , 0 , 0
      -9    .033       0       0    .033       0     4.4    .033       0
#XS Ineff= 2 , 0
               0   36.06     4.4           36.06
Permanent Ineff=
       F       F
Bank Sta=0,4.4
XS Rating Curve= 0
Exp/Cntr=.3,.1

Type RM Length L Ch R = 1 ,668.00  ,18,18,18
BEGIN DESCRIPTION:
13.018
END DESCRIPTION:
#Sta/Elev= 13
    -8.7   39.78    -5.7   38.28    -2.7   36.88       0   35.58     1.5   34.28
     2.2   34.08     2.9   34.08     3.1   34.18       4   34.18     4.2   35.48
     7.4   35.48     8.8   34.28    18.8   34.28
#Mann= 3 , 0 , 0
    -8.7    .033       0       0    .033       0     4.2    .033       0
#XS Ineff= 2 , 0
               0   35.58     4.2           35.48
Permanent Ineff=
       F       F
Bank Sta=0,4.2
XS Rating Curve= 0
Exp/Cntr=.3,.1

Type RM Length L Ch R = 1 ,650.00  ,24,24,24
BEGIN DESCRIPTION:
13
END DESCRIPTION:
#Sta/Elev= 16
   -14.5   42.16   -11.5   41.06    -8.5   39.96    -5.5   38.86    -5.3   38.06
    -2.6   35.76     -.8   34.16       0   34.16      .2   33.96      .3   33.96
      .5   33.66     1.8   33.66     3.1   34.96     6.1   34.96     8.1   34.26
    18.1   34.26
#Mann= 3 , 0 , 0
   -14.5    .033       0       0    .033       0     3.1    .033       0
#XS Ineff= 2 , 0
               0   34.16     3.1           34.96
Permanent Ineff=
       F       F
Bank Sta=0,3.1
XS Rating Curve= 0
Exp/Cntr=.3,.1

Type RM Length L Ch R = 1 ,626.00  ,1,1,1
BEGIN DESCRIPTION:
12.026
END DESCRIPTION:
#Sta/Elev= 16
   -14.8   41.96   -11.8   40.86    -8.8   39.76    -5.8   38.66    -5.6   37.86
    -2.9   35.56    -1.1   33.96     -.3   33.96     -.1   33.76       0   33.76
      .2   33.06     1.5   33.06     2.8   34.26     5.8   34.26     7.8   33.56
    17.8   33.56
#Mann= 3 , 0 , 0
   -14.8    .033       0       0    .033       0     2.8    .033       0
#XS Ineff= 2 , 0
               0   33.76     2.8           34.26
Permanent Ineff=
       F       F
Bank Sta=0,2.8
XS Rating Curve= 0
Exp/Cntr=.3,.1

Type RM Length L Ch R = 1 ,625.00  ,25,25,25
BEGIN DESCRIPTION:
12.025
END DESCRIPTION:
#Sta/Elev= 18
   -14.8   41.96   -11.8   40.86    -8.8   39.76    -5.8   38.66    -5.6   37.86
    -2.9   35.56    -1.1   33.96     -.3   33.96     -.1   33.76       0   33.76
      .2   33.06      .2   32.56     1.5   32.56     1.5   33.06     2.8   34.26
     5.8   34.26     7.8   33.56    17.8   33.56
#Mann= 3 , 0 , 0
   -14.8    .033       0       0    .033       0     2.8    .033       0
#XS Ineff= 2 , 0
               0   33.76     2.8           34.26
Permanent Ineff=
       F       F
Bank Sta=0,2.8
XS Rating Curve= 0
Exp/Cntr=.3,.1

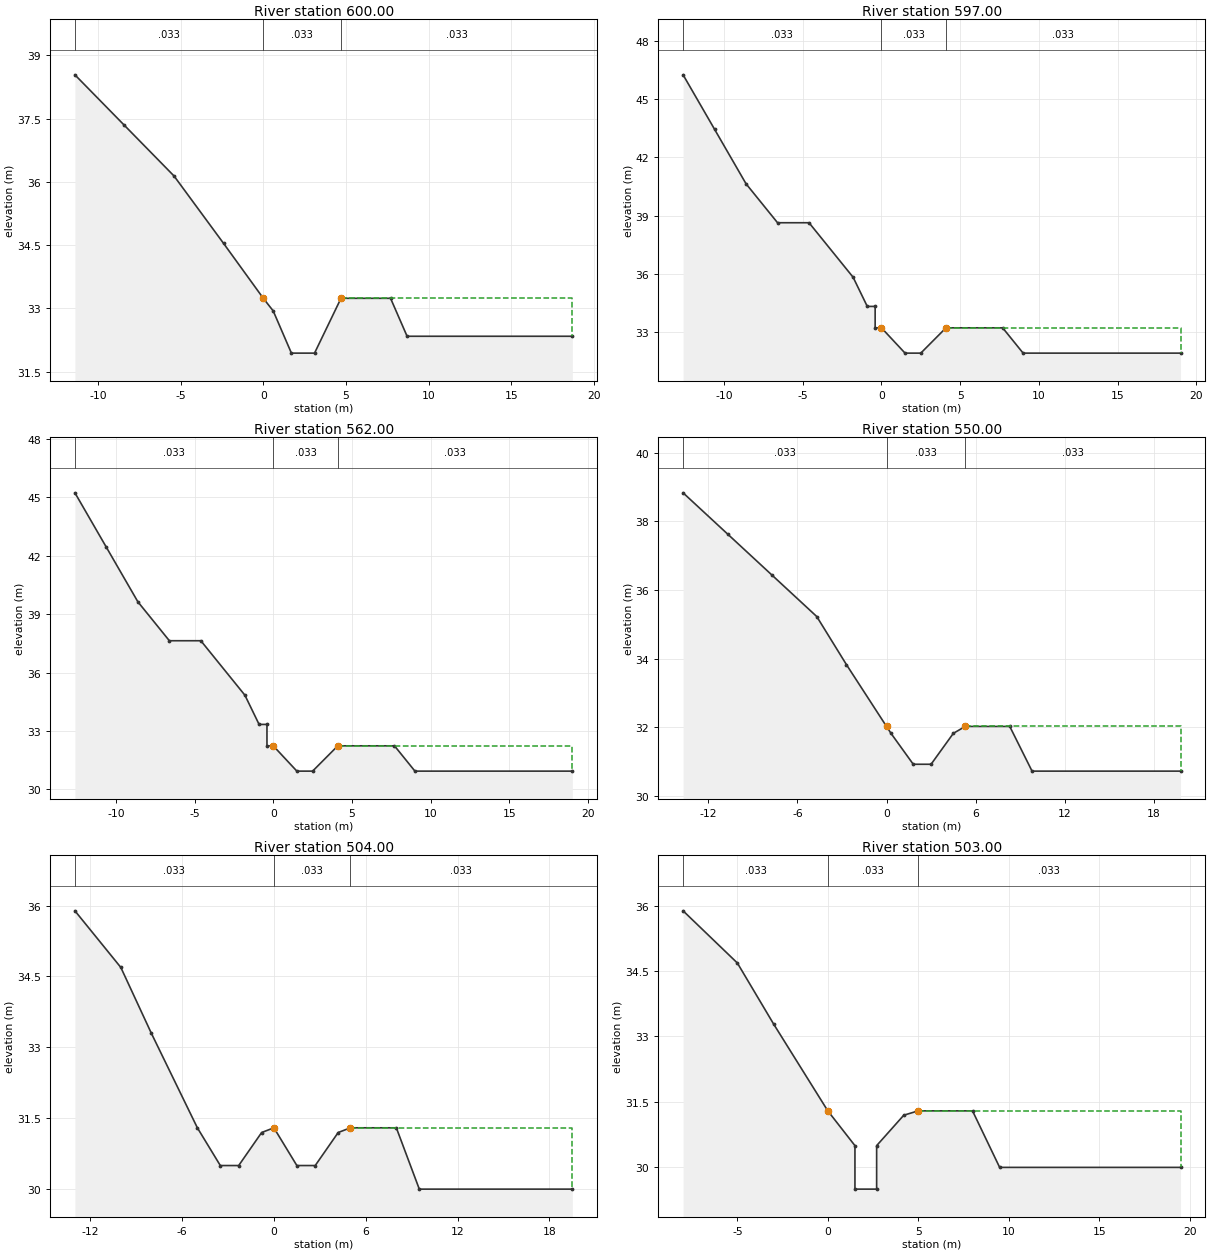
Type RM Length L Ch R = 1 ,600.00  ,3,3,3
BEGIN DESCRIPTION:
12
END DESCRIPTION:
#Sta/Elev= 12
   -11.4   38.54    -8.4   37.34    -5.4   36.14    -2.4   34.54       0   33.24
      .6   32.94     1.7   31.94     3.1   31.94     4.7   33.24     7.7   33.24
     8.7   32.34    18.7   32.34
#Mann= 3 , 0 , 0
   -11.4    .033       0       0    .033       0     4.7    .033       0
#XS Ineff= 2 , 0
               0   33.24     4.7           33.24
Permanent Ineff=
       F       F
Bank Sta=0,4.7
XS Rating Curve= 0
Exp/Cntr=.3,.1

Type RM Length L Ch R = 1 ,597.00  ,35,35,35
BEGIN DESCRIPTION:
11.047
END DESCRIPTION:
#Sta/Elev= 16
   -12.6   46.24   -10.6   43.44    -8.6   40.64    -6.6   38.64    -4.6   38.64
    -1.8   35.84     -.9   34.34     -.4   34.34     -.4   33.24       0   33.24
     1.5   31.94     2.5   31.94     4.1   33.24     7.7   33.24       9   31.94
      19   31.94
#Mann= 3 , 0 , 0
   -12.6    .033       0       0    .033       0     4.1    .033       0
#XS Ineff= 2 , 0
               0   33.24     4.1           33.24
Permanent Ineff=
       F       F
Bank Sta=0,4.1
XS Rating Curve= 0
Exp/Cntr=.3,.1

Type RM Length L Ch R = 1 ,562.00  ,12,12,12
BEGIN DESCRIPTION:
11.012
END DESCRIPTION:
#Sta/Elev= 16
   -12.6   45.24   -10.6   42.44    -8.6   39.64    -6.6   37.64    -4.6   37.64
    -1.8   34.84     -.9   33.34     -.4   33.34     -.4   32.24       0   32.24
     1.5   30.94     2.5   30.94     4.1   32.24     7.7   32.24       9   30.94
      19   30.94
#Mann= 3 , 0 , 0
   -12.6    .033       0       0    .033       0     4.1    .033       0
#XS Ineff= 2 , 0
               0   32.24     4.1           32.24
Permanent Ineff=
       F       F
Bank Sta=0,4.1
XS Rating Curve= 0
Exp/Cntr=.3,.1

Type RM Length L Ch R = 1 ,550.00  ,46,46,46
BEGIN DESCRIPTION:
11
END DESCRIPTION:
#Sta/Elev= 14
   -13.7   38.83   -10.7   37.63    -7.7   36.43    -4.7   35.23    -2.7   33.83
       0   32.03      .3   31.83     1.8   30.93       3   30.93     4.5   31.83
     5.3   32.03     8.3   32.03     9.8   30.73    19.8   30.73
#Mann= 3 , 0 , 0
   -13.7    .033       0       0    .033       0     5.3    .033       0
#XS Ineff= 2 , 0
               0   32.03     5.3           32.03
Permanent Ineff=
       F       F
Bank Sta=0,5.3
XS Rating Curve= 0
Exp/Cntr=.3,.1

Type RM Length L Ch R = 1 ,504.00  ,1,1,1
BEGIN DESCRIPTION:
10.004
END DESCRIPTION:
#Sta/Elev= 15
     -13   35.89     -10   34.69      -8   33.29      -5   31.29    -3.5   30.49
    -2.3   30.49     -.8   31.19       0   31.29     1.5   30.49     2.7   30.49
     4.2   31.19       5   31.29       8   31.29     9.5   29.99    19.5   29.99
#Mann= 3 , 0 , 0
     -13    .033       0       0    .033       0       5    .033       0
#XS Ineff= 2 , 0
               0   31.29       5           31.29
Permanent Ineff=
       F       F
Bank Sta=0,5
XS Rating Curve= 0
Exp/Cntr=.3,.1

Type RM Length L Ch R = 1 ,503.00  ,3,3,3
BEGIN DESCRIPTION:
10.003
END DESCRIPTION:
#Sta/Elev= 13
      -8   35.89      -5   34.69      -3   33.29       0   31.29     1.5   30.49
     1.5   29.49     2.7   29.49     2.7   30.49     4.2   31.19       5   31.29
       8   31.29     9.5   29.99    19.5   29.99
#Mann= 3 , 0 , 0
      -8    .033       0       0    .033       0       5    .033       0
#XS Ineff= 2 , 0
               0   31.29       5           31.29
Permanent Ineff=
       F       F
Bank Sta=0,5
XS Rating Curve= 0
Exp/Cntr=.3,.1

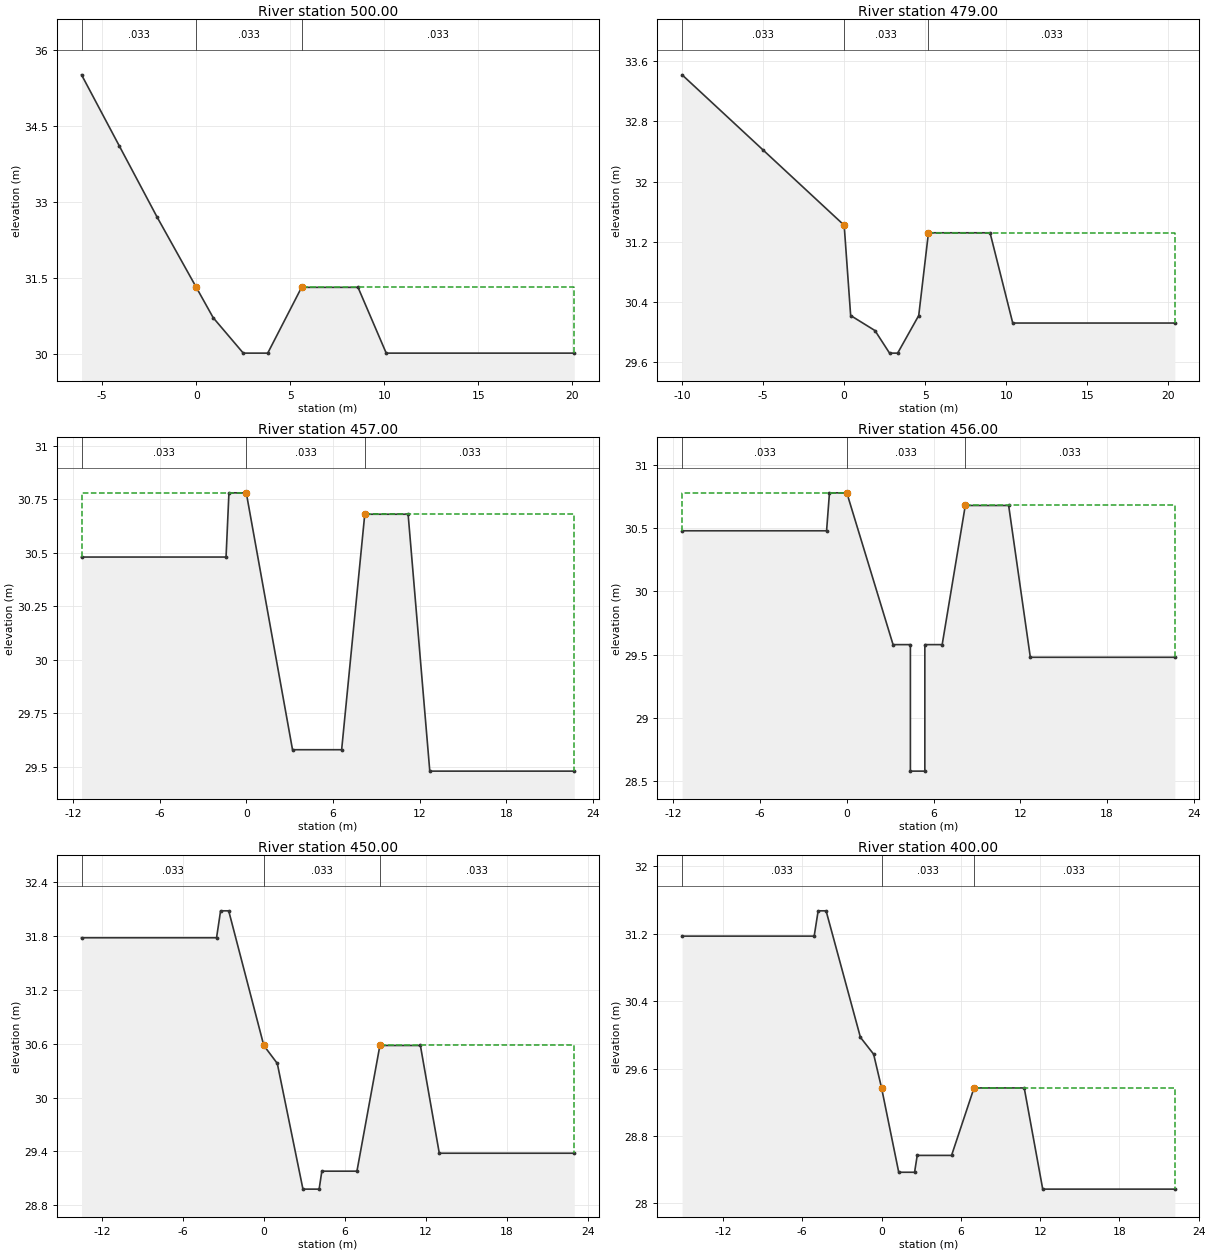
Type RM Length L Ch R = 1 ,500.00  ,21,21,21
BEGIN DESCRIPTION:
10
END DESCRIPTION:
#Sta/Elev= 11
    -6.1   35.51    -4.1   34.11    -2.1   32.71       0   31.31      .9   30.71
     2.5   30.01     3.8   30.01     5.6   31.31     8.6   31.31    10.1   30.01
    20.1   30.01
#Mann= 3 , 0 , 0
    -6.1    .033       0       0    .033       0     5.6    .033       0
#XS Ineff= 2 , 0
               0   31.31     5.6           31.31
Permanent Ineff=
       F       F
Bank Sta=0,5.6
XS Rating Curve= 0
Exp/Cntr=.3,.1

Type RM Length L Ch R = 1 ,479.00  ,22,22,22
BEGIN DESCRIPTION:
9.029
END DESCRIPTION:
#Sta/Elev= 12
     -10   33.42      -5   32.42       0   31.42      .4   30.22     1.9   30.02
     2.8   29.72     3.3   29.72     4.6   30.22     5.2   31.32       9   31.32
    10.4   30.12    20.4   30.12
#Mann= 3 , 0 , 0
     -10    .033       0       0    .033       0     5.2    .033       0
#XS Ineff= 2 , 0
               0   31.42     5.2           31.32
Permanent Ineff=
       F       F
Bank Sta=0,5.2
XS Rating Curve= 0
Exp/Cntr=.3,.1

Type RM Length L Ch R = 1 ,457.00  ,1,1,1
BEGIN DESCRIPTION:
9.007
END DESCRIPTION:
#Sta/Elev= 10
   -11.4   30.48    -1.4   30.48    -1.2   30.78       0   30.78     3.2   29.58
     6.6   29.58     8.2   30.68    11.2   30.68    12.7   29.48    22.7   29.48
#Mann= 3 , 0 , 0
   -11.4    .033       0       0    .033       0     8.2    .033       0
#XS Ineff= 2 , 0
               0   30.78     8.2           30.68
Permanent Ineff=
       F       F
Bank Sta=0,8.2
XS Rating Curve= 0
Exp/Cntr=.3,.1

Type RM Length L Ch R = 1 ,456.00  ,6,6,6
BEGIN DESCRIPTION:
9.006
END DESCRIPTION:
#Sta/Elev= 14
   -11.4   30.48    -1.4   30.48    -1.2   30.78       0   30.78     3.2   29.58
     4.4   29.58     4.4   28.58     5.4   28.58     5.4   29.58     6.6   29.58
     8.2   30.68    11.2   30.68    12.7   29.48    22.7   29.48
#Mann= 3 , 0 , 0
   -11.4    .033       0       0    .033       0     8.2    .033       0
#XS Ineff= 2 , 0
               0   30.78     8.2           30.68
Permanent Ineff=
       F       F
Bank Sta=0,8.2
XS Rating Curve= 0
Exp/Cntr=.3,.1

Type RM Length L Ch R = 1 ,450.00  ,50,50,50
BEGIN DESCRIPTION:
9
END DESCRIPTION:
#Sta/Elev= 14
   -13.5   31.78    -3.5   31.78    -3.2   32.08    -2.6   32.08       0   30.58
       1   30.38     2.9   28.98     4.1   28.98     4.3   29.18     6.9   29.18
     8.6   30.58    11.6   30.58      13   29.38      23   29.38
#Mann= 3 , 0 , 0
   -13.5    .033       0       0    .033       0     8.6    .033       0
#XS Ineff= 2 , 0
               0   30.58     8.6           30.58
Permanent Ineff=
       F       F
Bank Sta=0,8.6
XS Rating Curve= 0
Exp/Cntr=.3,.1

Type RM Length L Ch R = 1 ,400.00  ,50,50,50
BEGIN DESCRIPTION:
8
END DESCRIPTION:
#Sta/Elev= 15
   -15.1   31.17    -5.1   31.17    -4.8   31.47    -4.2   31.47    -1.6   29.97
     -.6   29.77       0   29.37     1.3   28.37     2.5   28.37     2.7   28.57
     5.3   28.57       7   29.37    10.8   29.37    12.2   28.17    22.2   28.17
#Mann= 3 , 0 , 0
   -15.1    .033       0       0    .033       0       7    .033       0
#XS Ineff= 2 , 0
               0   29.37       7           29.37
Permanent Ineff=
       F       F
Bank Sta=0,7
XS Rating Curve= 0
Exp/Cntr=.3,.1

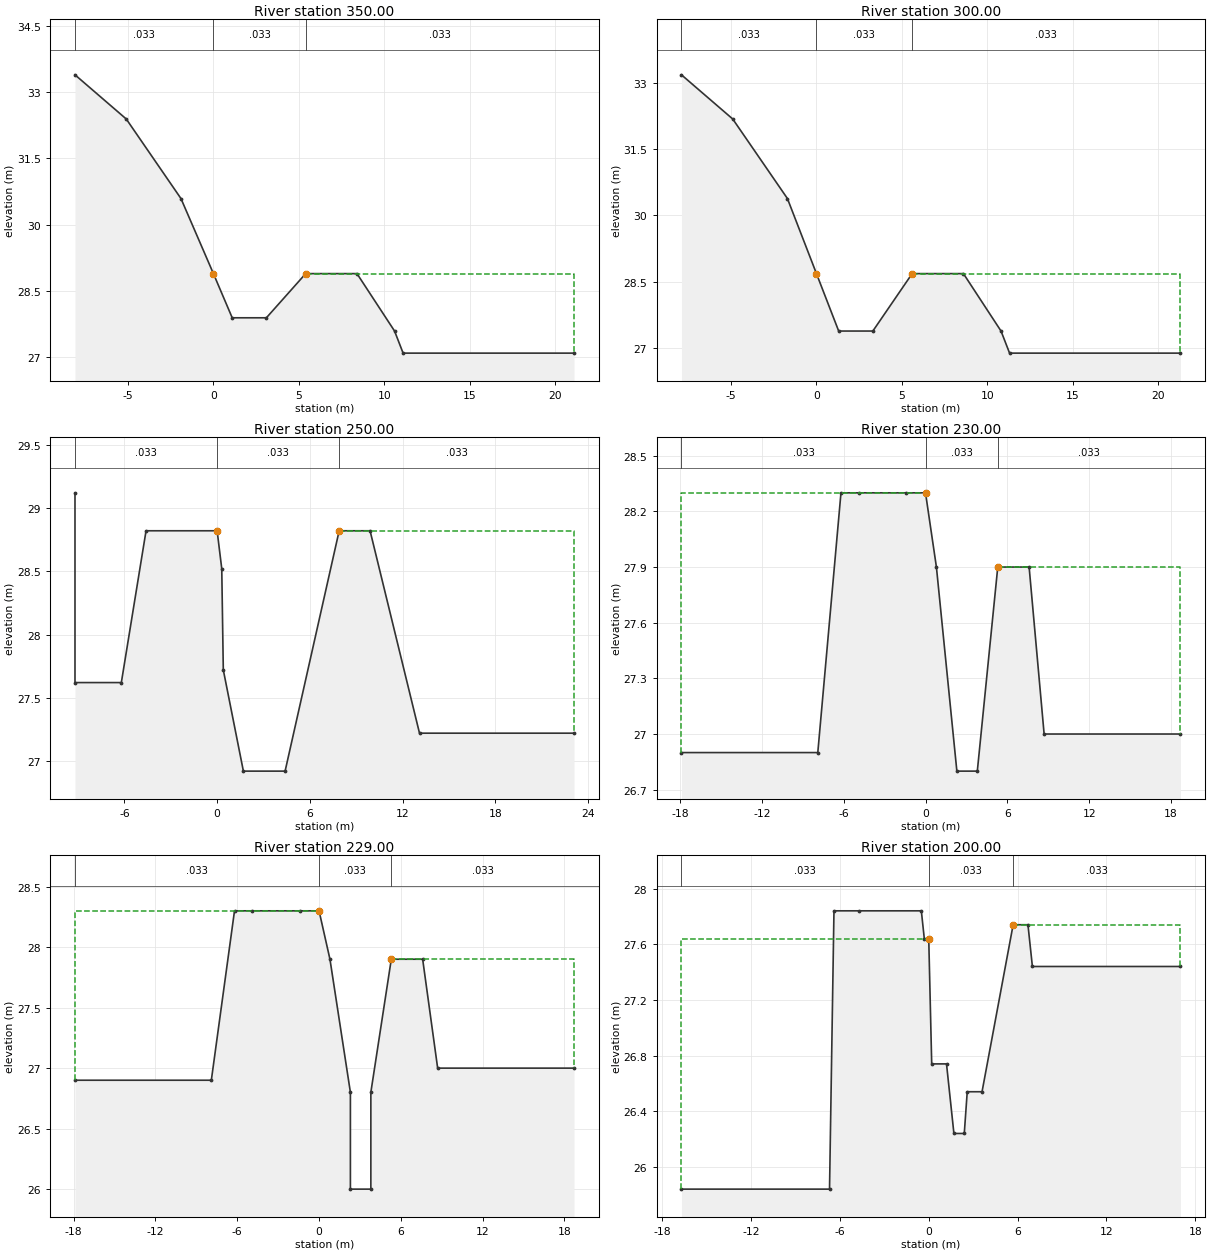
Type RM Length L Ch R = 1 ,350.00  ,50,50,50
BEGIN DESCRIPTION:
7
END DESCRIPTION:
#Sta/Elev= 11
    -8.1   33.39    -5.1   32.39    -1.9   30.59       0   28.89     1.1   27.89
     3.1   27.89     5.4   28.89     8.4   28.89    10.6   27.59    11.1   27.09
    21.1   27.09
#Mann= 3 , 0 , 0
    -8.1    .033       0       0    .033       0     5.4    .033       0
#XS Ineff= 2 , 0
               0   28.89     5.4           28.89
Permanent Ineff=
       F       F
Bank Sta=0,5.4
XS Rating Curve= 0
Exp/Cntr=.3,.1

Type RM Length L Ch R = 1 ,300.00  ,50,50,50
BEGIN DESCRIPTION:
6
END DESCRIPTION:
#Sta/Elev= 11
    -7.9   33.18    -4.9   32.18    -1.7   30.38       0   28.68     1.3   27.38
     3.3   27.38     5.6   28.68     8.6   28.68    10.8   27.38    11.3   26.88
    21.3   26.88
#Mann= 3 , 0 , 0
    -7.9    .033       0       0    .033       0     5.6    .033       0
#XS Ineff= 2 , 0
               0   28.68     5.6           28.68
Permanent Ineff=
       F       F
Bank Sta=0,5.6
XS Rating Curve= 0
Exp/Cntr=.3,.1

Type RM Length L Ch R = 1 ,250.00  ,20,20,20
BEGIN DESCRIPTION:
5
END DESCRIPTION:
#Sta/Elev= 13
    -9.2   29.12    -9.2   27.62    -6.2   27.62    -4.6   28.82       0   28.82
      .3   28.52      .4   27.72     1.7   26.92     4.4   26.92     7.9   28.82
     9.9   28.82    13.1   27.22    23.1   27.22
#Mann= 3 , 0 , 0
    -9.2    .033       0       0    .033       0     7.9    .033       0
#XS Ineff= 2 , 0
               0   28.82     7.9           28.82
Permanent Ineff=
       F       F
Bank Sta=0,7.9
XS Rating Curve= 0
Exp/Cntr=.3,.1

Type RM Length L Ch R = 1 ,230.00  ,1,1,1
BEGIN DESCRIPTION:
4.03
END DESCRIPTION:
#Sta/Elev= 13
   -17.9    26.9    -7.9    26.9    -6.2    28.3    -4.9    28.3    -1.4    28.3
       0    28.3      .8    27.9     2.3    26.8     3.8    26.8     5.3    27.9
     7.6    27.9     8.7      27    18.7      27
#Mann= 3 , 0 , 0
   -17.9    .033       0       0    .033       0     5.3    .033       0
#XS Ineff= 2 , 0
               0    28.3     5.3            27.9
Permanent Ineff=
       F       F
Bank Sta=0,5.3
XS Rating Curve= 0
Exp/Cntr=.3,.1

Type RM Length L Ch R = 1 ,229.00  ,29,29,29
BEGIN DESCRIPTION:
4.029
END DESCRIPTION:
#Sta/Elev= 15
   -17.9    26.9    -7.9    26.9    -6.2    28.3    -4.9    28.3    -1.4    28.3
       0    28.3      .8    27.9     2.3    26.8     2.3      26     3.8      26
     3.8    26.8     5.3    27.9     7.6    27.9     8.7      27    18.7      27
#Mann= 3 , 0 , 0
   -17.9    .033       0       0    .033       0     5.3    .033       0
#XS Ineff= 2 , 0
               0    28.3     5.3            27.9
Permanent Ineff=
       F       F
Bank Sta=0,5.3
XS Rating Curve= 0
Exp/Cntr=.3,.1

Type RM Length L Ch R = 1 ,200.00  ,41,41,41
BEGIN DESCRIPTION:
4
END DESCRIPTION:
#Sta/Elev= 17
   -16.7   25.84    -6.7   25.84    -6.4   27.84    -4.7   27.84     -.5   27.84
     -.3   27.64       0   27.64      .2   26.74     1.2   26.74     1.7   26.24
     2.4   26.24     2.6   26.54     3.6   26.54     5.7   27.74     6.7   27.74
       7   27.44      17   27.44
#Mann= 3 , 0 , 0
   -16.7    .033       0       0    .033       0     5.7    .033       0
#XS Ineff= 2 , 0
               0   27.64     5.7           27.74
Permanent Ineff=
       F       F
Bank Sta=0,5.7
XS Rating Curve= 0
Exp/Cntr=.3,.1