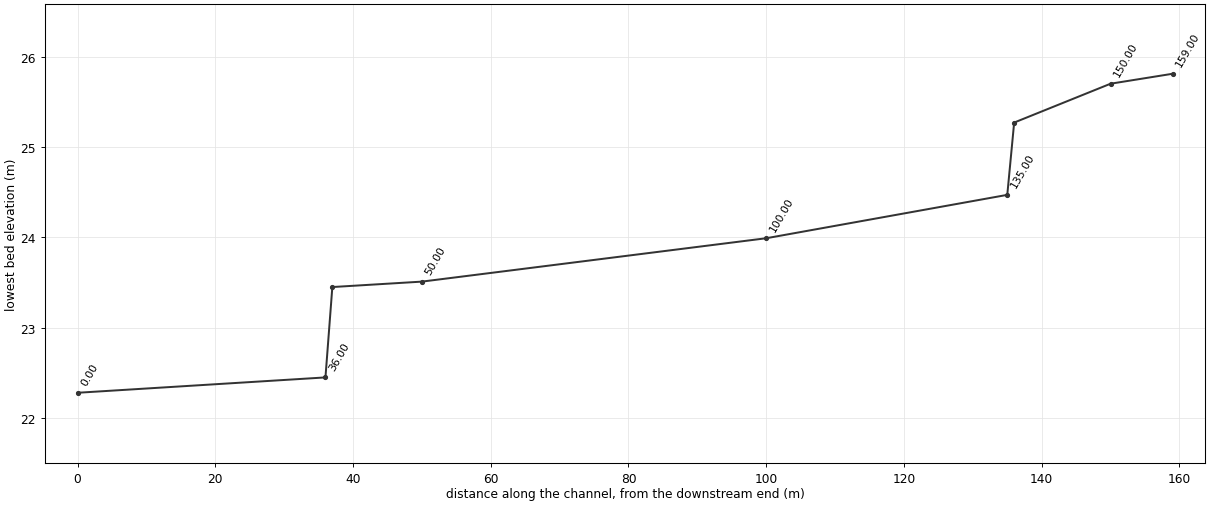
HEC-RAS study SIN.prj: SIN

--- SIN.g01 (geometry) --- (continued)

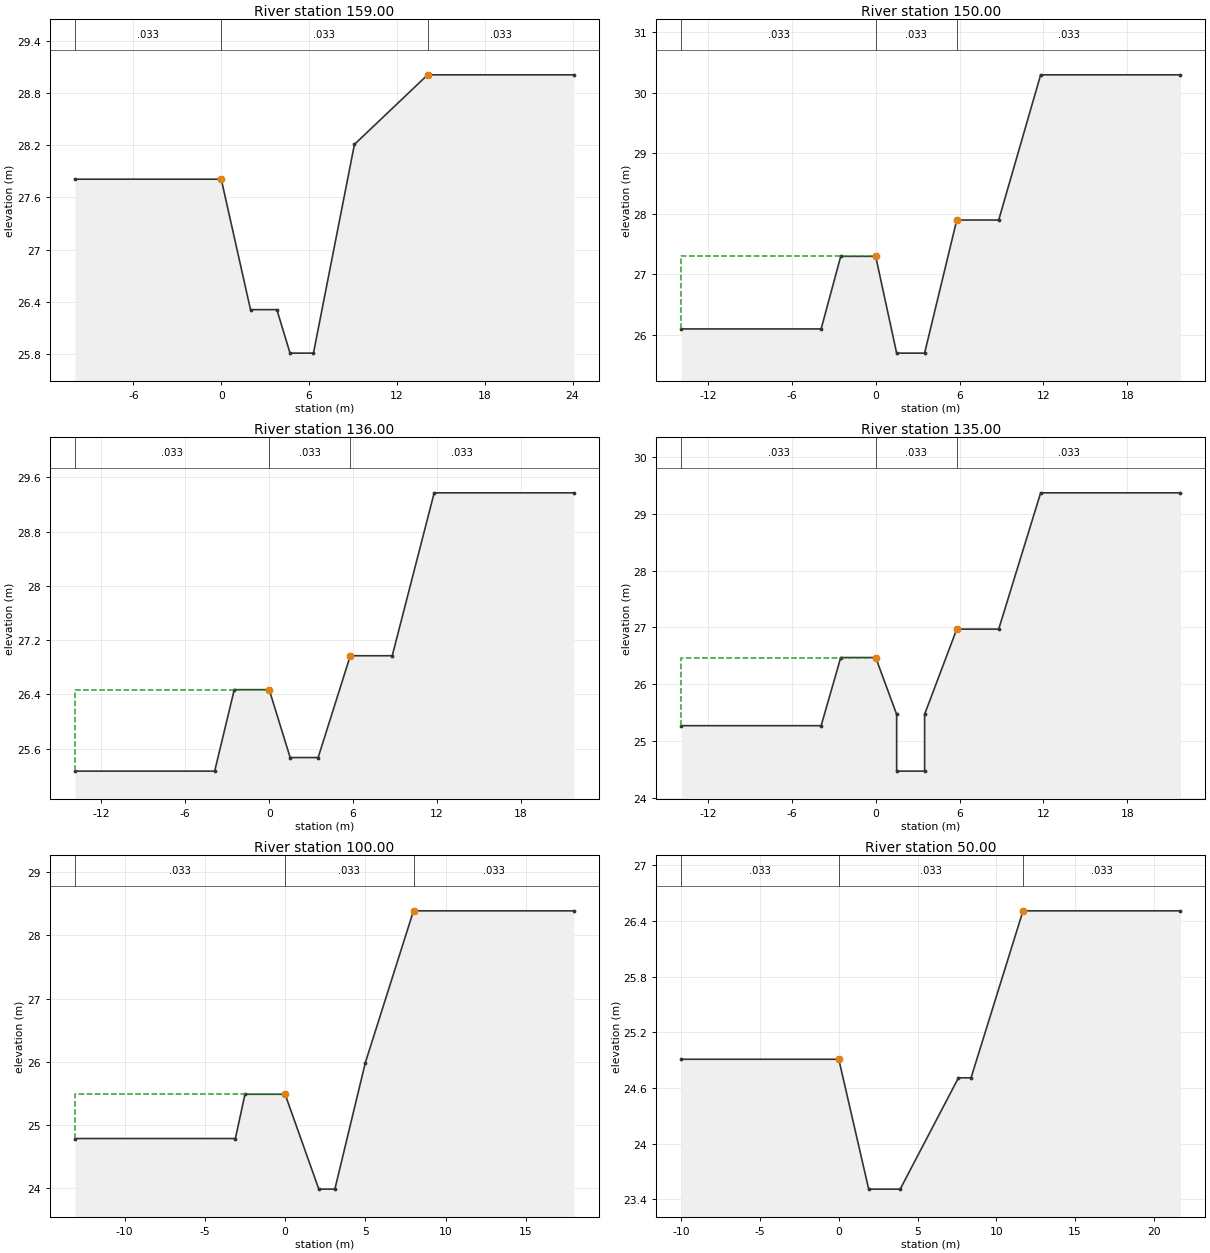
Type RM Length L Ch R = 1 ,159.00  ,9,9,9
BEGIN DESCRIPTION:
3.009
END DESCRIPTION:
#Sta/Elev= 9
     -10   27.81       0   27.81       2   26.31     3.8   26.31     4.7   25.81
     6.3   25.81     9.1   28.21    14.1   29.01    24.1   29.01
#Mann= 3 , 0 , 0
     -10    .033       0       0    .033       0    14.1    .033       0
#XS Ineff= 2 , 0
               0   27.81    14.1           29.01
Permanent Ineff=
       F       F
Bank Sta=0,14.1
XS Rating Curve= 0
Exp/Cntr=.3,.1

Type RM Length L Ch R = 1 ,150.00  ,14,14,14
BEGIN DESCRIPTION:
3
END DESCRIPTION:
#Sta/Elev= 10
   -13.9    26.1    -3.9    26.1    -2.5    27.3       0    27.3     1.5    25.7
     3.5    25.7     5.8    27.9     8.8    27.9    11.8    30.3    21.8    30.3
#Mann= 3 , 0 , 0
   -13.9    .033       0       0    .033       0     5.8    .033       0
#XS Ineff= 2 , 0
               0    27.3     5.8            27.9
Permanent Ineff=
       F       F
Bank Sta=0,5.8
XS Rating Curve= 0
Exp/Cntr=.3,.1

Type RM Length L Ch R = 1 ,136.00  ,1,1,1
BEGIN DESCRIPTION:
2.036
END DESCRIPTION:
#Sta/Elev= 10
   -13.9   25.27    -3.9   25.27    -2.5   26.47       0   26.47     1.5   25.47
     3.5   25.47     5.8   26.97     8.8   26.97    11.8   29.37    21.8   29.37
#Mann= 3 , 0 , 0
   -13.9    .033       0       0    .033       0     5.8    .033       0
#XS Ineff= 2 , 0
               0   26.47     5.8           26.97
Permanent Ineff=
       F       F
Bank Sta=0,5.8
XS Rating Curve= 0
Exp/Cntr=.3,.1

Type RM Length L Ch R = 1 ,135.00  ,35,35,35
BEGIN DESCRIPTION:
2.035
END DESCRIPTION:
#Sta/Elev= 12
   -13.9   25.27    -3.9   25.27    -2.5   26.47       0   26.47     1.5   25.47
     1.5   24.47     3.5   24.47     3.5   25.47     5.8   26.97     8.8   26.97
    11.8   29.37    21.8   29.37
#Mann= 3 , 0 , 0
   -13.9    .033       0       0    .033       0     5.8    .033       0
#XS Ineff= 2 , 0
               0   26.47     5.8           26.97
Permanent Ineff=
       F       F
Bank Sta=0,5.8
XS Rating Curve= 0
Exp/Cntr=.3,.1

Type RM Length L Ch R = 1 ,100.00  ,50,50,50
BEGIN DESCRIPTION:
2
END DESCRIPTION:
#Sta/Elev= 9
   -13.1   24.79    -3.1   24.79    -2.5   25.49       0   25.49     2.1   23.99
     3.1   23.99       5   25.99       8   28.39      18   28.39
#Mann= 3 , 0 , 0
   -13.1    .033       0       0    .033       0       8    .033       0
#XS Ineff= 2 , 0
               0   25.49       8           28.39
Permanent Ineff=
       F       F
Bank Sta=0,8
XS Rating Curve= 0
Exp/Cntr=.3,.1

Type RM Length L Ch R = 1 ,50.00   ,13,13,13
BEGIN DESCRIPTION:
1
END DESCRIPTION:
#Sta/Elev= 8
     -10   24.91       0   24.91     1.9   23.51     3.9   23.51     7.6   24.71
     8.4   24.71    11.7   26.51    21.7   26.51
#Mann= 3 , 0 , 0
     -10    .033       0       0    .033       0    11.7    .033       0
#XS Ineff= 2 , 0
               0   24.91    11.7           26.51
Permanent Ineff=
       F       F
Bank Sta=0,11.7
XS Rating Curve= 0
Exp/Cntr=.3,.1

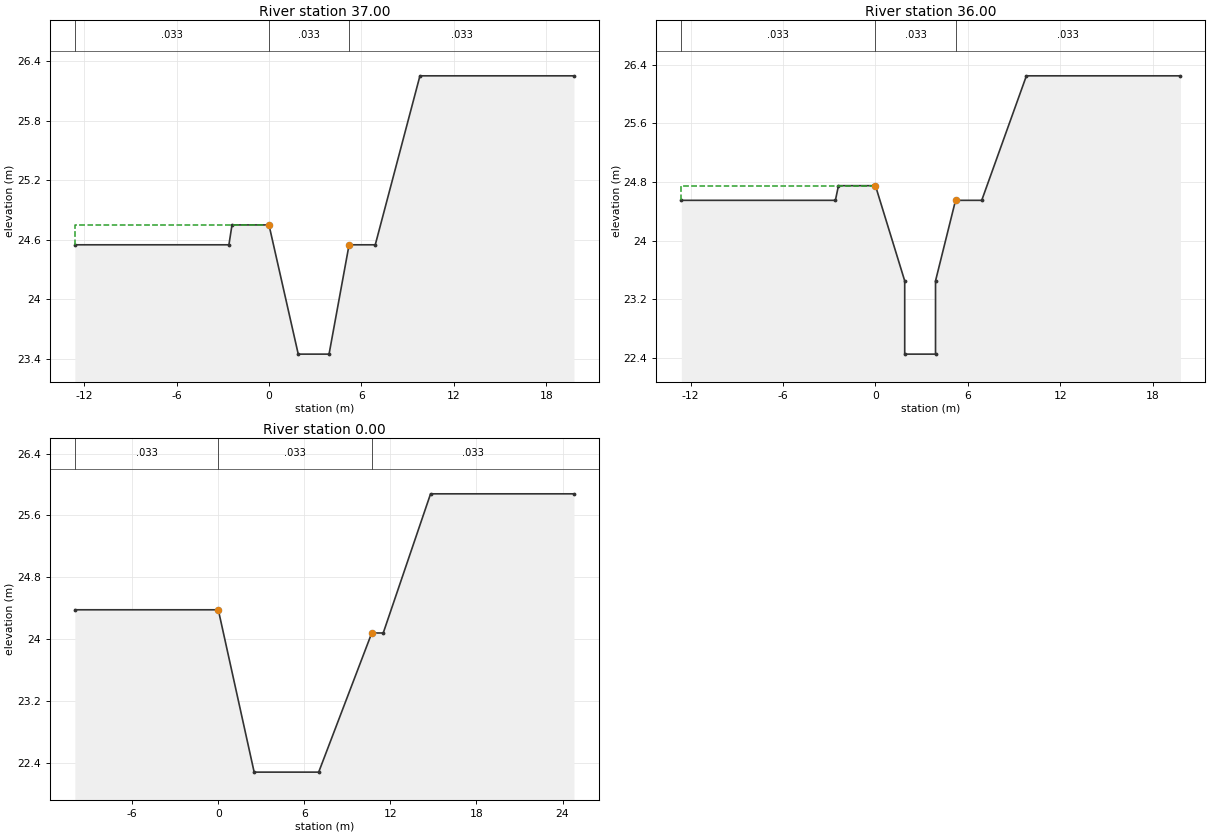
Type RM Length L Ch R = 1 ,37.00   ,1,1,1
BEGIN DESCRIPTION:
0.037
END DESCRIPTION:
#Sta/Elev= 10
   -12.6   24.55    -2.6   24.55    -2.4   24.75       0   24.75     1.9   23.45
     3.9   23.45     5.2   24.55     6.9   24.55     9.8   26.25    19.8   26.25
#Mann= 3 , 0 , 0
   -12.6    .033       0       0    .033       0     5.2    .033       0
#XS Ineff= 2 , 0
               0   24.75     5.2           24.55
Permanent Ineff=
       F       F
Bank Sta=0,5.2
XS Rating Curve= 0
Exp/Cntr=.3,.1

Type RM Length L Ch R = 1 ,36.00   ,36,36,36
BEGIN DESCRIPTION:
0.036
END DESCRIPTION:
#Sta/Elev= 12
   -12.6   24.55    -2.6   24.55    -2.4   24.75       0   24.75     1.9   23.45
     1.9   22.45     3.9   22.45     3.9   23.45     5.2   24.55     6.9   24.55
     9.8   26.25    19.8   26.25
#Mann= 3 , 0 , 0
   -12.6    .033       0       0    .033       0     5.2    .033       0
#XS Ineff= 2 , 0
               0   24.75     5.2           24.55
Permanent Ineff=
       F       F
Bank Sta=0,5.2
XS Rating Curve= 0
Exp/Cntr=.3,.1

Type RM Length L Ch R = 1 ,0.00    ,0,0,0
BEGIN DESCRIPTION:
0
END DESCRIPTION:
#Sta/Elev= 8
     -10   24.38       0   24.38     2.5   22.28       7   22.28    10.7   24.08
    11.5   24.08    14.8   25.88    24.8   25.88
#Mann= 3 , 0 , 0
     -10    .033       0       0    .033       0    10.7    .033       0
#XS Ineff= 2 , 0
               0   24.38    10.7           24.08
Permanent Ineff=
       F       F
Bank Sta=0,10.7
XS Rating Curve= 0
Exp/Cntr=.3,.1

Chan Stop Cuts=-1