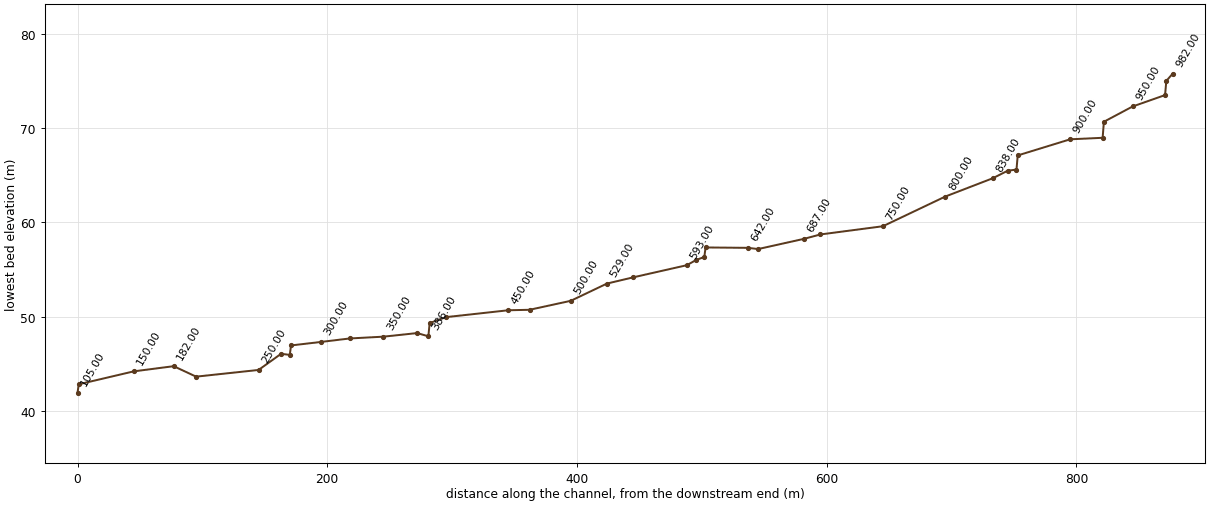
--- SINJ.prj (project) ---

Proj Title=SINJ
Current Plan=p01
Default Exp/Contr=.3,.1
SI Units
Geom File=g01
Flow File=f01
Plan File=p01
Y Axis Title=Elevation
X Axis Title(PF)=Main Channel Distance
X Axis Title(XS)=Station
BEGIN DESCRIPTION:
           BACK WATER COMPUTATION
      APPLICATION OF HEC-2 BY Samju Construction Engineering
      SINJEOGOL-STREEM : 30 YR
END DESCRIPTION:
DSS Export Rating Curves= 0
DSS Export Rating Curve Sorted= 0
DSS Export Volume Flow Curves= 0
DXF OffsetX= 0
DXF OffsetY= 0
DXF ScaleX= 1
DXF ScaleY= 10

--- SINJ.p01 (plan) ---

Plan Title=Imported Plan 01
Version=Version 3.0.1  Mar 2001
Short Identifier=Imported Pla
Geom File=g01
Flow File=f01
Subcritical Flow
K Sum by GR= 0
Std Step Tol= 0.003
Critical Tol= 0.003
Num of Std Step Trials= 20
Max Error Tol= 0.1
Flow Tol Ratio= 0.001
Split Flow NTrial= 30
Split Flow Tol= 0.02
Split Flow Ratio= 0.02
Log Output Level= 0
Friction Slope Method= 1
Unsteady Friction Slope Method= 2
Parabolic Critical Depth
Global Vel Dist= 0 , 0 , 0
Global Log Level= 0
CheckData=True
Encroach Param=-1 ,0,0, 0
Computation Interval=1HOUR
Output Interval=1HOUR
Run HTab= 0
Run UNet= 0
Run PostProcess= 0
UNET Theta= 1
UNET ZTol= 0.02
UNET ZSATol= 0.1
UNET MxIter= 20
UNET MaxInSteps= 20
UNET DtIC= 0
UNET DtMin= 0
UNET MaxCRTS= 20
UNET WFStab= 2
UNET SFStab= 1
UNET WFX= 1
UNET SFX= 1
UNET Convert EG Bridges=-1
UNET Use Existing IB Tables=-1
Instantaneous Interval=1HOUR
Write IC File= 0
Write Velocity= 0
Write Detailed= 0

--- SINJ.f01 (steady flow) ---

Flow Title=Imported Flow 01
Version=Version 3.0.1  Mar 2001
Number of Profiles= 5
Profile Names=10YR,20YR,30YR,50YR,80YR
River Rch & RM=RIVER-1,Reach-1         ,982.00
    18.2   20.05   21.14    22.5   23.75
Boundary for River Rch & Prof#=RIVER-1,Reach-1         , 1
Up Type= 0
Dn Type= 3
Dn Slope=.022
Boundary for River Rch & Prof#=RIVER-1,Reach-1         , 2
Up Type= 0
Dn Type= 3
Dn Slope=.022
Boundary for River Rch & Prof#=RIVER-1,Reach-1         , 3
Up Type= 0
Dn Type= 3
Dn Slope=.022
Boundary for River Rch & Prof#=RIVER-1,Reach-1         , 4
Up Type= 0
Dn Type= 3
Dn Slope=.022
Boundary for River Rch & Prof#=RIVER-1,Reach-1         , 5
Up Type= 0
Dn Type= 3
Dn Slope=.022
DSS Import GetInterval= 0
DSS Import GetPeak= 0
DSS Import FillOption= 0

--- SINJ.g01 (geometry) ---

Geom Title=Imported Geom 01
Version=Version 3.0.1  Mar 2001

River Reach=RIVER-1         ,Reach-1
Reach XY= 2
              .5             .95              .5             .05

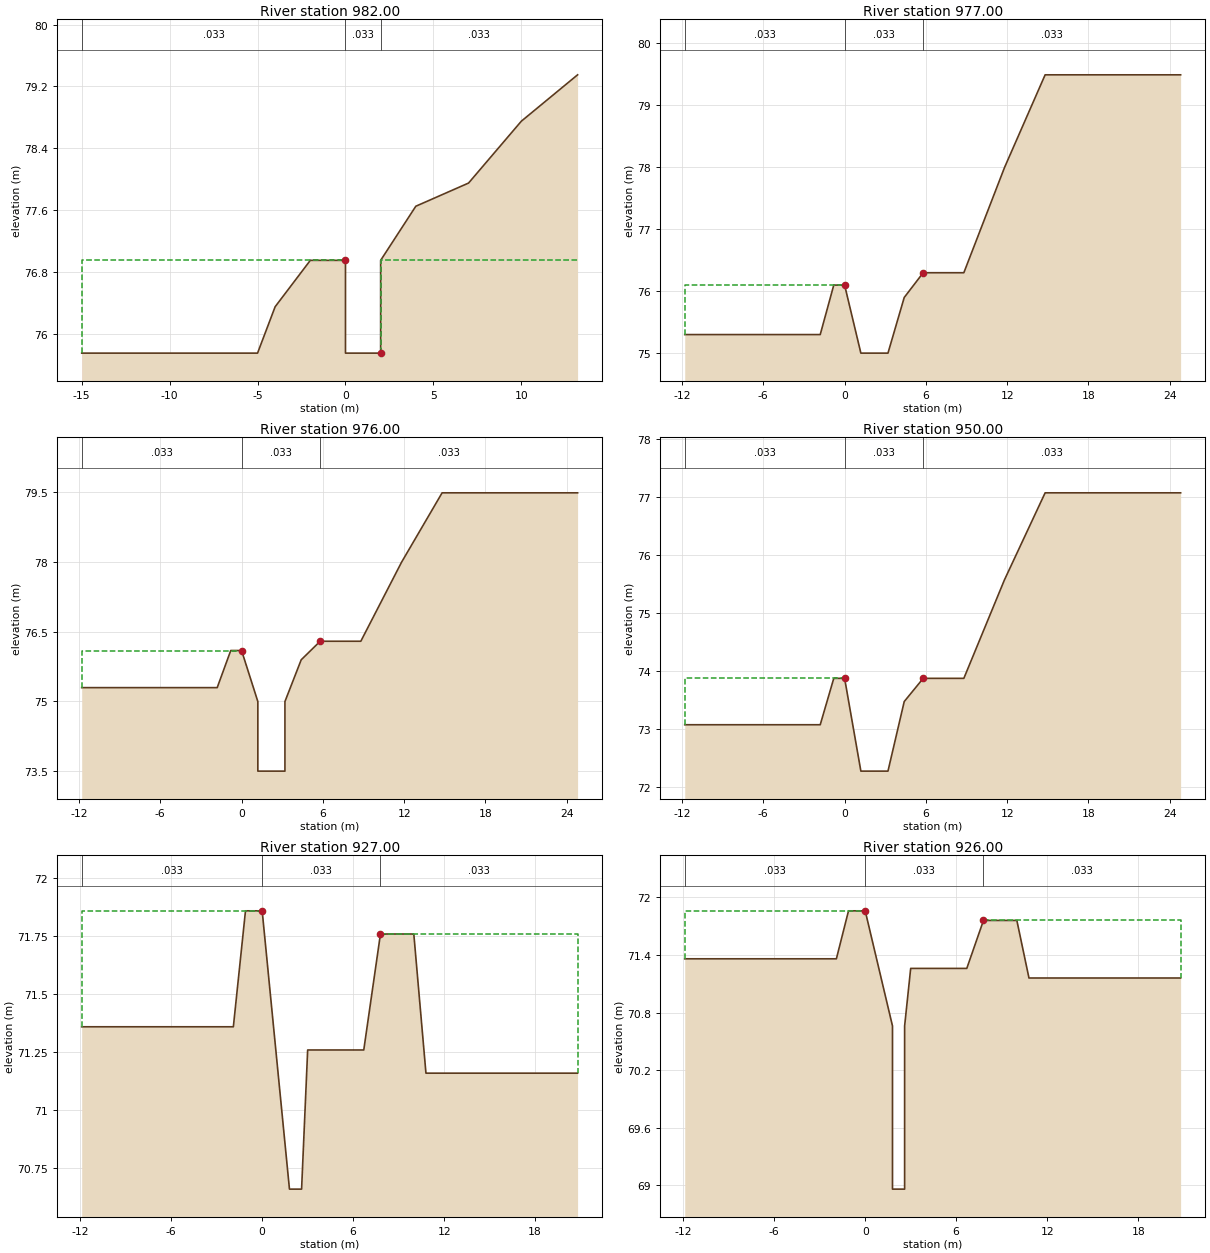
Type RM Length L Ch R = 1 ,982.00  ,5,5,5
BEGIN DESCRIPTION:
19.032
END DESCRIPTION:
#Sta/Elev= 12
     -15   75.75      -5   75.75      -4   76.35      -2   76.95       0   76.95
       0   75.75       2   75.75       2   76.95       4   77.65       7   77.95
      10   78.75    13.2   79.35
#Mann= 3 , 0 , 0
     -15    .033       0       0    .033       0       2    .033       0
#XS Ineff= 2 , 0
               0   76.95       2           76.95
Permanent Ineff=
       F       F
Bank Sta=0,2
XS Rating Curve= 0
Exp/Cntr=.3,.1

Type RM Length L Ch R = 1 ,977.00  ,1,1,1
BEGIN DESCRIPTION:
19.027
END DESCRIPTION:
#Sta/Elev= 12
   -11.8   75.29    -1.8   75.29     -.8   76.09       0   76.09     1.2   74.99
     3.2   74.99     4.4   75.89     5.8   76.29     8.8   76.29    11.8   77.99
    14.8   79.49    24.8   79.49
#Mann= 3 , 0 , 0
   -11.8    .033       0       0    .033       0     5.8    .033       0
#XS Ineff= 2 , 0
               0   76.09     5.8           76.29
Permanent Ineff=
       F       F
Bank Sta=0,5.8
XS Rating Curve= 0
Exp/Cntr=.3,.1

Type RM Length L Ch R = 1 ,976.00  ,26,26,26
BEGIN DESCRIPTION:
19.026
END DESCRIPTION:
#Sta/Elev= 14
   -11.8   75.29    -1.8   75.29     -.8   76.09       0   76.09     1.2   74.99
     1.2   73.49     3.2   73.49     3.2   74.99     4.4   75.89     5.8   76.29
     8.8   76.29    11.8   77.99    14.8   79.49    24.8   79.49
#Mann= 3 , 0 , 0
   -11.8    .033       0       0    .033       0     5.8    .033       0
#XS Ineff= 2 , 0
               0   76.09     5.8           76.29
Permanent Ineff=
       F       F
Bank Sta=0,5.8
XS Rating Curve= 0
Exp/Cntr=.3,.1

Type RM Length L Ch R = 1 ,950.00  ,23,23,23
BEGIN DESCRIPTION:
19
END DESCRIPTION:
#Sta/Elev= 12
   -11.8   73.08    -1.8   73.08     -.8   73.88       0   73.88     1.2   72.28
     3.2   72.28     4.4   73.48     5.8   73.88     8.8   73.88    11.8   75.58
    14.8   77.08    24.8   77.08
#Mann= 3 , 0 , 0
   -11.8    .033       0       0    .033       0     5.8    .033       0
#XS Ineff= 2 , 0
               0   73.88     5.8           73.88
Permanent Ineff=
       F       F
Bank Sta=0,5.8
XS Rating Curve= 0
Exp/Cntr=.3,.1

Type RM Length L Ch R = 1 ,927.00  ,1,1,1
BEGIN DESCRIPTION:
18.027
END DESCRIPTION:
#Sta/Elev= 12
   -11.9   71.36    -1.9   71.36    -1.1   71.86       0   71.86     1.8   70.66
     2.6   70.66       3   71.26     6.7   71.26     7.8   71.76      10   71.76
    10.8   71.16    20.8   71.16
#Mann= 3 , 0 , 0
   -11.9    .033       0       0    .033       0     7.8    .033       0
#XS Ineff= 2 , 0
               0   71.86     7.8           71.76
Permanent Ineff=
       F       F
Bank Sta=0,7.8
XS Rating Curve= 0
Exp/Cntr=.3,.1

Type RM Length L Ch R = 1 ,926.00  ,26,26,26
BEGIN DESCRIPTION:
18.026
END DESCRIPTION:
#Sta/Elev= 14
   -11.9   71.36    -1.9   71.36    -1.1   71.86       0   71.86     1.8   70.66
     1.8   68.96     2.6   68.96     2.6   70.66       3   71.26     6.7   71.26
     7.8   71.76      10   71.76    10.8   71.16    20.8   71.16
#Mann= 3 , 0 , 0
   -11.9    .033       0       0    .033       0     7.8    .033       0
#XS Ineff= 2 , 0
               0   71.86     7.8           71.76
Permanent Ineff=
       F       F
Bank Sta=0,7.8
XS Rating Curve= 0
Exp/Cntr=.3,.1

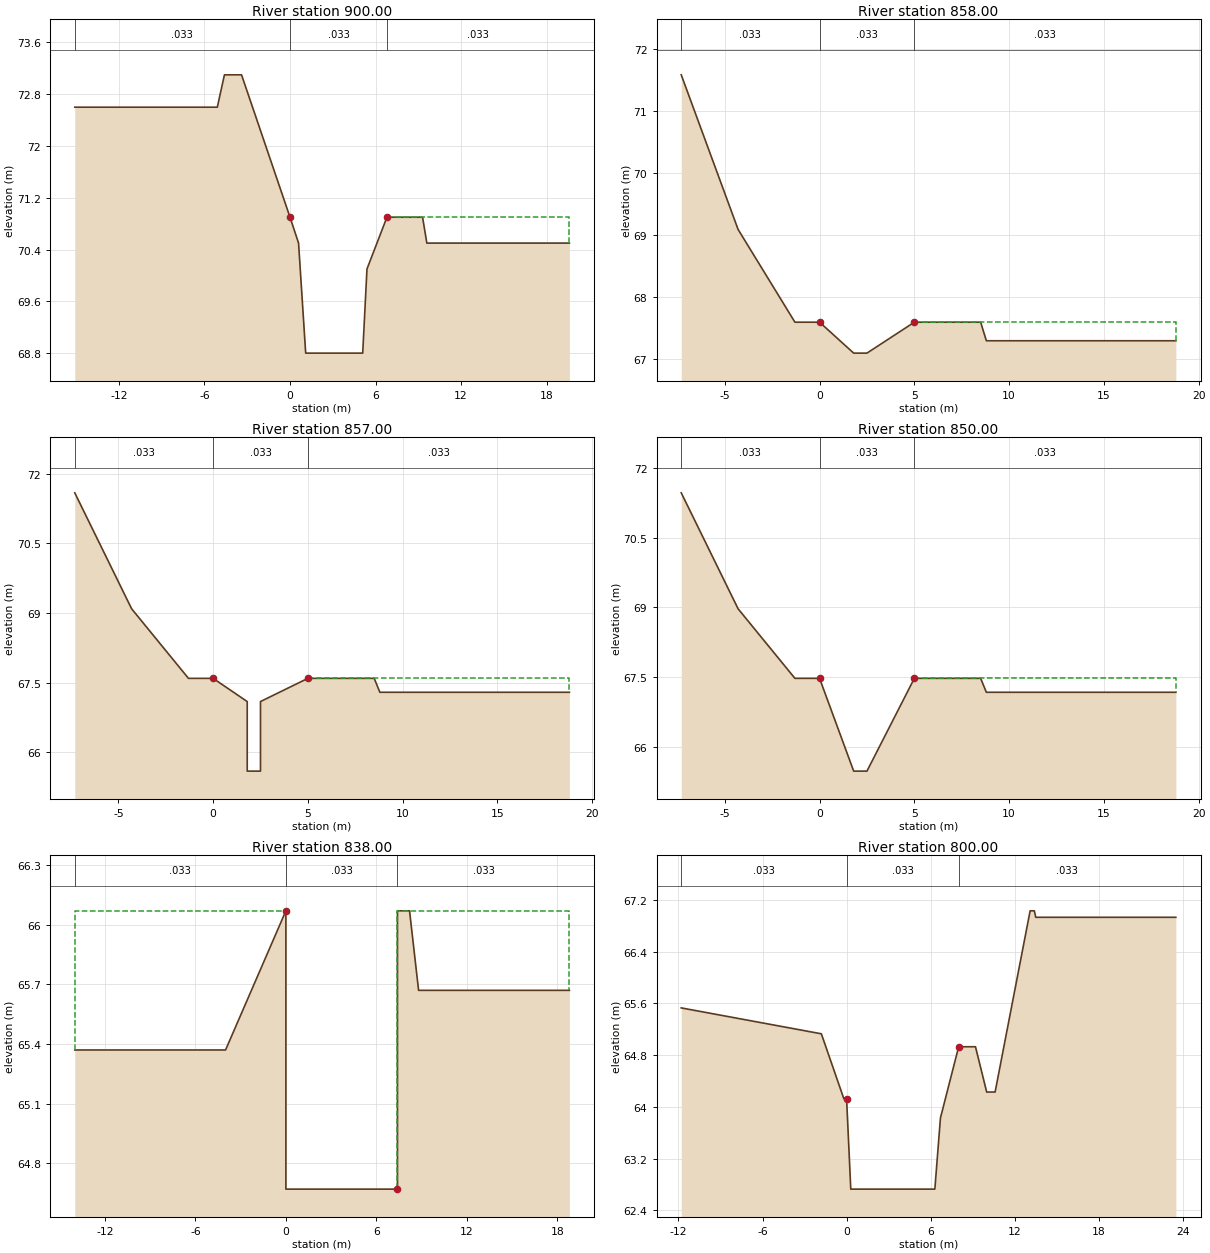
Type RM Length L Ch R = 1 ,900.00  ,42,42,42
BEGIN DESCRIPTION:
18
END DESCRIPTION:
#Sta/Elev= 13
   -15.1    72.6    -5.1    72.6    -4.6    73.1    -3.4    73.1       0    70.9
      .6    70.5     1.1    68.8     5.1    68.8     5.4    70.1     6.8    70.9
     9.3    70.9     9.6    70.5    19.6    70.5
#Mann= 3 , 0 , 0
   -15.1    .033       0       0    .033       0     6.8    .033       0
#XS Ineff= 2 , 0
               0    70.9     6.8            70.9
Permanent Ineff=
       F       F
Bank Sta=0,6.8
XS Rating Curve= 0
Exp/Cntr=.3,.1

Type RM Length L Ch R = 1 ,858.00  ,1,1,1
BEGIN DESCRIPTION:
17.008
END DESCRIPTION:
#Sta/Elev= 10
    -7.3   71.59    -4.3   69.09    -1.3   67.59       0   67.59     1.8   67.09
     2.5   67.09       5   67.59     8.5   67.59     8.8   67.29    18.8   67.29
#Mann= 3 , 0 , 0
    -7.3    .033       0       0    .033       0       5    .033       0
#XS Ineff= 2 , 0
               0   67.59       5           67.59
Permanent Ineff=
       F       F
Bank Sta=0,5
XS Rating Curve= 0
Exp/Cntr=.3,.1

Type RM Length L Ch R = 1 ,857.00  ,7,7,7
BEGIN DESCRIPTION:
17.007
END DESCRIPTION:
#Sta/Elev= 12
    -7.3   71.59    -4.3   69.09    -1.3   67.59       0   67.59     1.8   67.09
     1.8   65.59     2.5   65.59     2.5   67.09       5   67.59     8.5   67.59
     8.8   67.29    18.8   67.29
#Mann= 3 , 0 , 0
    -7.3    .033       0       0    .033       0       5    .033       0
#XS Ineff= 2 , 0
               0   67.59       5           67.59
Permanent Ineff=
       F       F
Bank Sta=0,5
XS Rating Curve= 0
Exp/Cntr=.3,.1

Type RM Length L Ch R = 1 ,850.00  ,12,12,12
BEGIN DESCRIPTION:
17
END DESCRIPTION:
#Sta/Elev= 10
    -7.3   71.47    -4.3   68.97    -1.3   67.47       0   67.47     1.8   65.47
     2.5   65.47       5   67.47     8.5   67.47     8.8   67.17    18.8   67.17
#Mann= 3 , 0 , 0
    -7.3    .033       0       0    .033       0       5    .033       0
#XS Ineff= 2 , 0
               0   67.47       5           67.47
Permanent Ineff=
       F       F
Bank Sta=0,5
XS Rating Curve= 0
Exp/Cntr=.3,.1

Type RM Length L Ch R = 1 ,838.00  ,38,38,38
BEGIN DESCRIPTION:
16.038
END DESCRIPTION:
#Sta/Elev= 9
     -14   65.37      -4   65.37       0   66.07       0   64.67     7.4   64.67
     7.4   66.07     8.2   66.07     8.8   65.67    18.8   65.67
#Mann= 3 , 0 , 0
     -14    .033       0       0    .033       0     7.4    .033       0
#XS Ineff= 2 , 0
               0   66.07     7.4           66.07
Permanent Ineff=
       F       F
Bank Sta=0,7.4
XS Rating Curve= 0
Exp/Cntr=.3,.1

Type RM Length L Ch R = 1 ,800.00  ,50,50,50
BEGIN DESCRIPTION:
16
END DESCRIPTION:
#Sta/Elev= 16
   -11.8   65.53    -6.8   65.33    -1.8   65.13     -.2   64.13       0   64.13
      .3   62.73     6.3   62.73     6.7   63.83       8   64.93     9.2   64.93
      10   64.23    10.6   64.23    13.1   67.03    13.4   67.03    13.5   66.93
    23.5   66.93
#Mann= 3 , 0 , 0
   -11.8    .033       0       0    .033       0       8    .033       0
#XS Ineff= 2 , 0
               0   64.13       8           64.93
Permanent Ineff=
       F       F
Bank Sta=0,8
XS Rating Curve= 0
Exp/Cntr=.3,.1

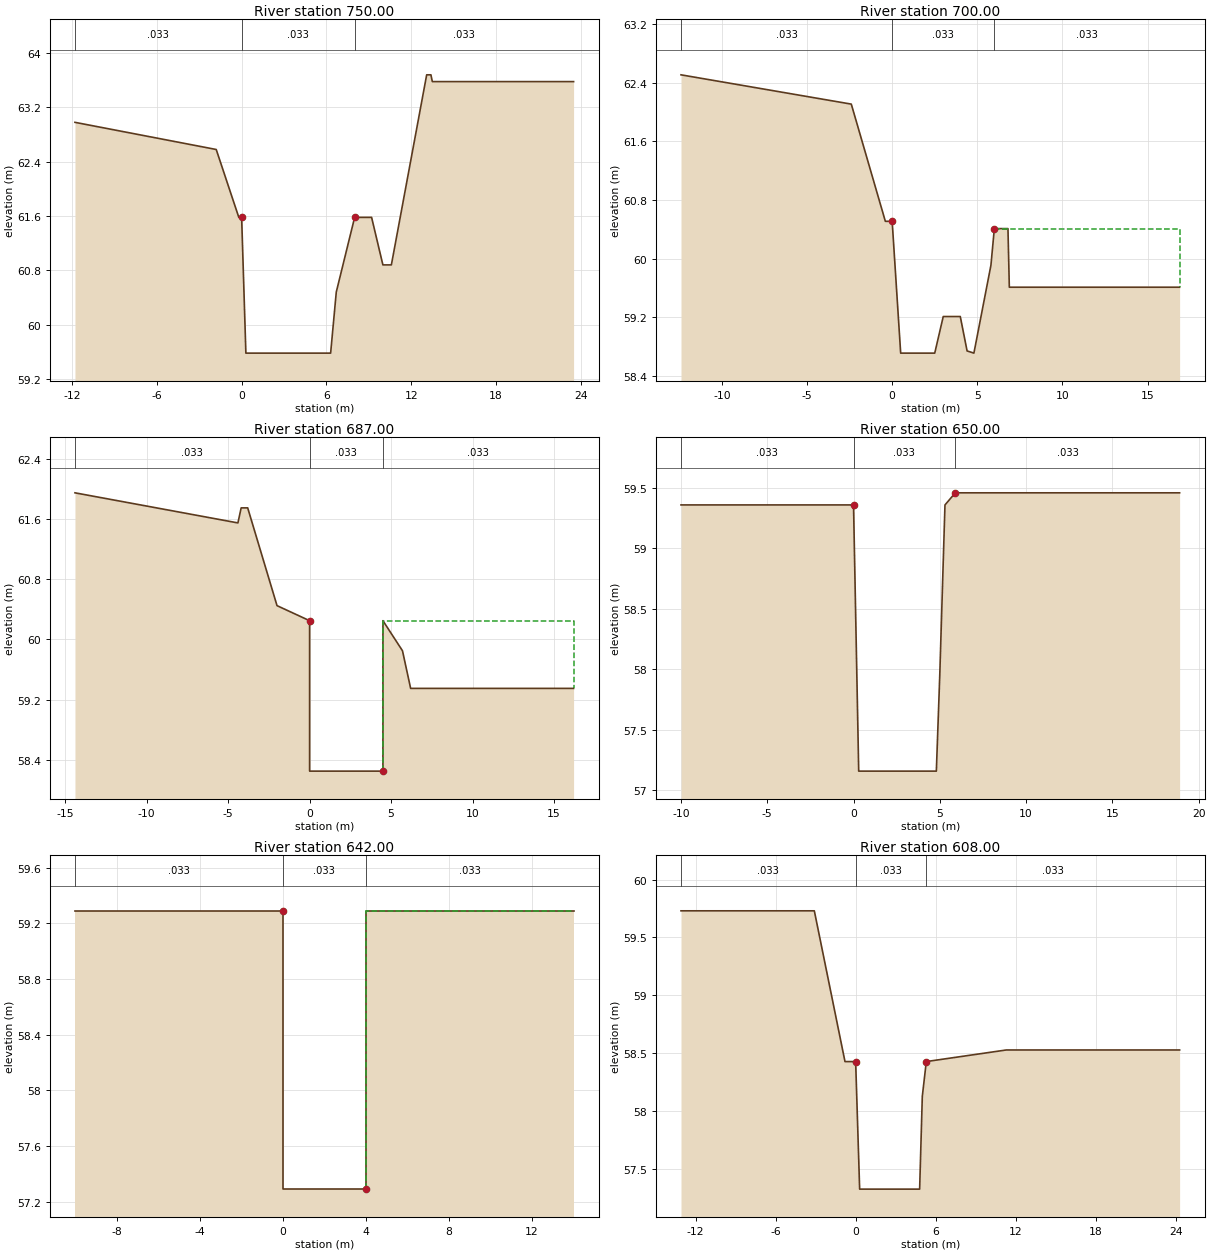
Type RM Length L Ch R = 1 ,750.00  ,50,50,50
BEGIN DESCRIPTION:
15
END DESCRIPTION:
#Sta/Elev= 16
   -11.8   62.98    -6.8   62.78    -1.8   62.58     -.2   61.58       0   61.58
      .3   59.58     6.3   59.58     6.7   60.48       8   61.58     9.2   61.58
      10   60.88    10.6   60.88    13.1   63.68    13.4   63.68    13.5   63.58
    23.5   63.58
#Mann= 3 , 0 , 0
   -11.8    .033       0       0    .033       0       8    .033       0
#XS Ineff= 2 , 0
               0   61.58       8           61.58
Permanent Ineff=
       F       F
Bank Sta=0,8
XS Rating Curve= 0
Exp/Cntr=.3,.1

Type RM Length L Ch R = 1 ,700.00  ,13,13,13
BEGIN DESCRIPTION:
14
END DESCRIPTION:
#Sta/Elev= 16
   -12.4   62.51    -7.4   62.31    -2.4   62.11     -.4   60.51       0   60.51
      .5   58.71     2.5   58.71       3   59.21       4   59.21     4.4   58.74
     4.8   58.71     5.8   59.91       6   60.41     6.8   60.41    6.88   59.61
   16.88   59.61
#Mann= 3 , 0 , 0
   -12.4    .033       0       0    .033       0       6    .033       0
#XS Ineff= 2 , 0
               0   60.51       6           60.41
Permanent Ineff=
       F       F
Bank Sta=0,6
XS Rating Curve= 0
Exp/Cntr=.3,.1

Type RM Length L Ch R = 1 ,687.00  ,37,37,37
BEGIN DESCRIPTION:
13.037
END DESCRIPTION:
#Sta/Elev= 13
   -14.4   61.95    -9.4   61.75    -4.4   61.55    -4.2   61.75    -3.8   61.75
      -2   60.45       0   60.25       0   58.25     4.5   58.25     4.5   60.25
     5.7   59.85     6.2   59.35    16.2   59.35
#Mann= 3 , 0 , 0
   -14.4    .033       0       0    .033       0     4.5    .033       0
#XS Ineff= 2 , 0
               0   60.25     4.5           60.25
Permanent Ineff=
       F       F
Bank Sta=0,4.5
XS Rating Curve= 0
Exp/Cntr=.3,.1

Type RM Length L Ch R = 1 ,650.00  ,8,8,8
BEGIN DESCRIPTION:
13
END DESCRIPTION:
#Sta/Elev= 9
     -10   59.36       0   59.36      .3   57.16     4.8   57.16       5   57.96
     5.3   59.36     5.9   59.46     8.9   59.46    18.9   59.46
#Mann= 3 , 0 , 0
     -10    .033       0       0    .033       0     5.9    .033       0
#XS Ineff= 2 , 0
               0   59.36     5.9           59.46
Permanent Ineff=
       F       F
Bank Sta=0,5.9
XS Rating Curve= 0
Exp/Cntr=.3,.1

Type RM Length L Ch R = 1 ,642.00  ,34,34,34
BEGIN DESCRIPTION:
12.042
END DESCRIPTION:
#Sta/Elev= 6
     -10   59.29       0   59.29       0   57.29       4   57.29       4   59.29
      14   59.29
#Mann= 3 , 0 , 0
     -10    .033       0       0    .033       0       4    .033       0
#XS Ineff= 2 , 0
               0   59.29       4           59.29
Permanent Ineff=
       F       F
Bank Sta=0,4
XS Rating Curve= 0
Exp/Cntr=.3,.1

Type RM Length L Ch R = 1 ,608.00  ,1,1,1
BEGIN DESCRIPTION:
12.008
END DESCRIPTION:
#Sta/Elev= 11
   -13.1   59.73    -3.1   59.73     -.8   58.43       0   58.43      .3   57.33
     4.8   57.33       5   58.13     5.3   58.43    11.3   58.53    14.3   58.53
    24.3   58.53
#Mann= 3 , 0 , 0
   -13.1    .033       0       0    .033       0     5.3    .033       0
#XS Ineff= 2 , 0
               0   58.43     5.3           58.43
Permanent Ineff=
       F       F
Bank Sta=0,5.3
XS Rating Curve= 0
Exp/Cntr=.3,.1

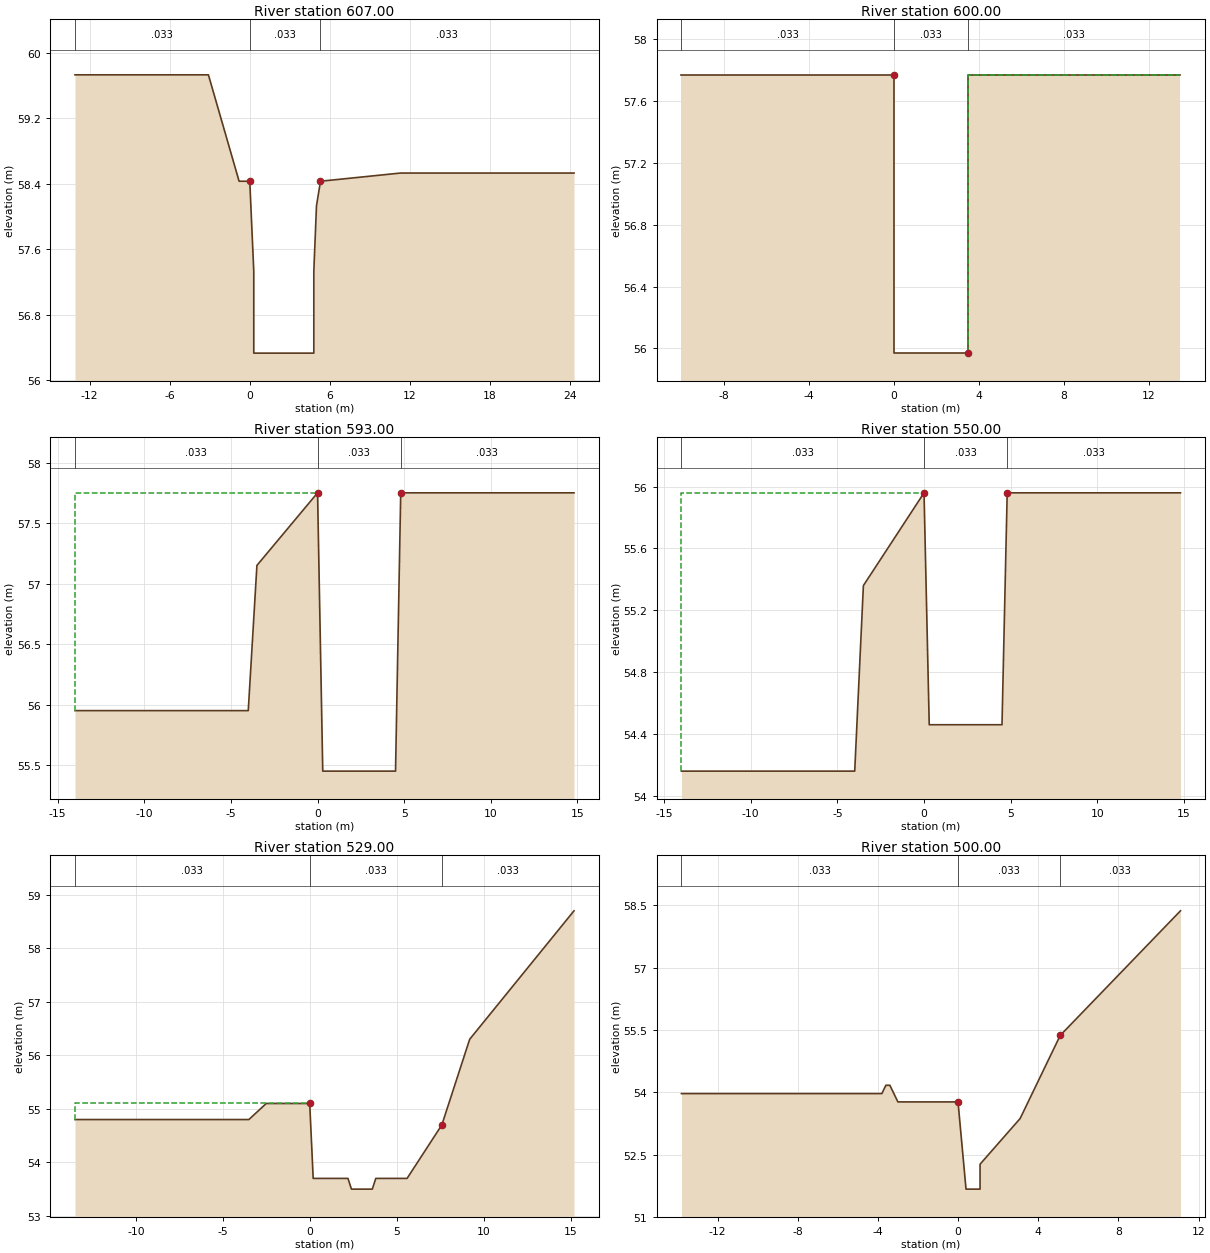
Type RM Length L Ch R = 1 ,607.00  ,7,7,7
BEGIN DESCRIPTION:
12.007
END DESCRIPTION:
#Sta/Elev= 13
   -13.1   59.73    -3.1   59.73     -.8   58.43       0   58.43      .3   57.33
      .3   56.33     4.8   56.33     4.8   57.33       5   58.13     5.3   58.43
    11.3   58.53    14.3   58.53    24.3   58.53
#Mann= 3 , 0 , 0
   -13.1    .033       0       0    .033       0     5.3    .033       0
#XS Ineff= 2 , 0
               0   58.43     5.3           58.43
Permanent Ineff=
       F       F
Bank Sta=0,5.3
XS Rating Curve= 0
Exp/Cntr=.3,.1

Type RM Length L Ch R = 1 ,600.00  ,7,7,7
BEGIN DESCRIPTION:
12
END DESCRIPTION:
#Sta/Elev= 6
     -10   57.77       0   57.77       0   55.97     3.5   55.97     3.5   57.77
    13.5   57.77
#Mann= 3 , 0 , 0
     -10    .033       0       0    .033       0     3.5    .033       0
#XS Ineff= 2 , 0
               0   57.77     3.5           57.77
Permanent Ineff=
       F       F
Bank Sta=0,3.5
XS Rating Curve= 0
Exp/Cntr=.3,.1

Type RM Length L Ch R = 1 ,593.00  ,43,43,43
BEGIN DESCRIPTION:
11.043
END DESCRIPTION:
#Sta/Elev= 8
     -14   55.95      -4   55.95    -3.5   57.15       0   57.75      .3   55.45
     4.5   55.45     4.8   57.75    14.8   57.75
#Mann= 3 , 0 , 0
     -14    .033       0       0    .033       0     4.8    .033       0
#XS Ineff= 2 , 0
               0   57.75     4.8           57.75
Permanent Ineff=
       F       F
Bank Sta=0,4.8
XS Rating Curve= 0
Exp/Cntr=.3,.1

Type RM Length L Ch R = 1 ,550.00  ,21,21,21
BEGIN DESCRIPTION:
11
END DESCRIPTION:
#Sta/Elev= 8
     -14   54.16      -4   54.16    -3.5   55.36       0   55.96      .3   54.46
     4.5   54.46     4.8   55.96    14.8   55.96
#Mann= 3 , 0 , 0
     -14    .033       0       0    .033       0     4.8    .033       0
#XS Ineff= 2 , 0
               0   55.96     4.8           55.96
Permanent Ineff=
       F       F
Bank Sta=0,4.8
XS Rating Curve= 0
Exp/Cntr=.3,.1

Type RM Length L Ch R = 1 ,529.00  ,29,29,29
BEGIN DESCRIPTION:
10.029
END DESCRIPTION:
#Sta/Elev= 14
   -13.5    54.8    -3.5    54.8    -2.5    55.1       0    55.1      .2    53.7
     2.2    53.7     2.4    53.5     3.6    53.5     3.8    53.7     5.6    53.7
     7.6    54.7     9.2    56.3    12.2    57.5    15.2    58.7
#Mann= 3 , 0 , 0
   -13.5    .033       0       0    .033       0     7.6    .033       0
#XS Ineff= 2 , 0
               0    55.1     7.6            54.7
Permanent Ineff=
       F       F
Bank Sta=0,7.6
XS Rating Curve= 0
Exp/Cntr=.3,.1

Type RM Length L Ch R = 1 ,500.00  ,33,33,33
BEGIN DESCRIPTION:
10
END DESCRIPTION:
#Sta/Elev= 13
   -13.8   53.97    -3.8   53.97    -3.6   54.17    -3.4   54.17      -3   53.77
       0   53.77      .4   51.67     1.1   51.67     1.1   52.27     3.1   53.37
     5.1   55.37     8.1   56.87    11.1   58.37
#Mann= 3 , 0 , 0
   -13.8    .033       0       0    .033       0     5.1    .033       0
#XS Ineff= 2 , 0
               0   53.77     5.1           55.37
Permanent Ineff=
       F       F
Bank Sta=0,5.1
XS Rating Curve= 0
Exp/Cntr=.3,.1

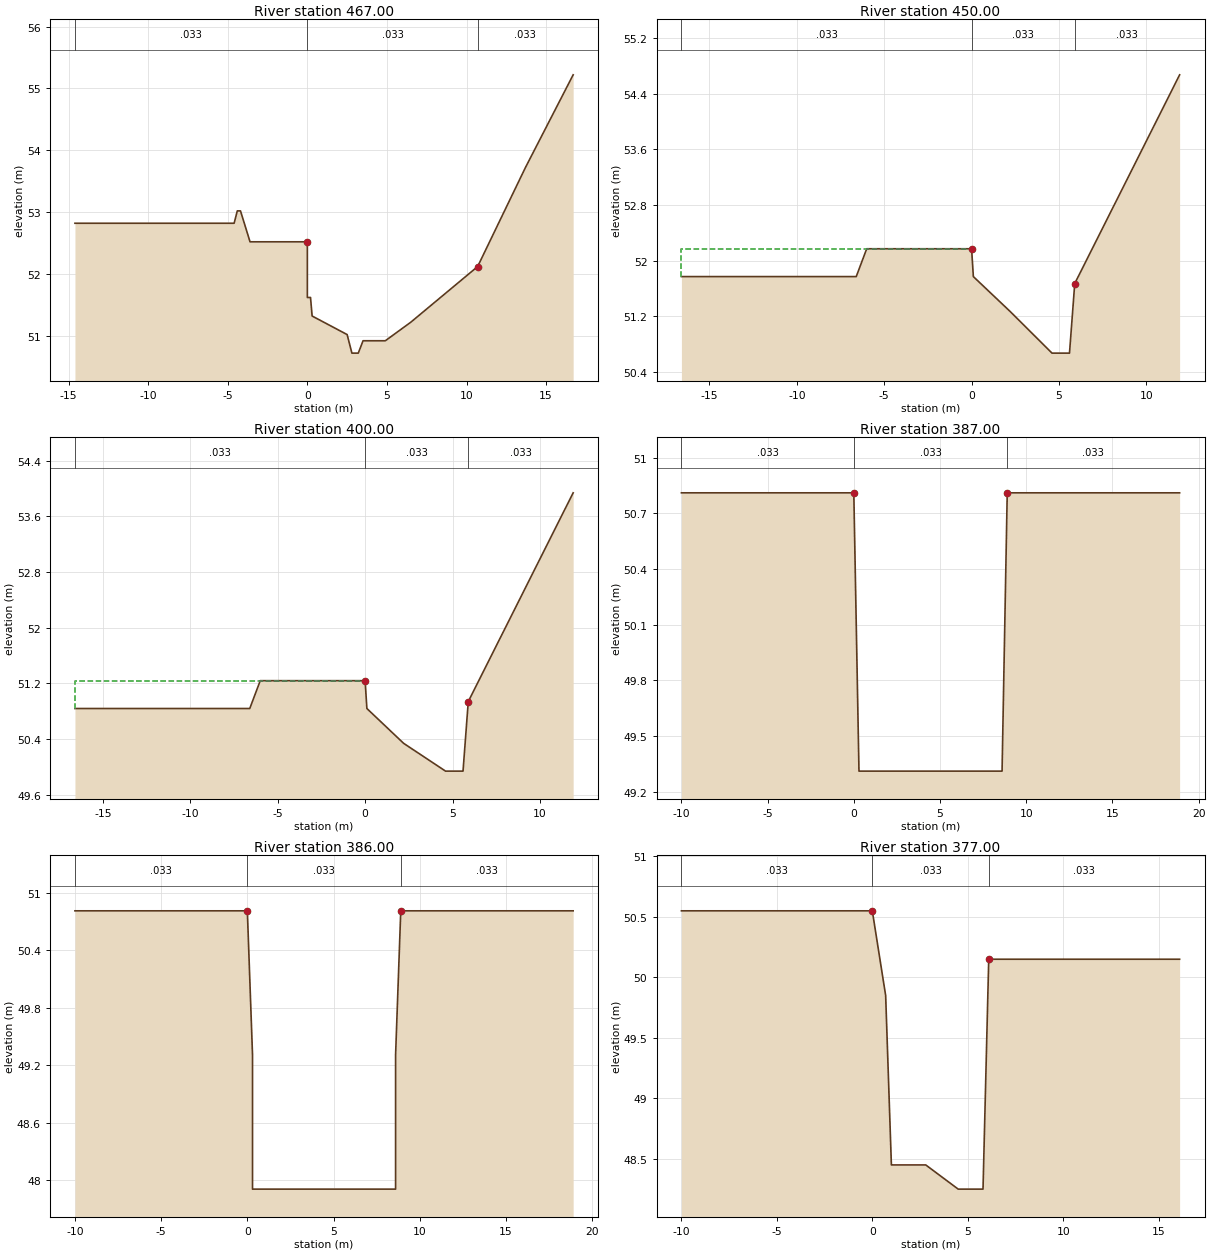
Type RM Length L Ch R = 1 ,467.00  ,17,17,17
BEGIN DESCRIPTION:
9.017
END DESCRIPTION:
#Sta/Elev= 19
   -14.6   52.82    -4.6   52.82    -4.4   53.02    -4.2   53.02    -3.6   52.52
      -3   52.52       0   52.52       0   51.62      .2   51.62      .3   51.32
     2.5   51.02     2.8   50.72     3.2   50.72     3.5   50.92     4.9   50.92
     6.5   51.22    10.7   52.12    13.7   53.72    16.7   55.22
#Mann= 3 , 0 , 0
   -14.6    .033       0       0    .033       0    10.7    .033       0
#XS Ineff= 2 , 0
               0   52.52    10.7           52.12
Permanent Ineff=
       F       F
Bank Sta=0,10.7
XS Rating Curve= 0
Exp/Cntr=.3,.1

Type RM Length L Ch R = 1 ,450.00  ,50,50,50
BEGIN DESCRIPTION:
9
END DESCRIPTION:
#Sta/Elev= 12
   -16.6   51.77    -6.6   51.77      -6   52.17      -3   52.17       0   52.17
      .1   51.77     2.2   51.27     4.6   50.67     5.6   50.67     5.9   51.67
     8.9   53.17    11.9   54.67
#Mann= 3 , 0 , 0
   -16.6    .033       0       0    .033       0     5.9    .033       0
#XS Ineff= 2 , 0
               0   52.17     5.9           51.67
Permanent Ineff=
       F       F
Bank Sta=0,5.9
XS Rating Curve= 0
Exp/Cntr=.3,.1

Type RM Length L Ch R = 1 ,400.00  ,13,13,13
BEGIN DESCRIPTION:
8
END DESCRIPTION:
#Sta/Elev= 12
   -16.6   50.84    -6.6   50.84      -6   51.24      -3   51.24       0   51.24
      .1   50.84     2.2   50.34     4.6   49.94     5.6   49.94     5.9   50.94
     8.9   52.44    11.9   53.94
#Mann= 3 , 0 , 0
   -16.6    .033       0       0    .033       0     5.9    .033       0
#XS Ineff= 2 , 0
               0   51.24     5.9           50.94
Permanent Ineff=
       F       F
Bank Sta=0,5.9
XS Rating Curve= 0
Exp/Cntr=.3,.1

Type RM Length L Ch R = 1 ,387.00  ,1,1,1
BEGIN DESCRIPTION:
7.037
END DESCRIPTION:
#Sta/Elev= 6
     -10   50.81       0   50.81      .3   49.31     8.6   49.31     8.9   50.81
    18.9   50.81
#Mann= 3 , 0 , 0
     -10    .033       0       0    .033       0     8.9    .033       0
#XS Ineff= 2 , 0
               0   50.81     8.9           50.81
Permanent Ineff=
       F       F
Bank Sta=0,8.9
XS Rating Curve= 0
Exp/Cntr=.3,.1

Type RM Length L Ch R = 1 ,386.00  ,9,9,9
BEGIN DESCRIPTION:
7.036
END DESCRIPTION:
#Sta/Elev= 8
     -10   50.81       0   50.81      .3   49.31      .3   47.91     8.6   47.91
     8.6   49.31     8.9   50.81    18.9   50.81
#Mann= 3 , 0 , 0
     -10    .033       0       0    .033       0     8.9    .033       0
#XS Ineff= 2 , 0
               0   50.81     8.9           50.81
Permanent Ineff=
       F       F
Bank Sta=0,8.9
XS Rating Curve= 0
Exp/Cntr=.3,.1

Type RM Length L Ch R = 1 ,377.00  ,27,27,27
BEGIN DESCRIPTION:
7.027
END DESCRIPTION:
#Sta/Elev= 9
     -10   50.55       0   50.55      .7   49.85       1   48.45     2.8   48.45
     4.5   48.25     5.8   48.25     6.1   50.15    16.1   50.15
#Mann= 3 , 0 , 0
     -10    .033       0       0    .033       0     6.1    .033       0
#XS Ineff= 2 , 0
               0   50.55     6.1           50.15
Permanent Ineff=
       F       F
Bank Sta=0,6.1
XS Rating Curve= 0
Exp/Cntr=.3,.1

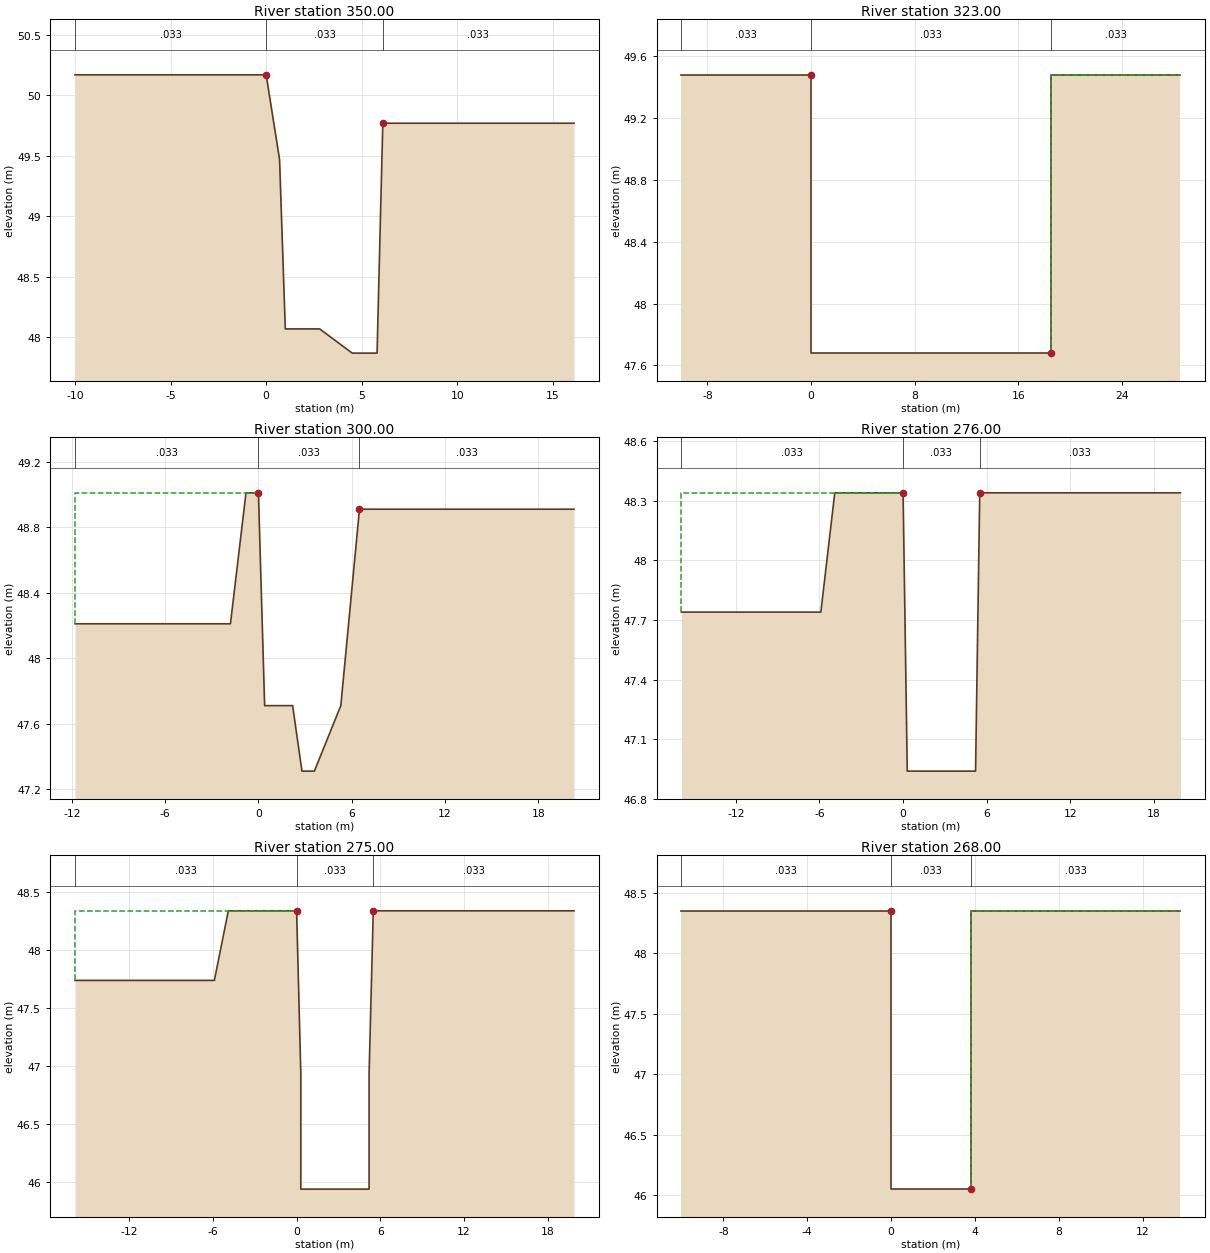
Type RM Length L Ch R = 1 ,350.00  ,27,27,27
BEGIN DESCRIPTION:
7
END DESCRIPTION:
#Sta/Elev= 9
     -10   50.17       0   50.17      .7   49.47       1   48.07     2.8   48.07
     4.5   47.87     5.8   47.87     6.1   49.77    16.1   49.77
#Mann= 3 , 0 , 0
     -10    .033       0       0    .033       0     6.1    .033       0
#XS Ineff= 2 , 0
               0   50.17     6.1           49.77
Permanent Ineff=
       F       F
Bank Sta=0,6.1
XS Rating Curve= 0
Exp/Cntr=.3,.1

Type RM Length L Ch R = 1 ,323.00  ,23,23,23
BEGIN DESCRIPTION:
6.023
END DESCRIPTION:
#Sta/Elev= 6
     -10   49.48       0   49.48       0   47.68    18.5   47.68    18.5   49.48
    28.5   49.48
#Mann= 3 , 0 , 0
     -10    .033       0       0    .033       0    18.5    .033       0
#XS Ineff= 2 , 0
               0   49.48    18.5           49.48
Permanent Ineff=
       F       F
Bank Sta=0,18.5
XS Rating Curve= 0
Exp/Cntr=.3,.1

Type RM Length L Ch R = 1 ,300.00  ,24,24,24
BEGIN DESCRIPTION:
6
END DESCRIPTION:
#Sta/Elev= 12
   -11.8   48.21    -1.8   48.21     -.8   49.01       0   49.01      .4   47.71
     2.2   47.71     2.8   47.31     3.6   47.31     5.3   47.71     6.5   48.91
    10.3   48.91    20.3   48.91
#Mann= 3 , 0 , 0
   -11.8    .033       0       0    .033       0     6.5    .033       0
#XS Ineff= 2 , 0
               0   49.01     6.5           48.91
Permanent Ineff=
       F       F
Bank Sta=0,6.5
XS Rating Curve= 0
Exp/Cntr=.3,.1

Type RM Length L Ch R = 1 ,276.00  ,1,1,1
BEGIN DESCRIPTION:
5.026
END DESCRIPTION:
#Sta/Elev= 10
   -15.9   47.74    -5.9   47.74    -4.9   48.34     -.9   48.34       0   48.34
      .3   46.94     5.2   46.94     5.5   48.34     9.9   48.34    19.9   48.34
#Mann= 3 , 0 , 0
   -15.9    .033       0       0    .033       0     5.5    .033       0
#XS Ineff= 2 , 0
               0   48.34     5.5           48.34
Permanent Ineff=
       F       F
Bank Sta=0,5.5
XS Rating Curve= 0
Exp/Cntr=.3,.1

Type RM Length L Ch R = 1 ,275.00  ,7,7,7
BEGIN DESCRIPTION:
5.025
END DESCRIPTION:
#Sta/Elev= 12
   -15.9   47.74    -5.9   47.74    -4.9   48.34     -.9   48.34       0   48.34
      .3   46.94      .3   45.94     5.2   45.94     5.2   46.94     5.5   48.34
     9.9   48.34    19.9   48.34
#Mann= 3 , 0 , 0
   -15.9    .033       0       0    .033       0     5.5    .033       0
#XS Ineff= 2 , 0
               0   48.34     5.5           48.34
Permanent Ineff=
       F       F
Bank Sta=0,5.5
XS Rating Curve= 0
Exp/Cntr=.3,.1

Type RM Length L Ch R = 1 ,268.00  ,18,18,18
BEGIN DESCRIPTION:
5.018
END DESCRIPTION:
#Sta/Elev= 6
     -10   48.35       0   48.35       0   46.05     3.8   46.05     3.8   48.35
    13.8   48.35
#Mann= 3 , 0 , 0
     -10    .033       0       0    .033       0     3.8    .033       0
#XS Ineff= 2 , 0
               0   48.35     3.8           48.35
Permanent Ineff=
       F       F
Bank Sta=0,3.8
XS Rating Curve= 0
Exp/Cntr=.3,.1

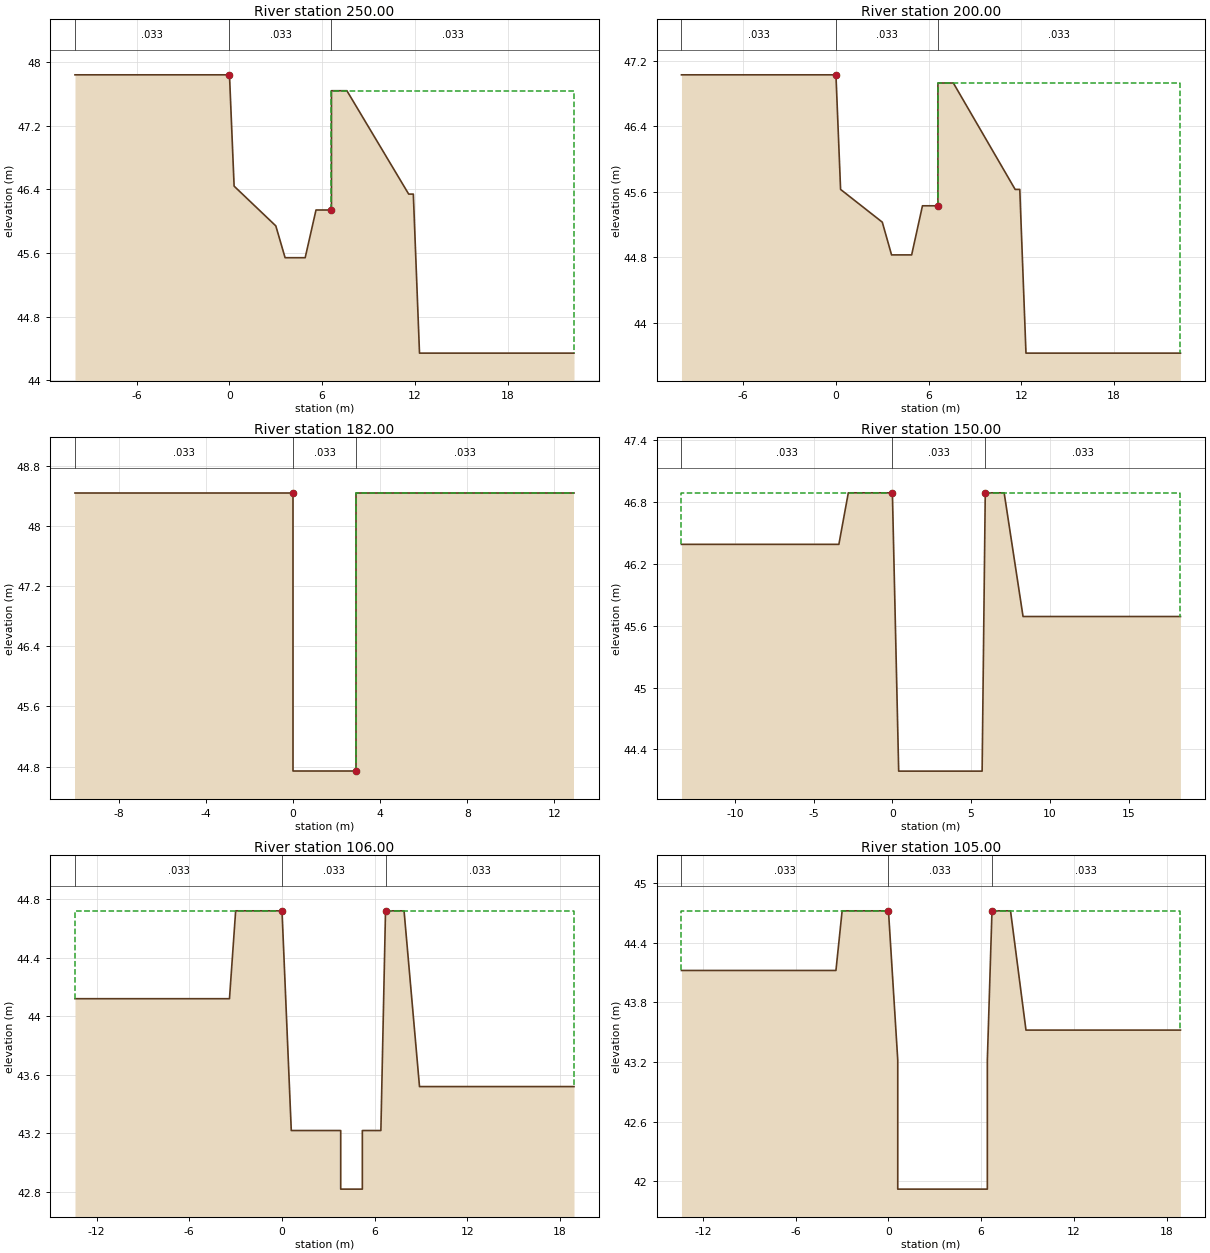
Type RM Length L Ch R = 1 ,250.00  ,50,50,50
BEGIN DESCRIPTION:
5
END DESCRIPTION:
#Sta/Elev= 15
     -10   47.84       0   47.84      .3   46.44       3   45.94     3.6   45.54
     4.9   45.54     5.6   46.14     6.6   46.14     6.6   47.64     6.9   47.64
     7.6   47.64    11.6   46.34    11.9   46.34    12.3   44.34    22.3   44.34
#Mann= 3 , 0 , 0
     -10    .033       0       0    .033       0     6.6    .033       0
#XS Ineff= 2 , 0
               0   47.84     6.6           47.64
Permanent Ineff=
       F       F
Bank Sta=0,6.6
XS Rating Curve= 0
Exp/Cntr=.3,.1

Type RM Length L Ch R = 1 ,200.00  ,18,18,18
BEGIN DESCRIPTION:
4
END DESCRIPTION:
#Sta/Elev= 15
     -10   47.03       0   47.03      .3   45.63       3   45.23     3.6   44.83
     4.9   44.83     5.6   45.43     6.6   45.43     6.6   46.93     6.9   46.93
     7.6   46.93    11.6   45.63    11.9   45.63    12.3   43.63    22.3   43.63
#Mann= 3 , 0 , 0
     -10    .033       0       0    .033       0     6.6    .033       0
#XS Ineff= 2 , 0
               0   47.03     6.6           46.93
Permanent Ineff=
       F       F
Bank Sta=0,6.6
XS Rating Curve= 0
Exp/Cntr=.3,.1

Type RM Length L Ch R = 1 ,182.00  ,32,32,32
BEGIN DESCRIPTION:
3.032
END DESCRIPTION:
#Sta/Elev= 6
     -10   48.44       0   48.44       0   44.74     2.9   44.74     2.9   48.44
    12.9   48.44
#Mann= 3 , 0 , 0
     -10    .033       0       0    .033       0     2.9    .033       0
#XS Ineff= 2 , 0
               0   48.44     2.9           48.44
Permanent Ineff=
       F       F
Bank Sta=0,2.9
XS Rating Curve= 0
Exp/Cntr=.3,.1

Type RM Length L Ch R = 1 ,150.00  ,44,44,44
BEGIN DESCRIPTION:
3
END DESCRIPTION:
#Sta/Elev= 10
   -13.4   46.39    -3.4   46.39    -2.8   46.89       0   46.89      .4   44.19
     5.7   44.19     5.9   46.89     7.1   46.89     8.3   45.69    18.3   45.69
#Mann= 3 , 0 , 0
   -13.4    .033       0       0    .033       0     5.9    .033       0
#XS Ineff= 2 , 0
               0   46.89     5.9           46.89
Permanent Ineff=
       F       F
Bank Sta=0,5.9
XS Rating Curve= 0
Exp/Cntr=.3,.1

Type RM Length L Ch R = 1 ,106.00  ,1,1,1
BEGIN DESCRIPTION:
2.006
END DESCRIPTION:
#Sta/Elev= 15
   -13.4   44.12    -3.4   44.12      -3   44.72       0   44.72      .2   44.22
      .6   43.22     3.8   43.22     3.8   42.82     5.2   42.82     5.2   43.22
     6.4   43.22     6.7   44.72     7.9   44.72     8.9   43.52    18.9   43.52
#Mann= 3 , 0 , 0
   -13.4    .033       0       0    .033       0     6.7    .033       0
#XS Ineff= 2 , 0
               0   44.72     6.7           44.72
Permanent Ineff=
       F       F
Bank Sta=0,6.7
XS Rating Curve= 0
Exp/Cntr=.3,.1

Type RM Length L Ch R = 1 ,105.00  ,5,5,5
BEGIN DESCRIPTION:
2.005
END DESCRIPTION:
#Sta/Elev= 13
   -13.4   44.12    -3.4   44.12      -3   44.72       0   44.72      .2   44.22
      .6   43.22      .6   41.92     6.4   41.92     6.4   43.22     6.7   44.72
     7.9   44.72     8.9   43.52    18.9   43.52
#Mann= 3 , 0 , 0
   -13.4    .033       0       0    .033       0     6.7    .033       0
#XS Ineff= 2 , 0
               0   44.72     6.7           44.72
Permanent Ineff=
       F       F
Bank Sta=0,6.7
XS Rating Curve= 0
Exp/Cntr=.3,.1