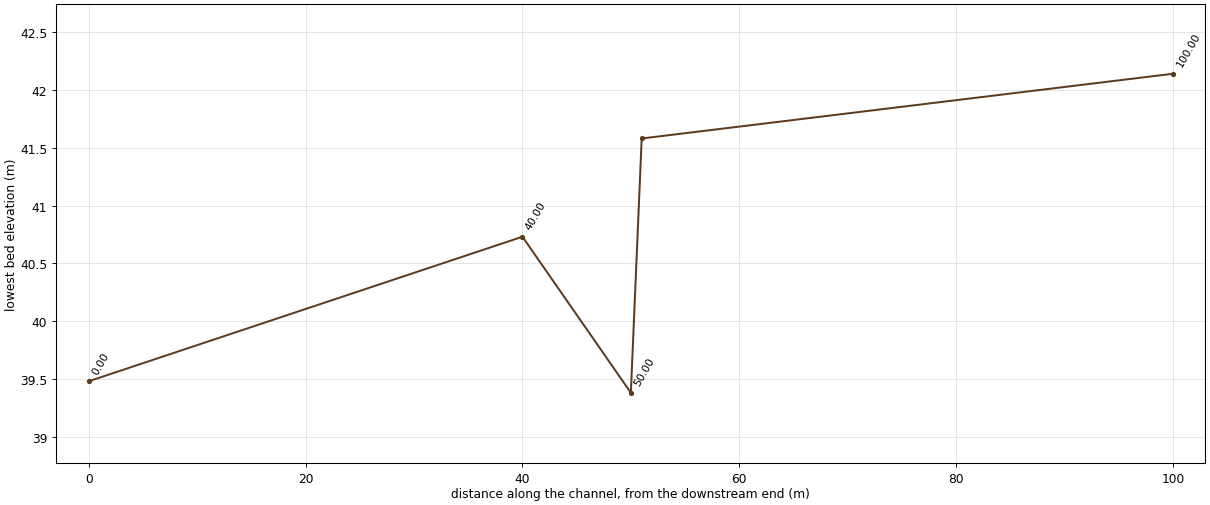
HEC-RAS study SINJ.prj: SINJ

--- SINJ.g01 (geometry) --- (continued)

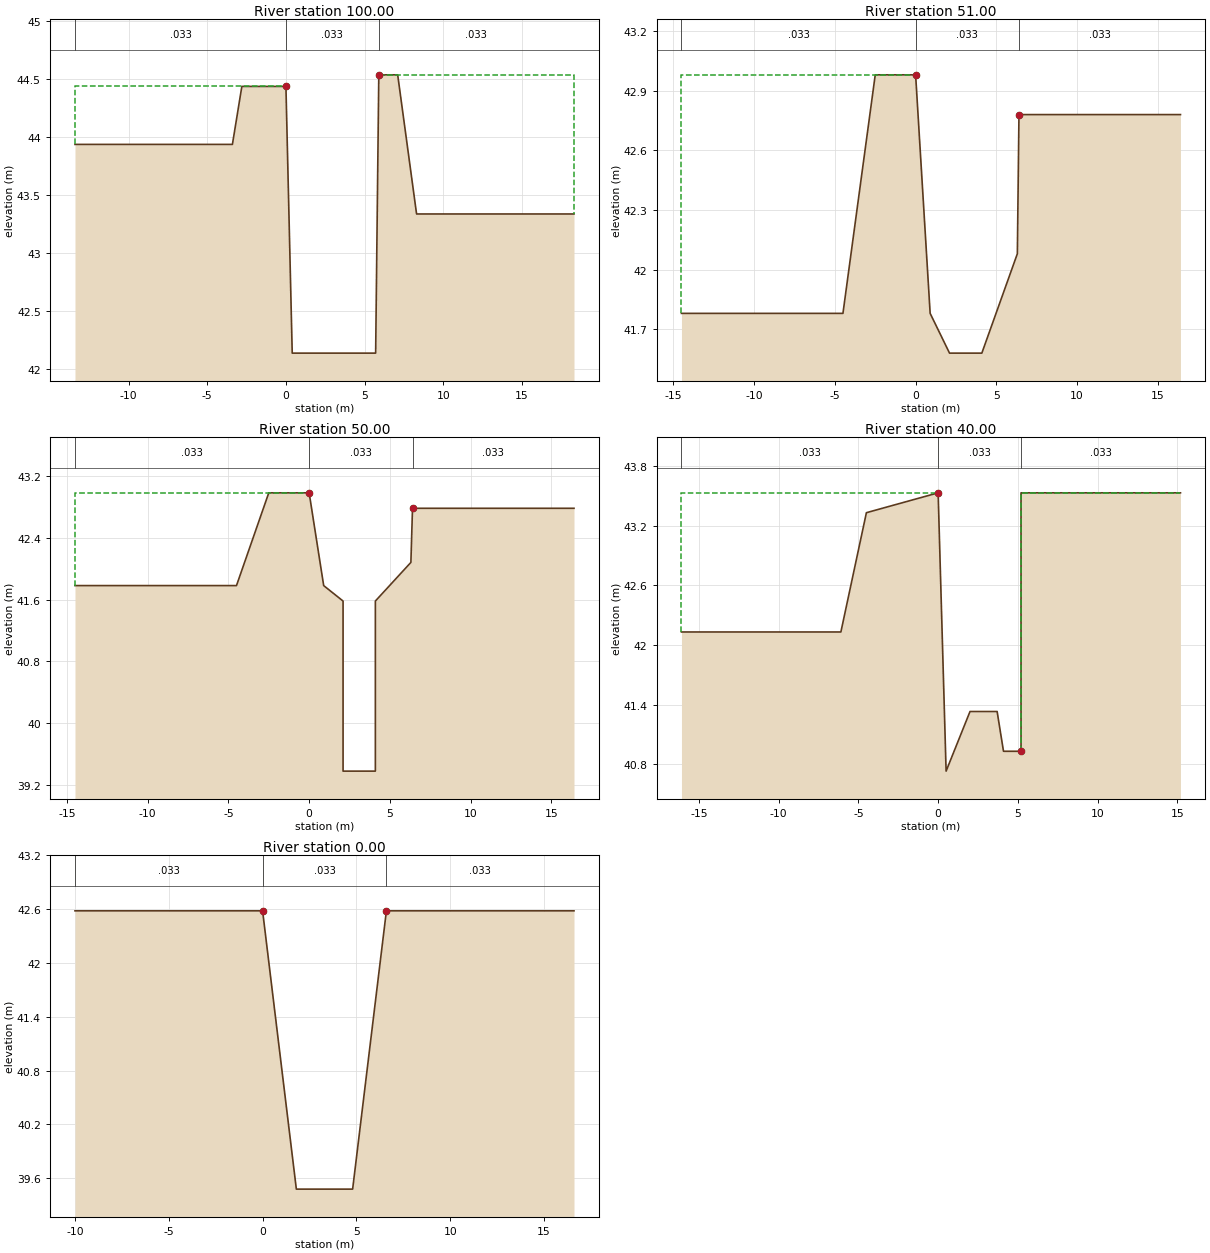
Type RM Length L Ch R = 1 ,100.00  ,49,49,49
BEGIN DESCRIPTION:
2
END DESCRIPTION:
#Sta/Elev= 10
   -13.4   43.94    -3.4   43.94    -2.8   44.44       0   44.44      .4   42.14
     5.7   42.14     5.9   44.54     7.1   44.54     8.3   43.34    18.3   43.34
#Mann= 3 , 0 , 0
   -13.4    .033       0       0    .033       0     5.9    .033       0
#XS Ineff= 2 , 0
               0   44.44     5.9           44.54
Permanent Ineff=
       F       F
Bank Sta=0,5.9
XS Rating Curve= 0
Exp/Cntr=.3,.1

Type RM Length L Ch R = 1 ,51.00   ,1,1,1
BEGIN DESCRIPTION:
1.001
END DESCRIPTION:
#Sta/Elev= 10
   -14.5   41.78    -4.5   41.78    -2.5   42.98       0   42.98      .9   41.78
     2.1   41.58     4.1   41.58     6.3   42.08     6.4   42.78    16.4   42.78
#Mann= 3 , 0 , 0
   -14.5    .033       0       0    .033       0     6.4    .033       0
#XS Ineff= 2 , 0
               0   42.98     6.4           42.78
Permanent Ineff=
       F       F
Bank Sta=0,6.4
XS Rating Curve= 0
Exp/Cntr=.3,.1

Type RM Length L Ch R = 1 ,50.00   ,10,10,10
BEGIN DESCRIPTION:
1
END DESCRIPTION:
#Sta/Elev= 12
   -14.5   41.78    -4.5   41.78    -2.5   42.98       0   42.98      .9   41.78
     2.1   41.58     2.1   39.38     4.1   39.38     4.1   41.58     6.3   42.08
     6.4   42.78    16.4   42.78
#Mann= 3 , 0 , 0
   -14.5    .033       0       0    .033       0     6.4    .033       0
#XS Ineff= 2 , 0
               0   42.98     6.4           42.78
Permanent Ineff=
       F       F
Bank Sta=0,6.4
XS Rating Curve= 0
Exp/Cntr=.3,.1

Type RM Length L Ch R = 1 ,40.00   ,40,40,40
BEGIN DESCRIPTION:
0.04
END DESCRIPTION:
#Sta/Elev= 11
   -16.1   42.13    -6.1   42.13    -4.5   43.33       0   43.53      .5   40.73
       2   41.33     3.7   41.33     4.1   40.93     5.2   40.93     5.2   43.53
    15.2   43.53
#Mann= 3 , 0 , 0
   -16.1    .033       0       0    .033       0     5.2    .033       0
#XS Ineff= 2 , 0
               0   43.53     5.2           43.53
Permanent Ineff=
       F       F
Bank Sta=0,5.2
XS Rating Curve= 0
Exp/Cntr=.3,.1

Type RM Length L Ch R = 1 ,0.00    ,0,0,0
BEGIN DESCRIPTION:
0
END DESCRIPTION:
#Sta/Elev= 6
     -10   42.58       0   42.58     1.8   39.48     4.8   39.48     6.6   42.58
    16.6   42.58
#Mann= 3 , 0 , 0
     -10    .033       0       0    .033       0     6.6    .033       0
#XS Ineff= 2 , 0
               0   42.58     6.6           42.58
Permanent Ineff=
       F       F
Bank Sta=0,6.6
XS Rating Curve= 0
Exp/Cntr=.3,.1

Chan Stop Cuts=-1