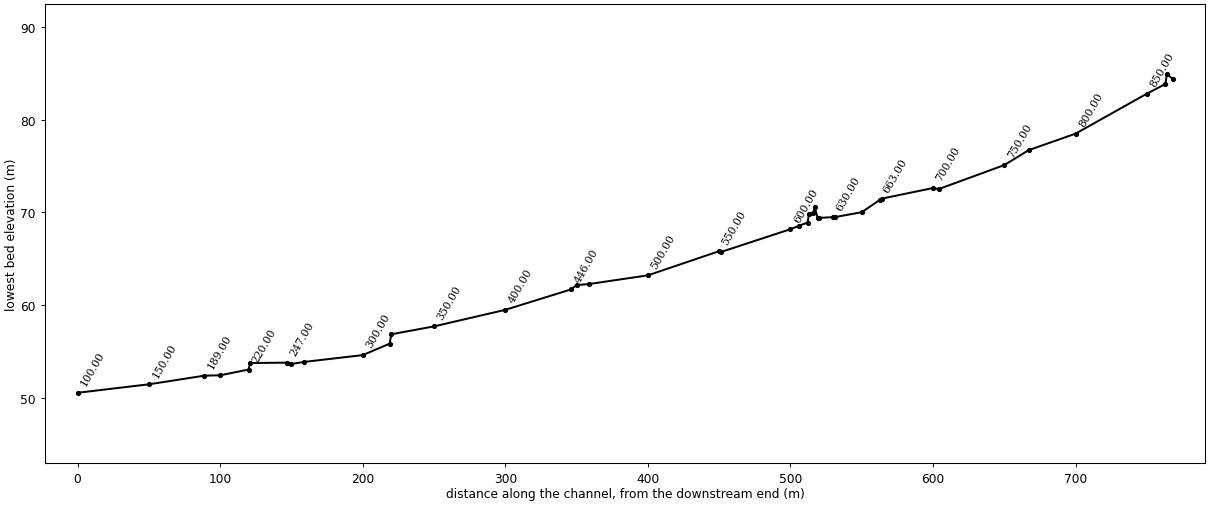
--- TONG.prj (project) ---

Proj Title=TONG
Current Plan=p01
Default Exp/Contr=.3,.1
SI Units
Geom File=g01
Flow File=f01
Plan File=p01
Y Axis Title=Elevation
X Axis Title(PF)=Main Channel Distance
X Axis Title(XS)=Station
BEGIN DESCRIPTION:
           BACK WATER COMPUTATION
      APPLICATION OF HEC-2 BY Samju Construction Engineering
      TONGJUM-STREEM : 30 YR
END DESCRIPTION:
DSS Export Rating Curves= 0
DSS Export Rating Curve Sorted= 0
DSS Export Volume Flow Curves= 0
DXF OffsetX= 0
DXF OffsetY= 0
DXF ScaleX= 1
DXF ScaleY= 10

--- TONG.p01 (plan) ---

Plan Title=Imported Plan 01
Version=Version 3.0.1  Mar 2001
Short Identifier=Imported Pla
Geom File=g01
Flow File=f01
Subcritical Flow
K Sum by GR= 0
Std Step Tol= 0.003
Critical Tol= 0.003
Num of Std Step Trials= 20
Max Error Tol= 0.1
Flow Tol Ratio= 0.001
Split Flow NTrial= 30
Split Flow Tol= 0.02
Split Flow Ratio= 0.02
Log Output Level= 0
Friction Slope Method= 1
Unsteady Friction Slope Method= 2
Parabolic Critical Depth
Global Vel Dist= 0 , 0 , 0
Global Log Level= 0
CheckData=True
Encroach Param=-1 ,0,0, 0
Computation Interval=1HOUR
Output Interval=1HOUR
Run HTab= 0
Run UNet= 0
Run PostProcess= 0
UNET Theta= 1
UNET ZTol= 0.02
UNET ZSATol= 0.1
UNET MxIter= 20
UNET MaxInSteps= 20
UNET DtIC= 0
UNET DtMin= 0
UNET MaxCRTS= 20
UNET WFStab= 2
UNET SFStab= 1
UNET WFX= 1
UNET SFX= 1
UNET Convert EG Bridges=-1
UNET Use Existing IB Tables=-1
Instantaneous Interval=1HOUR
Write IC File= 0
Write Velocity= 0
Write Detailed= 0

--- TONG.f01 (steady flow) ---

Flow Title=Imported Flow 01
Version=Version 3.0.1  Mar 2001
Number of Profiles= 5
Profile Names=10YR,20YR,30YR,50YR,80YR
River Rch & RM=RIVER-1,Reach-1         ,868.00
   12.77   14.07   14.82   15.78   16.66
Boundary for River Rch & Prof#=RIVER-1,Reach-1         , 1
Up Type= 0
Dn Type= 3
Dn Slope=.03
Boundary for River Rch & Prof#=RIVER-1,Reach-1         , 2
Up Type= 0
Dn Type= 3
Dn Slope=.03
Boundary for River Rch & Prof#=RIVER-1,Reach-1         , 3
Up Type= 0
Dn Type= 3
Dn Slope=.03
Boundary for River Rch & Prof#=RIVER-1,Reach-1         , 4
Up Type= 0
Dn Type= 3
Dn Slope=.03
Boundary for River Rch & Prof#=RIVER-1,Reach-1         , 5
Up Type= 0
Dn Type= 3
Dn Slope=.03
DSS Import GetInterval= 0
DSS Import GetPeak= 0
DSS Import FillOption= 0

--- TONG.g01 (geometry) ---

Geom Title=Imported Geom 01
Version=Version 3.0.1  Mar 2001

River Reach=RIVER-1         ,Reach-1
Reach XY= 2
              .5             .95              .5             .05

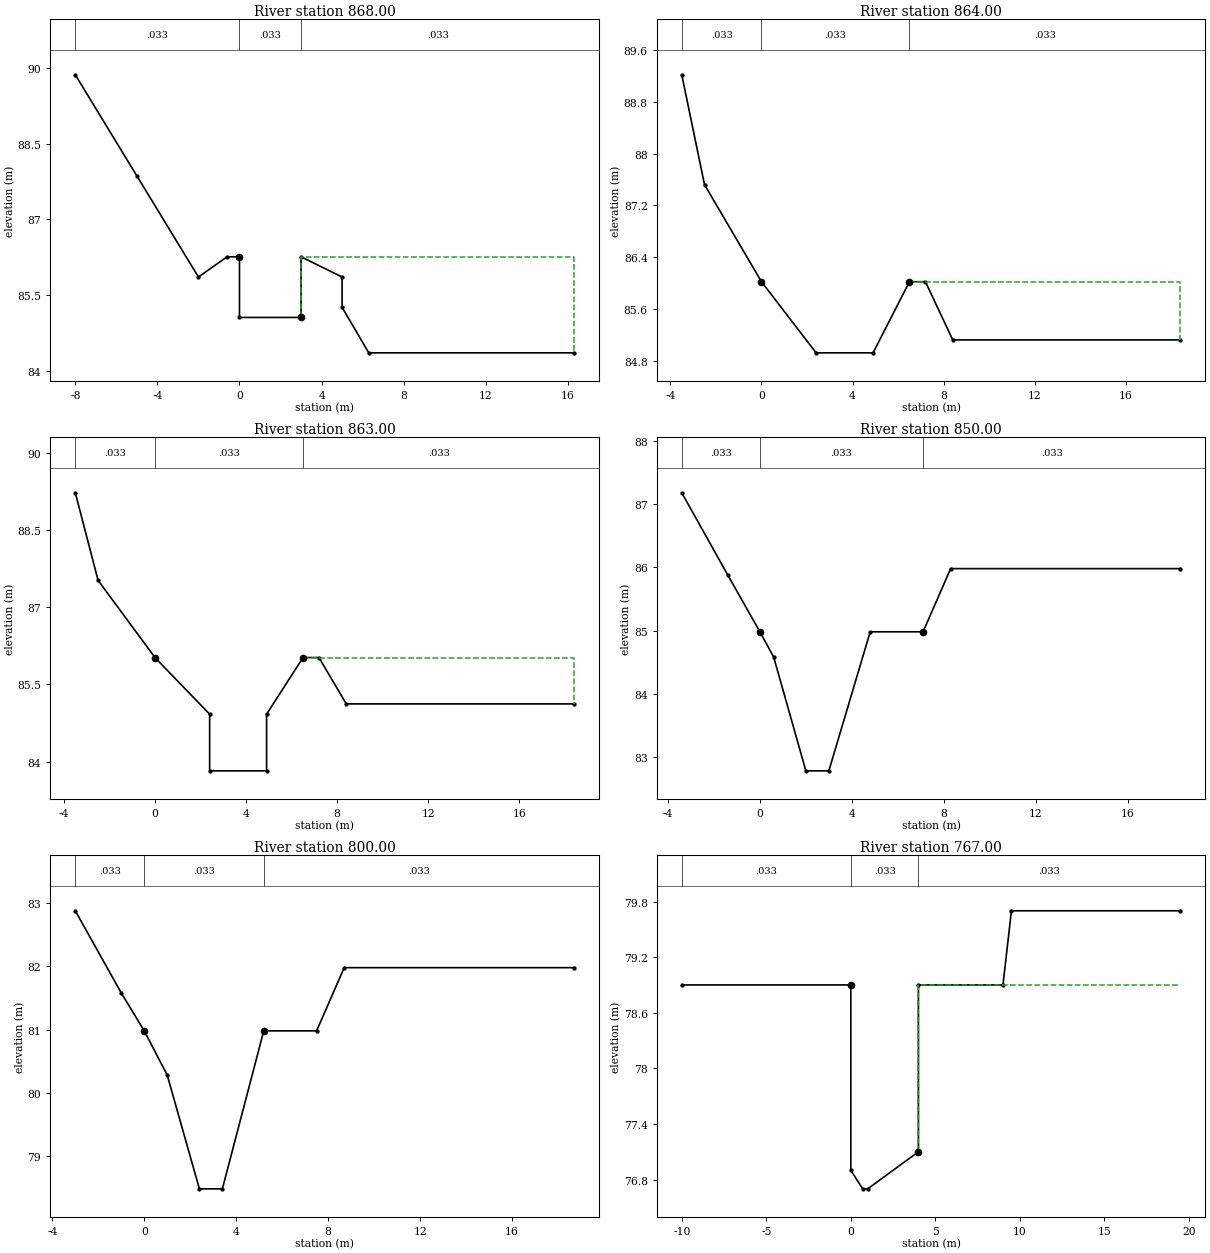
Type RM Length L Ch R = 1 ,868.00  ,4,4,4
BEGIN DESCRIPTION:
17.018
END DESCRIPTION:
#Sta/Elev= 12
      -8   89.86      -5   87.86      -2   85.86     -.6   86.26       0   86.26
       0   85.06       3   85.06       3   86.26       5   85.86       5   85.26
     6.3   84.36    16.3   84.36
#Mann= 3 , 0 , 0
      -8    .033       0       0    .033       0       3    .033       0
#XS Ineff= 2 , 0
               0   86.26       3           86.26
Permanent Ineff=
       F       F
Bank Sta=0,3
XS Rating Curve= 0
Exp/Cntr=.3,.1

Type RM Length L Ch R = 1 ,864.00  ,1,1,1
BEGIN DESCRIPTION:
17.014
END DESCRIPTION:
#Sta/Elev= 9
    -3.5   89.22    -2.5   87.52       0   86.02     2.4   84.92     4.9   84.92
     6.5   86.02     7.2   86.02     8.4   85.12    18.4   85.12
#Mann= 3 , 0 , 0
    -3.5    .033       0       0    .033       0     6.5    .033       0
#XS Ineff= 2 , 0
               0   86.02     6.5           86.02
Permanent Ineff=
       F       F
Bank Sta=0,6.5
XS Rating Curve= 0
Exp/Cntr=.3,.1

Type RM Length L Ch R = 1 ,863.00  ,13,13,13
BEGIN DESCRIPTION:
17.013
END DESCRIPTION:
#Sta/Elev= 11
    -3.5   89.22    -2.5   87.52       0   86.02     2.4   84.92     2.4   83.82
     4.9   83.82     4.9   84.92     6.5   86.02     7.2   86.02     8.4   85.12
    18.4   85.12
#Mann= 3 , 0 , 0
    -3.5    .033       0       0    .033       0     6.5    .033       0
#XS Ineff= 2 , 0
               0   86.02     6.5           86.02
Permanent Ineff=
       F       F
Bank Sta=0,6.5
XS Rating Curve= 0
Exp/Cntr=.3,.1

Type RM Length L Ch R = 1 ,850.00  ,50,50,50
BEGIN DESCRIPTION:
17
END DESCRIPTION:
#Sta/Elev= 10
    -3.4   87.18    -1.4   85.88       0   84.98      .6   84.58       2   82.78
       3   82.78     4.8   84.98     7.1   84.98     8.3   85.98    18.3   85.98
#Mann= 3 , 0 , 0
    -3.4    .033       0       0    .033       0     7.1    .033       0
#XS Ineff= 2 , 0
               0   84.98     7.1           84.98
Permanent Ineff=
       F       F
Bank Sta=0,7.1
XS Rating Curve= 0
Exp/Cntr=.3,.1

Type RM Length L Ch R = 1 ,800.00  ,33,33,33
BEGIN DESCRIPTION:
16
END DESCRIPTION:
#Sta/Elev= 10
      -3   82.88      -1   81.58       0   80.98       1   80.28     2.4   78.48
     3.4   78.48     5.2   80.98     7.5   80.98     8.7   81.98    18.7   81.98
#Mann= 3 , 0 , 0
      -3    .033       0       0    .033       0     5.2    .033       0
#XS Ineff= 2 , 0
               0   80.98     5.2           80.98
Permanent Ineff=
       F       F
Bank Sta=0,5.2
XS Rating Curve= 0
Exp/Cntr=.3,.1

Type RM Length L Ch R = 1 ,767.00  ,17,17,17
BEGIN DESCRIPTION:
15.017
END DESCRIPTION:
#Sta/Elev= 10
     -10    78.9       0    78.9       0    76.9      .7    76.7       1    76.7
       4    77.1       4    78.9       9    78.9     9.5    79.7    19.5    79.7
#Mann= 3 , 0 , 0
     -10    .033       0       0    .033       0       4    .033       0
#XS Ineff= 2 , 0
               0    78.9       4            78.9
Permanent Ineff=
       F       F
Bank Sta=0,4
XS Rating Curve= 0
Exp/Cntr=.3,.1

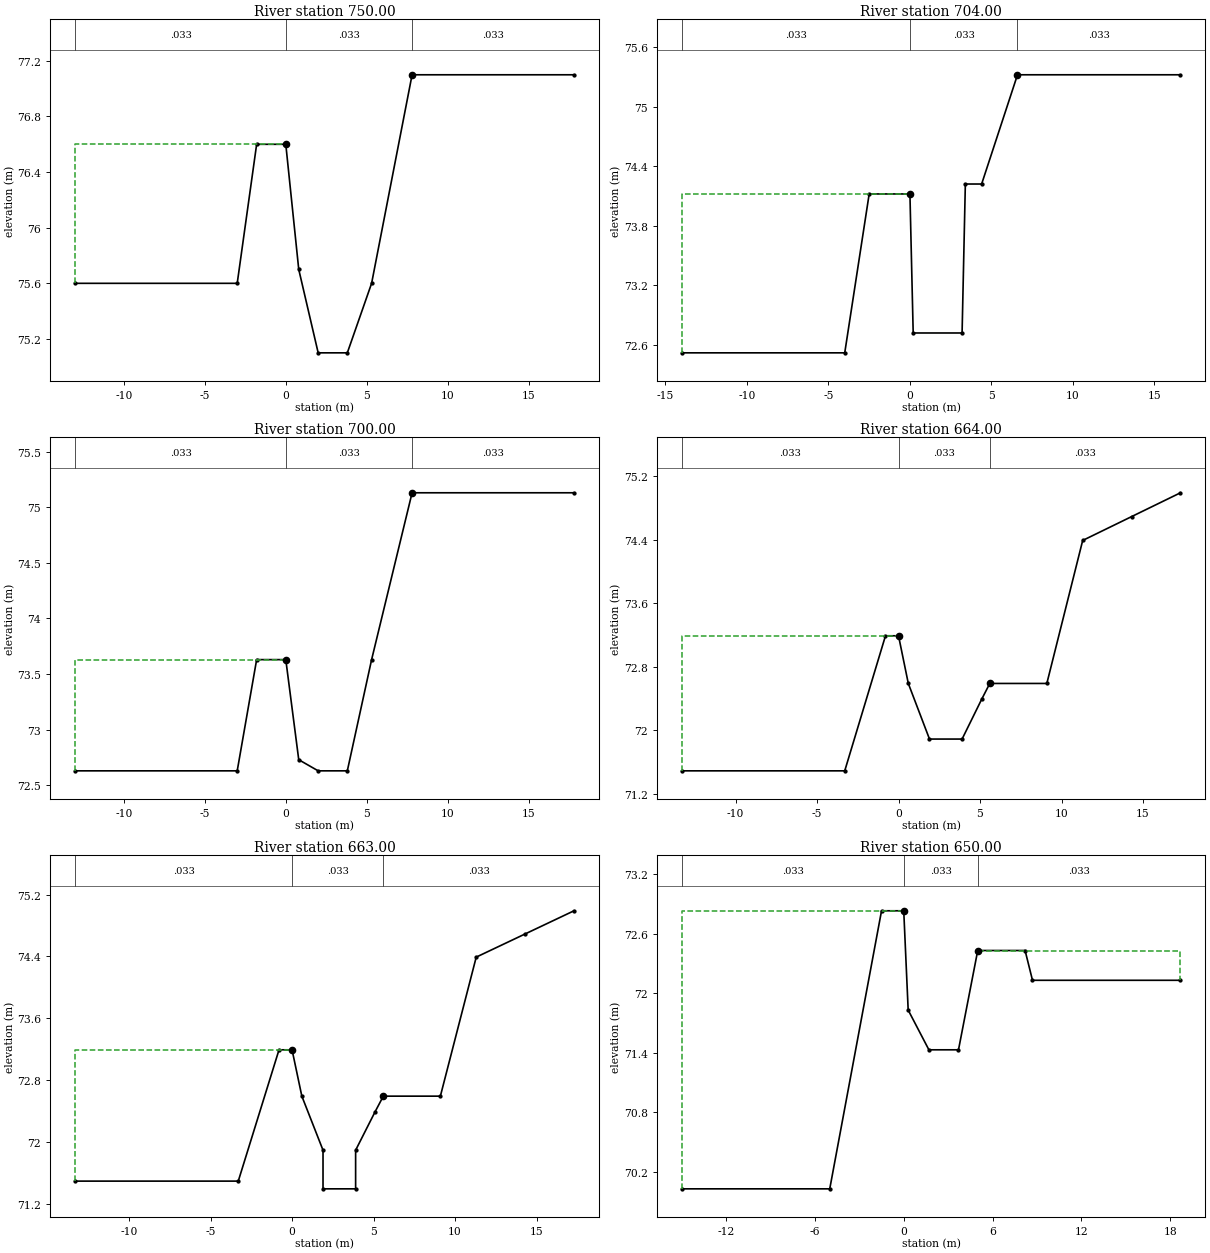
Type RM Length L Ch R = 1 ,750.00  ,46,46,46
BEGIN DESCRIPTION:
15
END DESCRIPTION:
#Sta/Elev= 10
     -13    75.6      -3    75.6    -1.8    76.6       0    76.6      .8    75.7
       2    75.1     3.8    75.1     5.3    75.6     7.8    77.1    17.8    77.1
#Mann= 3 , 0 , 0
     -13    .033       0       0    .033       0     7.8    .033       0
#XS Ineff= 2 , 0
               0    76.6     7.8            77.1
Permanent Ineff=
       F       F
Bank Sta=0,7.8
XS Rating Curve= 0
Exp/Cntr=.3,.1

Type RM Length L Ch R = 1 ,704.00  ,4,4,4
BEGIN DESCRIPTION:
14.004
END DESCRIPTION:
#Sta/Elev= 10
     -14   72.52      -4   72.52    -2.5   74.12       0   74.12      .2   72.72
     3.2   72.72     3.4   74.22     4.4   74.22     6.6   75.32    16.6   75.32
#Mann= 3 , 0 , 0
     -14    .033       0       0    .033       0     6.6    .033       0
#XS Ineff= 2 , 0
               0   74.12     6.6           75.32
Permanent Ineff=
       F       F
Bank Sta=0,6.6
XS Rating Curve= 0
Exp/Cntr=.3,.1

Type RM Length L Ch R = 1 ,700.00  ,36,36,36
BEGIN DESCRIPTION:
14
END DESCRIPTION:
#Sta/Elev= 10
     -13   72.63      -3   72.63    -1.8   73.63       0   73.63      .8   72.73
       2   72.63     3.8   72.63     5.3   73.63     7.8   75.13    17.8   75.13
#Mann= 3 , 0 , 0
     -13    .033       0       0    .033       0     7.8    .033       0
#XS Ineff= 2 , 0
               0   73.63     7.8           75.13
Permanent Ineff=
       F       F
Bank Sta=0,7.8
XS Rating Curve= 0
Exp/Cntr=.3,.1

Type RM Length L Ch R = 1 ,664.00  ,1,1,1
BEGIN DESCRIPTION:
13.014
END DESCRIPTION:
#Sta/Elev= 13
   -13.3   71.49    -3.3   71.49     -.8   73.19       0   73.19      .6   72.59
     1.9   71.89     3.9   71.89     5.1   72.39     5.6   72.59     9.1   72.59
    11.3   74.39    14.3   74.69    17.3   74.99
#Mann= 3 , 0 , 0
   -13.3    .033       0       0    .033       0     5.6    .033       0
#XS Ineff= 2 , 0
               0   73.19     5.6           72.59
Permanent Ineff=
       F       F
Bank Sta=0,5.6
XS Rating Curve= 0
Exp/Cntr=.3,.1

Type RM Length L Ch R = 1 ,663.00  ,13,13,13
BEGIN DESCRIPTION:
13.013
END DESCRIPTION:
#Sta/Elev= 15
   -13.3   71.49    -3.3   71.49     -.8   73.19       0   73.19      .6   72.59
     1.9   71.89     1.9   71.39     3.9   71.39     3.9   71.89     5.1   72.39
     5.6   72.59     9.1   72.59    11.3   74.39    14.3   74.69    17.3   74.99
#Mann= 3 , 0 , 0
   -13.3    .033       0       0    .033       0     5.6    .033       0
#XS Ineff= 2 , 0
               0   73.19     5.6           72.59
Permanent Ineff=
       F       F
Bank Sta=0,5.6
XS Rating Curve= 0
Exp/Cntr=.3,.1

Type RM Length L Ch R = 1 ,650.00  ,19,19,19
BEGIN DESCRIPTION:
13
END DESCRIPTION:
#Sta/Elev= 11
     -15   70.03      -5   70.03    -1.5   72.83       0   72.83      .3   71.83
     1.7   71.43     3.7   71.43       5   72.43     8.2   72.43     8.7   72.13
    18.7   72.13
#Mann= 3 , 0 , 0
     -15    .033       0       0    .033       0       5    .033       0
#XS Ineff= 2 , 0
               0   72.83       5           72.43
Permanent Ineff=
       F       F
Bank Sta=0,5
XS Rating Curve= 0
Exp/Cntr=.3,.1

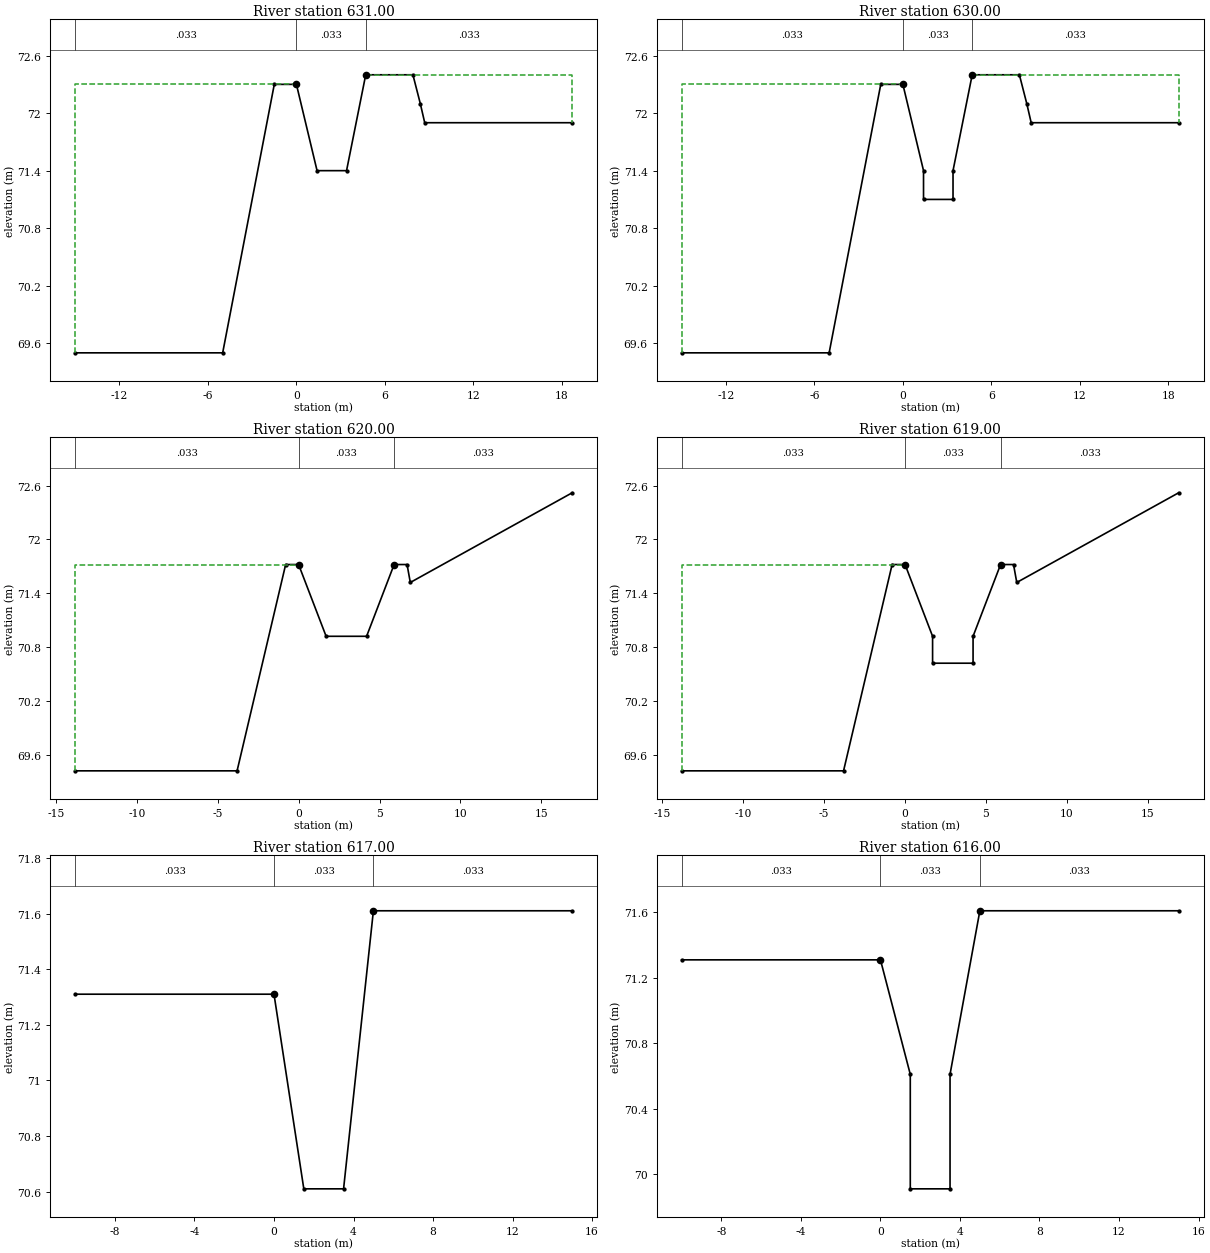
Type RM Length L Ch R = 1 ,631.00  ,1,1,1
BEGIN DESCRIPTION:
12.031
END DESCRIPTION:
#Sta/Elev= 11
     -15    69.5      -5    69.5    -1.5    72.3       0    72.3     1.4    71.4
     3.4    71.4     4.7    72.4     7.9    72.4     8.4    72.1     8.7    71.9
    18.7    71.9
#Mann= 3 , 0 , 0
     -15    .033       0       0    .033       0     4.7    .033       0
#XS Ineff= 2 , 0
               0    72.3     4.7            72.4
Permanent Ineff=
       F       F
Bank Sta=0,4.7
XS Rating Curve= 0
Exp/Cntr=.3,.1

Type RM Length L Ch R = 1 ,630.00  ,10,10,10
BEGIN DESCRIPTION:
12.03
END DESCRIPTION:
#Sta/Elev= 13
     -15    69.5      -5    69.5    -1.5    72.3       0    72.3     1.4    71.4
     1.4    71.1     3.4    71.1     3.4    71.4     4.7    72.4     7.9    72.4
     8.4    72.1     8.7    71.9    18.7    71.9
#Mann= 3 , 0 , 0
     -15    .033       0       0    .033       0     4.7    .033       0
#XS Ineff= 2 , 0
               0    72.3     4.7            72.4
Permanent Ineff=
       F       F
Bank Sta=0,4.7
XS Rating Curve= 0
Exp/Cntr=.3,.1

Type RM Length L Ch R = 1 ,620.00  ,1,1,1
BEGIN DESCRIPTION:
12.02
END DESCRIPTION:
#Sta/Elev= 10
   -13.8   69.42    -3.8   69.42     -.8   71.72       0   71.72     1.7   70.92
     4.2   70.92     5.9   71.72     6.7   71.72     6.9   71.52    16.9   72.52
#Mann= 3 , 0 , 0
   -13.8    .033       0       0    .033       0     5.9    .033       0
#XS Ineff= 2 , 0
               0   71.72     5.9           71.72
Permanent Ineff=
       F       F
Bank Sta=0,5.9
XS Rating Curve= 0
Exp/Cntr=.3,.1

Type RM Length L Ch R = 1 ,619.00  ,2,2,2
BEGIN DESCRIPTION:
12.019
END DESCRIPTION:
#Sta/Elev= 12
   -13.8   69.42    -3.8   69.42     -.8   71.72       0   71.72     1.7   70.92
     1.7   70.62     4.2   70.62     4.2   70.92     5.9   71.72     6.7   71.72
     6.9   71.52    16.9   72.52
#Mann= 3 , 0 , 0
   -13.8    .033       0       0    .033       0     5.9    .033       0
#XS Ineff= 2 , 0
               0   71.72     5.9           71.72
Permanent Ineff=
       F       F
Bank Sta=0,5.9
XS Rating Curve= 0
Exp/Cntr=.3,.1

Type RM Length L Ch R = 1 ,617.00  ,1,1,1
BEGIN DESCRIPTION:
12.017
END DESCRIPTION:
#Sta/Elev= 6
     -10   71.31       0   71.31     1.5   70.61     3.5   70.61       5   71.61
      15   71.61
#Mann= 3 , 0 , 0
     -10    .033       0       0    .033       0       5    .033       0
#XS Ineff= 2 , 0
               0   71.31       5           71.61
Permanent Ineff=
       F       F
Bank Sta=0,5
XS Rating Curve= 0
Exp/Cntr=.3,.1

Type RM Length L Ch R = 1 ,616.00  ,3,3,3
BEGIN DESCRIPTION:
12.016
END DESCRIPTION:
#Sta/Elev= 8
     -10   71.31       0   71.31     1.5   70.61     1.5   69.91     3.5   69.91
     3.5   70.61       5   71.61      15   71.61
#Mann= 3 , 0 , 0
     -10    .033       0       0    .033       0       5    .033       0
#XS Ineff= 2 , 0
               0   71.31       5           71.61
Permanent Ineff=
       F       F
Bank Sta=0,5
XS Rating Curve= 0
Exp/Cntr=.3,.1

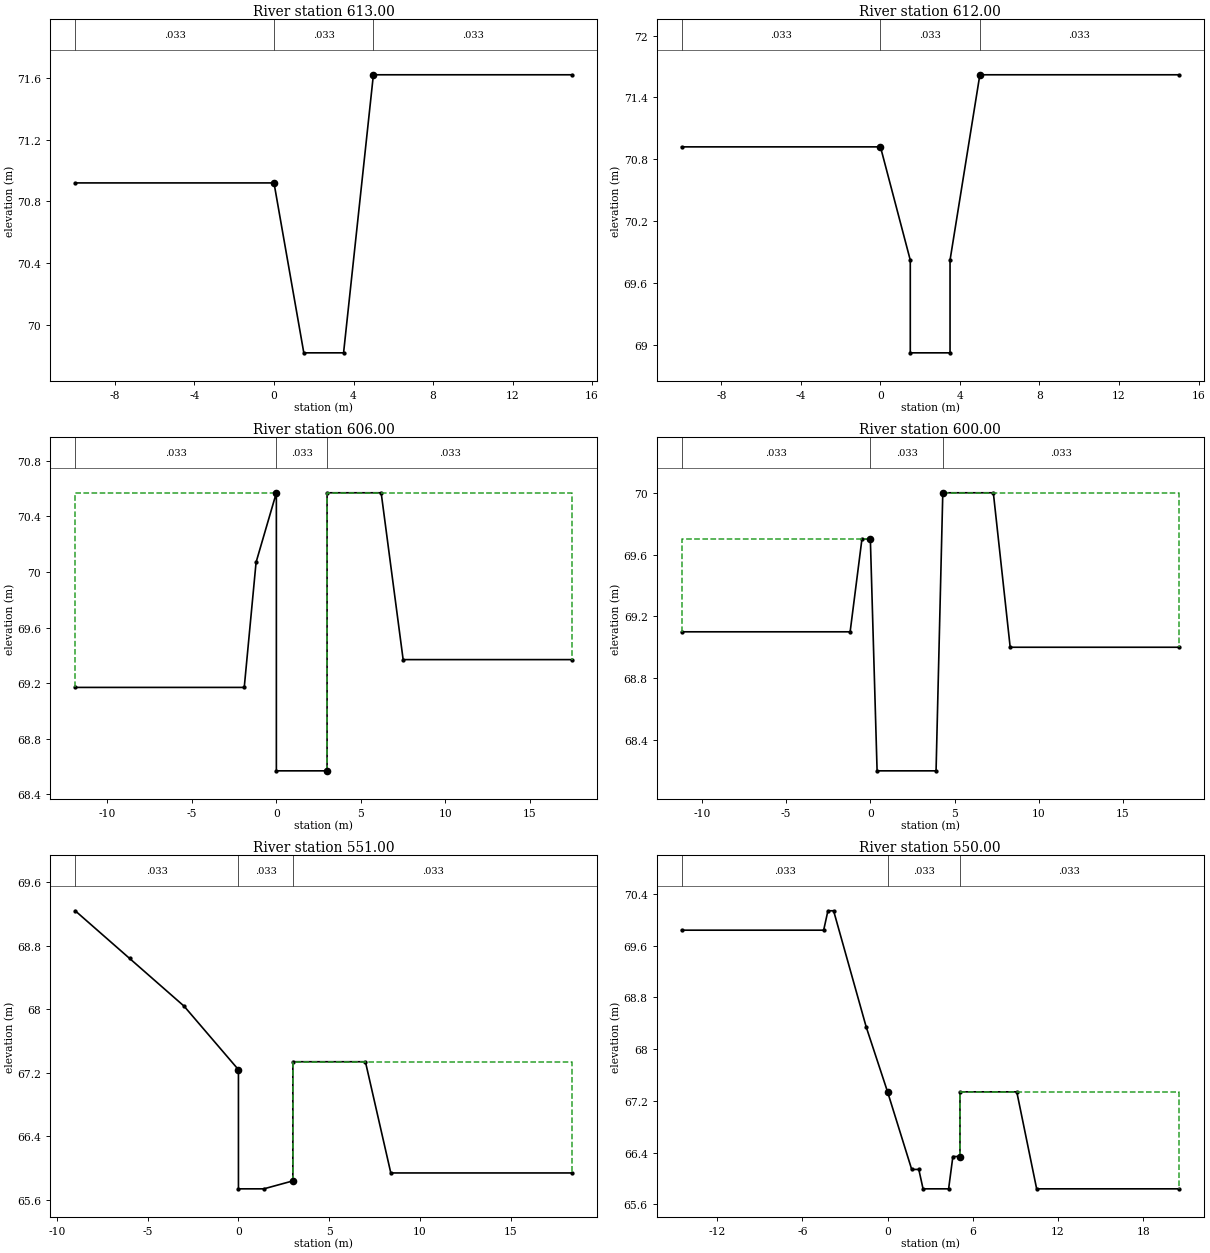
Type RM Length L Ch R = 1 ,613.00  ,1,1,1
BEGIN DESCRIPTION:
12.013
END DESCRIPTION:
#Sta/Elev= 6
     -10   70.92       0   70.92     1.5   69.82     3.5   69.82       5   71.62
      15   71.62
#Mann= 3 , 0 , 0
     -10    .033       0       0    .033       0       5    .033       0
#XS Ineff= 2 , 0
               0   70.92       5           71.62
Permanent Ineff=
       F       F
Bank Sta=0,5
XS Rating Curve= 0
Exp/Cntr=.3,.1

Type RM Length L Ch R = 1 ,612.00  ,6,6,6
BEGIN DESCRIPTION:
12.012
END DESCRIPTION:
#Sta/Elev= 8
     -10   70.92       0   70.92     1.5   69.82     1.5   68.92     3.5   68.92
     3.5   69.82       5   71.62      15   71.62
#Mann= 3 , 0 , 0
     -10    .033       0       0    .033       0       5    .033       0
#XS Ineff= 2 , 0
               0   70.92       5           71.62
Permanent Ineff=
       F       F
Bank Sta=0,5
XS Rating Curve= 0
Exp/Cntr=.3,.1

Type RM Length L Ch R = 1 ,606.00  ,6,6,6
BEGIN DESCRIPTION:
12.006
END DESCRIPTION:
#Sta/Elev= 10
   -11.9   69.17    -1.9   69.17    -1.2   70.07       0   70.57       0   68.57
       3   68.57       3   70.57     6.2   70.57     7.5   69.37    17.5   69.37
#Mann= 3 , 0 , 0
   -11.9    .033       0       0    .033       0       3    .033       0
#XS Ineff= 2 , 0
               0   70.57       3           70.57
Permanent Ineff=
       F       F
Bank Sta=0,3
XS Rating Curve= 0
Exp/Cntr=.3,.1

Type RM Length L Ch R = 1 ,600.00  ,49,49,49
BEGIN DESCRIPTION:
12
END DESCRIPTION:
#Sta/Elev= 10
   -11.2    69.1    -1.2    69.1     -.5    69.7       0    69.7      .4    68.2
     3.9    68.2     4.3      70     7.3      70     8.3      69    18.3      69
#Mann= 3 , 0 , 0
   -11.2    .033       0       0    .033       0     4.3    .033       0
#XS Ineff= 2 , 0
               0    69.7     4.3              70
Permanent Ineff=
       F       F
Bank Sta=0,4.3
XS Rating Curve= 0
Exp/Cntr=.3,.1

Type RM Length L Ch R = 1 ,551.00  ,1,1,1
BEGIN DESCRIPTION:
11.001
END DESCRIPTION:
#Sta/Elev= 11
      -9   69.24      -6   68.64      -3   68.04       0   67.24       0   65.74
     1.4   65.74       3   65.84       3   67.34       7   67.34     8.4   65.94
    18.4   65.94
#Mann= 3 , 0 , 0
      -9    .033       0       0    .033       0       3    .033       0
#XS Ineff= 2 , 0
               0   67.24       3           67.34
Permanent Ineff=
       F       F
Bank Sta=0,3
XS Rating Curve= 0
Exp/Cntr=.3,.1

Type RM Length L Ch R = 1 ,550.00  ,50,50,50
BEGIN DESCRIPTION:
11
END DESCRIPTION:
#Sta/Elev= 16
   -14.5   69.84    -4.5   69.84    -4.2   70.14    -3.8   70.14    -1.5   68.34
       0   67.34     1.7   66.14     2.2   66.14     2.5   65.84     4.3   65.84
     4.6   66.34     5.1   66.34     5.1   67.34     9.1   67.34    10.5   65.84
    20.5   65.84
#Mann= 3 , 0 , 0
   -14.5    .033       0       0    .033       0     5.1    .033       0
#XS Ineff= 2 , 0
               0   67.34     5.1           67.34
Permanent Ineff=
       F       F
Bank Sta=0,5.1
XS Rating Curve= 0
Exp/Cntr=.3,.1

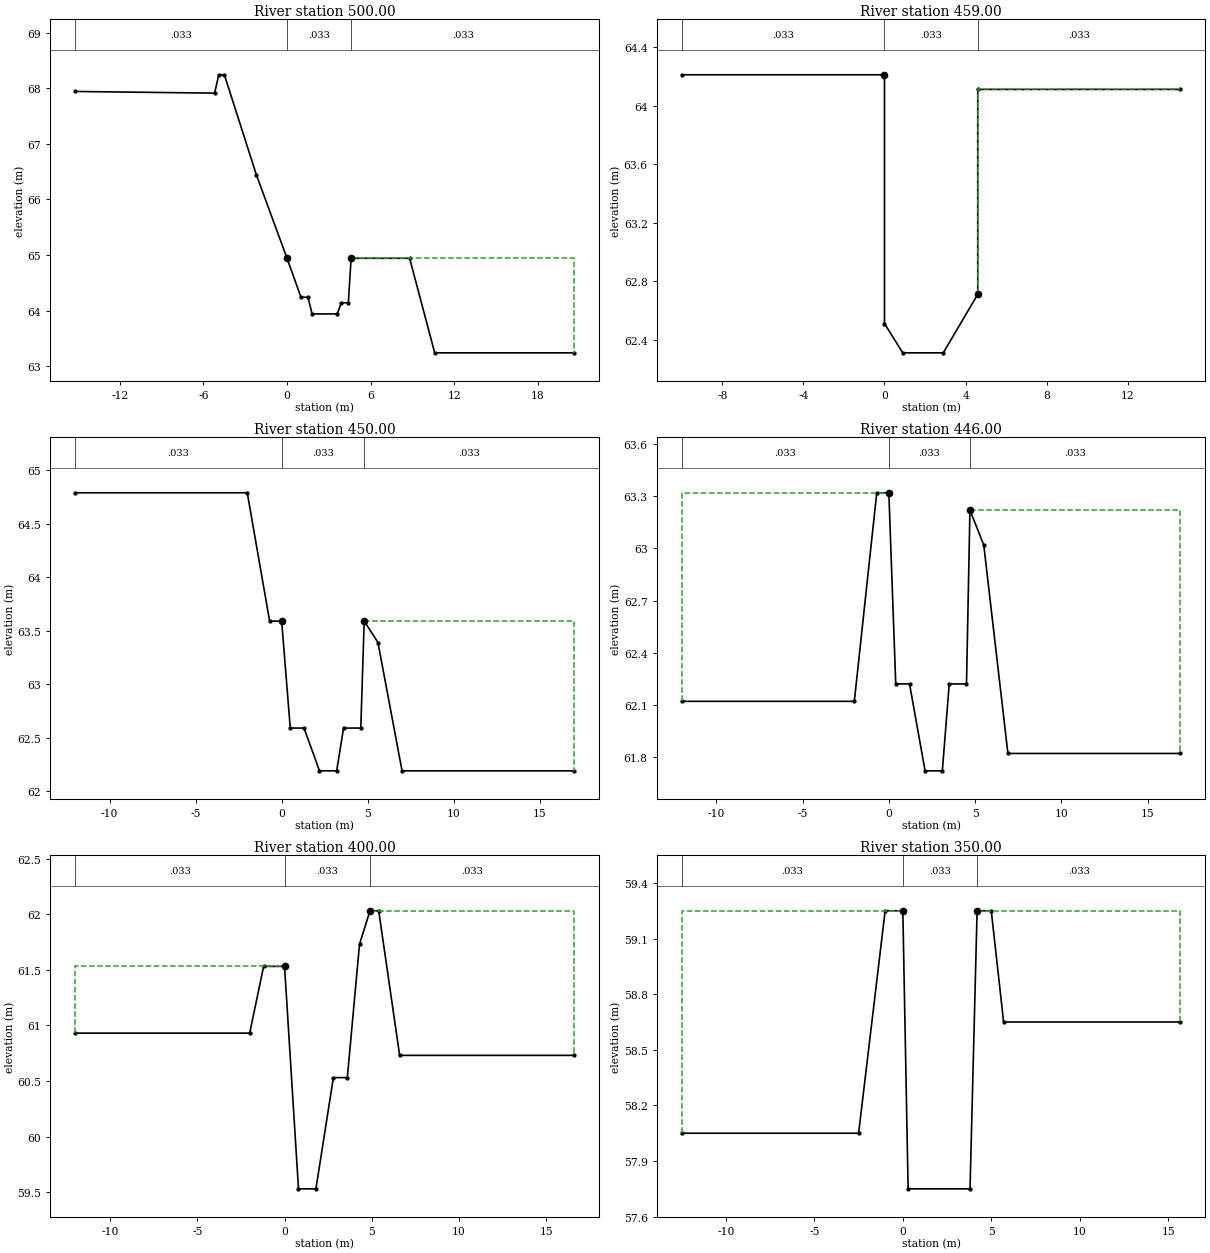
Type RM Length L Ch R = 1 ,500.00  ,41,41,41
BEGIN DESCRIPTION:
10
END DESCRIPTION:
#Sta/Elev= 16
   -15.2   67.94    -5.2   67.91    -4.9   68.24    -4.5   68.24    -2.2   66.44
       0   64.94       1   64.24     1.5   64.24     1.8   63.94     3.6   63.94
     3.9   64.14     4.4   64.14     4.6   64.94     8.8   64.94    10.6   63.24
    20.6   63.24
#Mann= 3 , 0 , 0
   -15.2    .033       0       0    .033       0     4.6    .033       0
#XS Ineff= 2 , 0
               0   64.94     4.6           64.94
Permanent Ineff=
       F       F
Bank Sta=0,4.6
XS Rating Curve= 0
Exp/Cntr=.3,.1

Type RM Length L Ch R = 1 ,459.00  ,9,9,9
BEGIN DESCRIPTION:
9.009
END DESCRIPTION:
#Sta/Elev= 8
     -10   64.21       0   64.21       0   62.51      .9   62.31     2.9   62.31
     4.6   62.71     4.6   64.11    14.6   64.11
#Mann= 3 , 0 , 0
     -10    .033       0       0    .033       0     4.6    .033       0
#XS Ineff= 2 , 0
               0   64.21     4.6           64.11
Permanent Ineff=
       F       F
Bank Sta=0,4.6
XS Rating Curve= 0
Exp/Cntr=.3,.1

Type RM Length L Ch R = 1 ,450.00  ,4,4,4
BEGIN DESCRIPTION:
9
END DESCRIPTION:
#Sta/Elev= 14
     -12   64.79      -2   64.79     -.7   63.59       0   63.59      .5   62.59
     1.3   62.59     2.2   62.19     3.2   62.19     3.6   62.59     4.6   62.59
     4.8   63.59     5.6   63.39       7   62.19      17   62.19
#Mann= 3 , 0 , 0
     -12    .033       0       0    .033       0     4.8    .033       0
#XS Ineff= 2 , 0
               0   63.59     4.8           63.59
Permanent Ineff=
       F       F
Bank Sta=0,4.8
XS Rating Curve= 0
Exp/Cntr=.3,.1

Type RM Length L Ch R = 1 ,446.00  ,46,46,46
BEGIN DESCRIPTION:
8.046
END DESCRIPTION:
#Sta/Elev= 14
     -12   62.12      -2   62.12     -.7   63.32       0   63.32      .4   62.22
     1.2   62.22     2.1   61.72     3.1   61.72     3.5   62.22     4.5   62.22
     4.7   63.22     5.5   63.02     6.9   61.82    16.9   61.82
#Mann= 3 , 0 , 0
     -12    .033       0       0    .033       0     4.7    .033       0
#XS Ineff= 2 , 0
               0   63.32     4.7           63.22
Permanent Ineff=
       F       F
Bank Sta=0,4.7
XS Rating Curve= 0
Exp/Cntr=.3,.1

Type RM Length L Ch R = 1 ,400.00  ,50,50,50
BEGIN DESCRIPTION:
8
END DESCRIPTION:
#Sta/Elev= 13
     -12   60.93      -2   60.93    -1.2   61.53       0   61.53      .8   59.53
     1.8   59.53     2.8   60.53     3.6   60.53     4.3   61.73     4.9   62.03
     5.4   62.03     6.6   60.73    16.6   60.73
#Mann= 3 , 0 , 0
     -12    .033       0       0    .033       0     4.9    .033       0
#XS Ineff= 2 , 0
               0   61.53     4.9           62.03
Permanent Ineff=
       F       F
Bank Sta=0,4.9
XS Rating Curve= 0
Exp/Cntr=.3,.1

Type RM Length L Ch R = 1 ,350.00  ,30,30,30
BEGIN DESCRIPTION:
7
END DESCRIPTION:
#Sta/Elev= 10
   -12.5   58.05    -2.5   58.05      -1   59.25       0   59.25      .3   57.75
     3.8   57.75     4.2   59.25       5   59.25     5.7   58.65    15.7   58.65
#Mann= 3 , 0 , 0
   -12.5    .033       0       0    .033       0     4.2    .033       0
#XS Ineff= 2 , 0
               0   59.25     4.2           59.25
Permanent Ineff=
       F       F
Bank Sta=0,4.2
XS Rating Curve= 0
Exp/Cntr=.3,.1

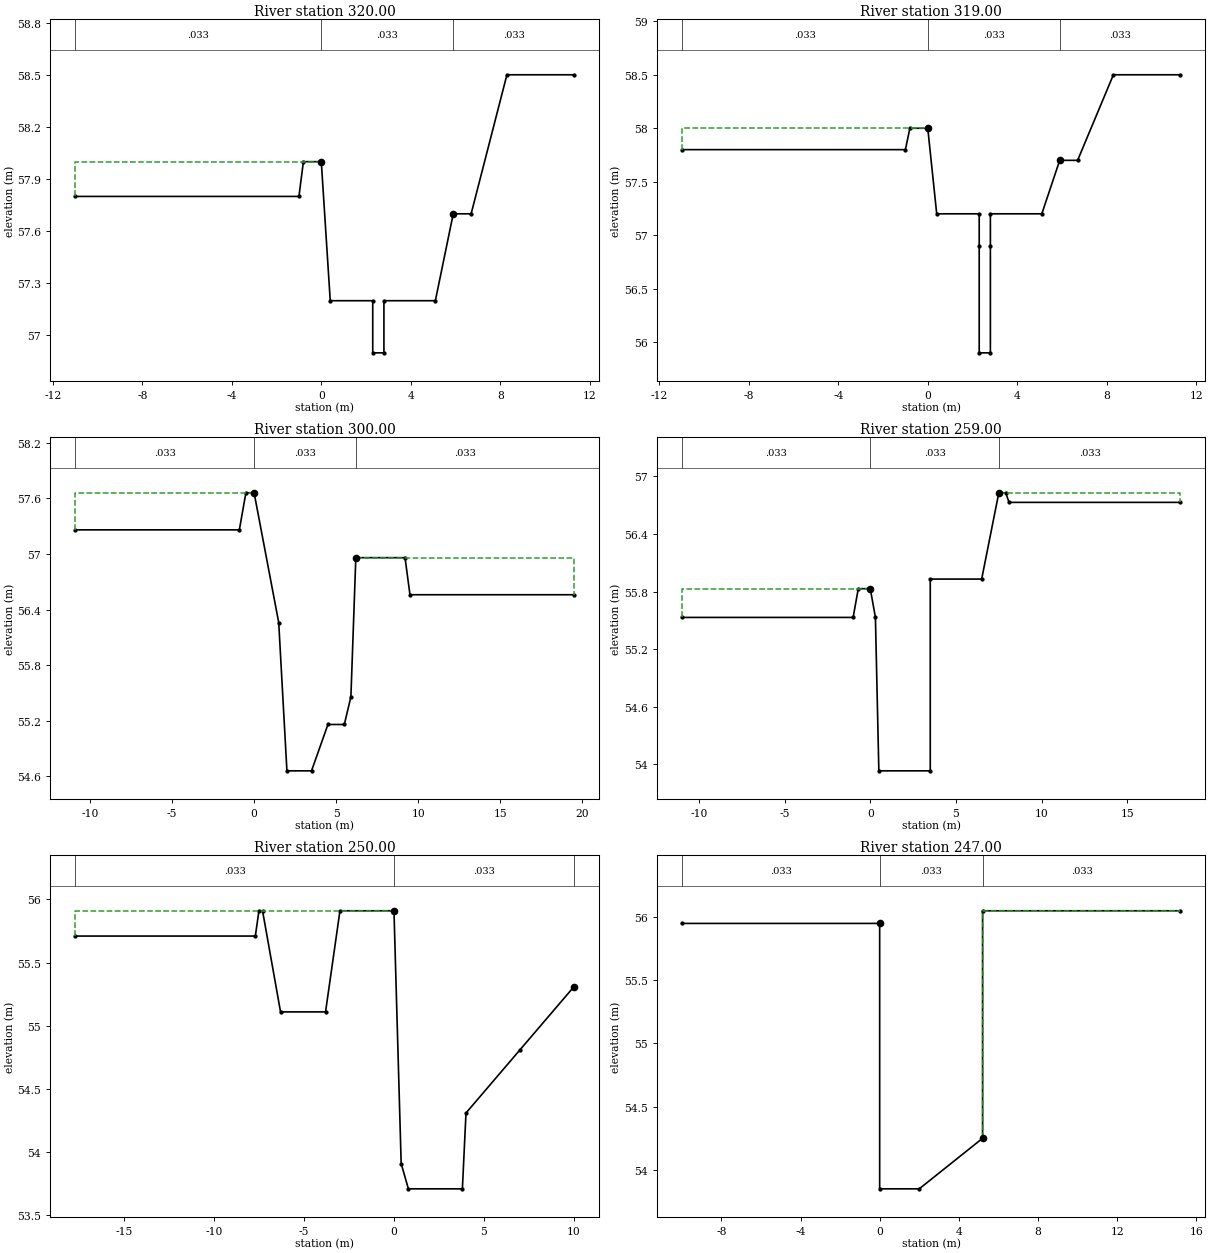
Type RM Length L Ch R = 1 ,320.00  ,1,1,1
BEGIN DESCRIPTION:
6.02
END DESCRIPTION:
#Sta/Elev= 14
     -11    57.8      -1    57.8     -.8      58       0      58      .4    57.2
     2.3    57.2     2.3    56.9     2.8    56.9     2.8    57.2     5.1    57.2
     5.9    57.7     6.7    57.7     8.3    58.5    11.3    58.5
#Mann= 3 , 0 , 0
     -11    .033       0       0    .033       0     5.9    .033       0
#XS Ineff= 2 , 0
               0      58     5.9            57.7
Permanent Ineff=
       F       F
Bank Sta=0,5.9
XS Rating Curve= 0
Exp/Cntr=.3,.1

Type RM Length L Ch R = 1 ,319.00  ,19,19,19
BEGIN DESCRIPTION:
6.019
END DESCRIPTION:
#Sta/Elev= 16
     -11    57.8      -1    57.8     -.8      58       0      58      .4    57.2
     2.3    57.2     2.3    56.9     2.3    55.9     2.8    55.9     2.8    56.9
     2.8    57.2     5.1    57.2     5.9    57.7     6.7    57.7     8.3    58.5
    11.3    58.5
#Mann= 3 , 0 , 0
     -11    .033       0       0    .033       0     5.9    .033       0
#XS Ineff= 2 , 0
               0      58     5.9            57.7
Permanent Ineff=
       F       F
Bank Sta=0,5.9
XS Rating Curve= 0
Exp/Cntr=.3,.1

Type RM Length L Ch R = 1 ,300.00  ,41,41,41
BEGIN DESCRIPTION:
6
END DESCRIPTION:
#Sta/Elev= 14
   -10.9   57.26     -.9   57.26     -.5   57.66       0   57.66     1.5   56.26
       2   54.66     3.5   54.66     4.5   55.16     5.5   55.16     5.9   55.46
     6.2   56.96     9.2   56.96     9.5   56.56    19.5   56.56
#Mann= 3 , 0 , 0
   -10.9    .033       0       0    .033       0     6.2    .033       0
#XS Ineff= 2 , 0
               0   57.66     6.2           56.96
Permanent Ineff=
       F       F
Bank Sta=0,6.2
XS Rating Curve= 0
Exp/Cntr=.3,.1

Type RM Length L Ch R = 1 ,259.00  ,9,9,9
BEGIN DESCRIPTION:
5.009
END DESCRIPTION:
#Sta/Elev= 13
     -11   55.53      -1   55.53     -.7   55.83       0   55.83      .3   55.53
      .5   53.93     3.5   53.93     3.5   55.93     6.5   55.93     7.5   56.83
     7.9   56.83     8.1   56.73    18.1   56.73
#Mann= 3 , 0 , 0
     -11    .033       0       0    .033       0     7.5    .033       0
#XS Ineff= 2 , 0
               0   55.83     7.5           56.83
Permanent Ineff=
       F       F
Bank Sta=0,7.5
XS Rating Curve= 0
Exp/Cntr=.3,.1

Type RM Length L Ch R = 1 ,250.00  ,3,3,3
BEGIN DESCRIPTION:
5
END DESCRIPTION:
#Sta/Elev= 14
   -17.7   55.71    -7.7   55.71    -7.5   55.91    -7.3   55.91    -6.3   55.11
    -3.8   55.11      -3   55.91       0   55.91      .4   53.91      .8   53.71
     3.8   53.71       4   54.31       7   54.81      10   55.31
#Mann= 3 , 0 , 0
   -17.7    .033       0       0    .033       0      10    .033       0
#XS Ineff= 2 , 0
               0   55.91      10           55.31
Permanent Ineff=
       F       F
Bank Sta=0,10
XS Rating Curve= 0
Exp/Cntr=.3,.1

Type RM Length L Ch R = 1 ,247.00  ,26,26,26
BEGIN DESCRIPTION:
4.047
END DESCRIPTION:
#Sta/Elev= 7
     -10   55.95       0   55.95       0   53.85       2   53.85     5.2   54.25
     5.2   56.05    15.2   56.05
#Mann= 3 , 0 , 0
     -10    .033       0       0    .033       0     5.2    .033       0
#XS Ineff= 2 , 0
               0   55.95     5.2           56.05
Permanent Ineff=
       F       F
Bank Sta=0,5.2
XS Rating Curve= 0
Exp/Cntr=.3,.1

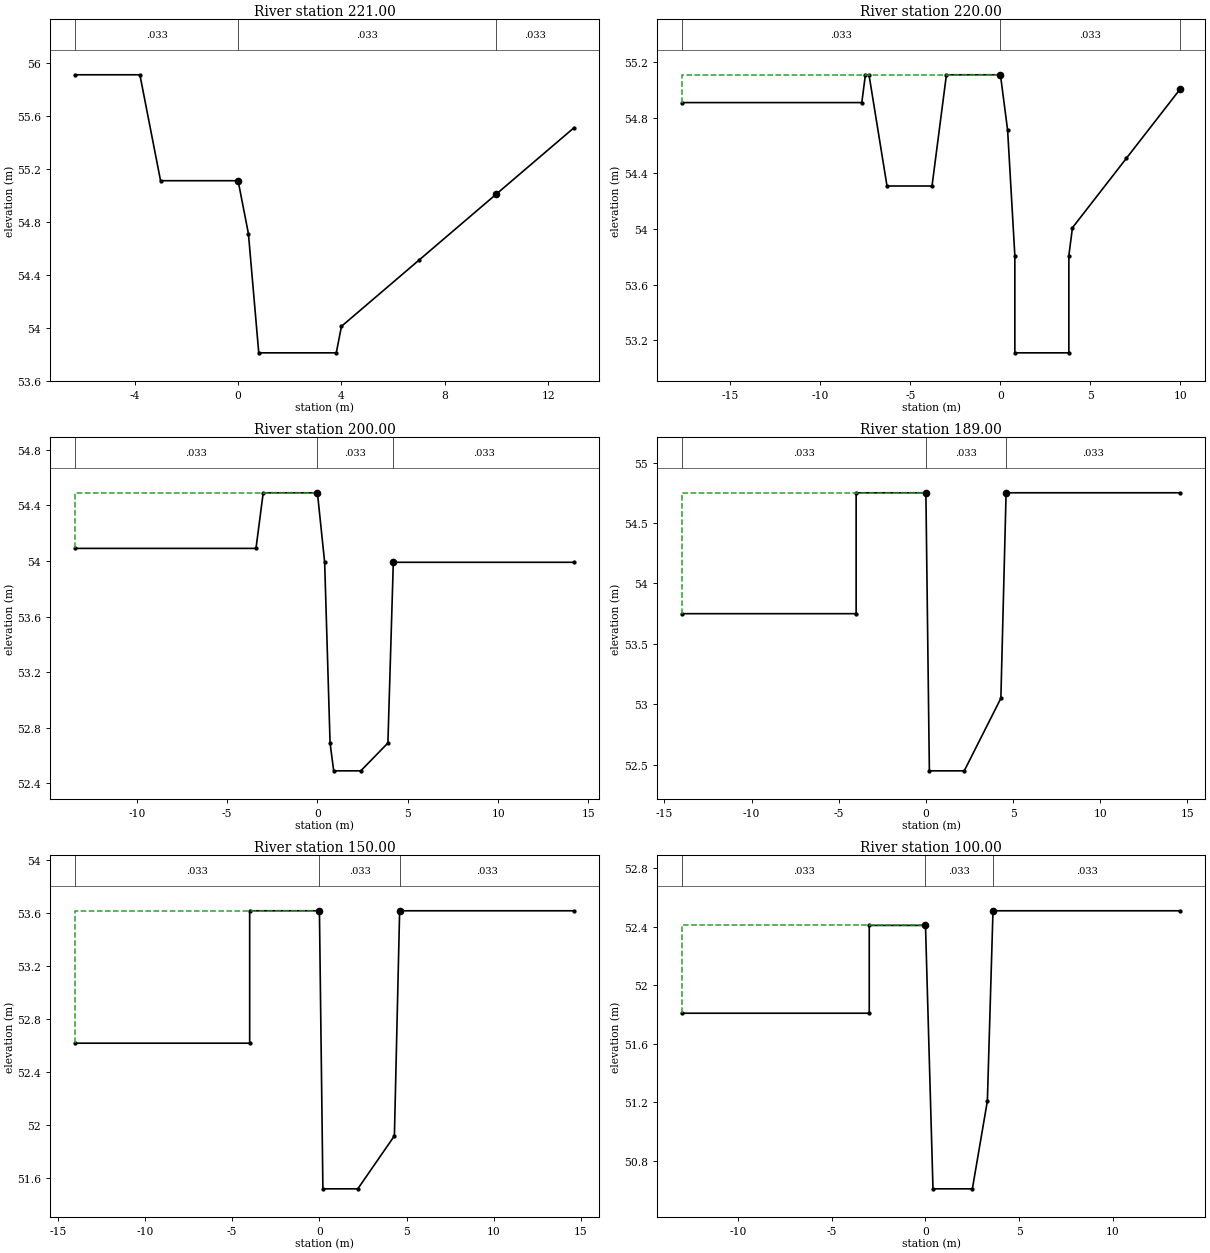
Type RM Length L Ch R = 1 ,221.00  ,1,1,1
BEGIN DESCRIPTION:
4.021
END DESCRIPTION:
#Sta/Elev= 11
    -6.3   55.91    -3.8   55.91      -3   55.11       0   55.11      .4   54.71
      .8   53.81     3.8   53.81       4   54.01       7   54.51      10   55.01
      13   55.51
#Mann= 3 , 0 , 0
    -6.3    .033       0       0    .033       0      10    .033       0
#XS Ineff= 2 , 0
               0   55.11      10           55.01
Permanent Ineff=
       F       F
Bank Sta=0,10
XS Rating Curve= 0
Exp/Cntr=.3,.1

Type RM Length L Ch R = 1 ,220.00  ,20,20,20
BEGIN DESCRIPTION:
4.02
END DESCRIPTION:
#Sta/Elev= 16
   -17.7   54.91    -7.7   54.91    -7.5   55.11    -7.3   55.11    -6.3   54.31
    -3.8   54.31      -3   55.11       0   55.11      .4   54.71      .8   53.81
      .8   53.11     3.8   53.11     3.8   53.81       4   54.01       7   54.51
      10   55.01
#Mann= 3 , 0 , 0
   -17.7    .033       0       0    .033       0      10    .033       0
#XS Ineff= 2 , 0
               0   55.11      10           55.01
Permanent Ineff=
       F       F
Bank Sta=0,10
XS Rating Curve= 0
Exp/Cntr=.3,.1

Type RM Length L Ch R = 1 ,200.00  ,11,11,11
BEGIN DESCRIPTION:
4
END DESCRIPTION:
#Sta/Elev= 11
   -13.4   54.09    -3.4   54.09      -3   54.49       0   54.49      .4   53.99
      .7   52.69      .9   52.49     2.4   52.49     3.9   52.69     4.2   53.99
    14.2   53.99
#Mann= 3 , 0 , 0
   -13.4    .033       0       0    .033       0     4.2    .033       0
#XS Ineff= 2 , 0
               0   54.49     4.2           53.99
Permanent Ineff=
       F       F
Bank Sta=0,4.2
XS Rating Curve= 0
Exp/Cntr=.3,.1

Type RM Length L Ch R = 1 ,189.00  ,39,39,39
BEGIN DESCRIPTION:
3.039
END DESCRIPTION:
#Sta/Elev= 9
     -14   53.75      -4   53.75      -4   54.75       0   54.75      .2   52.45
     2.2   52.45     4.3   53.05     4.6   54.75    14.6   54.75
#Mann= 3 , 0 , 0
     -14    .033       0       0    .033       0     4.6    .033       0
#XS Ineff= 2 , 0
               0   54.75     4.6           54.75
Permanent Ineff=
       F       F
Bank Sta=0,4.6
XS Rating Curve= 0
Exp/Cntr=.3,.1

Type RM Length L Ch R = 1 ,150.00  ,50,50,50
BEGIN DESCRIPTION:
3
END DESCRIPTION:
#Sta/Elev= 9
     -14   52.62      -4   52.62      -4   53.62       0   53.62      .2   51.52
     2.2   51.52     4.3   51.92     4.6   53.62    14.6   53.62
#Mann= 3 , 0 , 0
     -14    .033       0       0    .033       0     4.6    .033       0
#XS Ineff= 2 , 0
               0   53.62     4.6           53.62
Permanent Ineff=
       F       F
Bank Sta=0,4.6
XS Rating Curve= 0
Exp/Cntr=.3,.1

Type RM Length L Ch R = 1 ,100.00  ,43,43,43
BEGIN DESCRIPTION:
2
END DESCRIPTION:
#Sta/Elev= 9
     -13   51.81      -3   51.81      -3   52.41       0   52.41      .4   50.61
     2.5   50.61     3.3   51.21     3.6   52.51    13.6   52.51
#Mann= 3 , 0 , 0
     -13    .033       0       0    .033       0     3.6    .033       0
#XS Ineff= 2 , 0
               0   52.41     3.6           52.51
Permanent Ineff=
       F       F
Bank Sta=0,3.6
XS Rating Curve= 0
Exp/Cntr=.3,.1