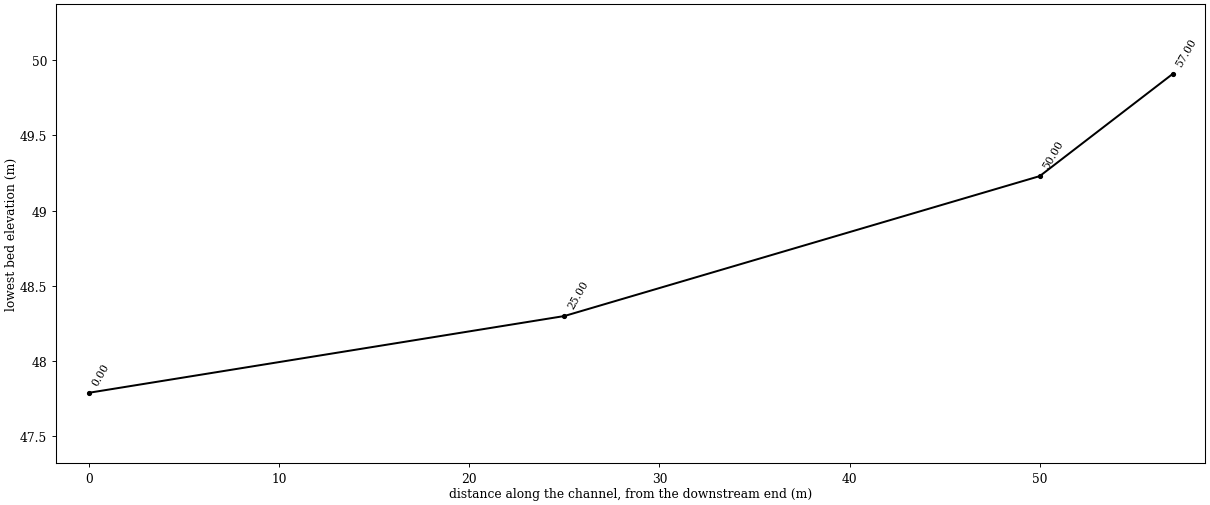
HEC-RAS study TONG.prj: TONG

--- TONG.g01 (geometry) --- (continued)

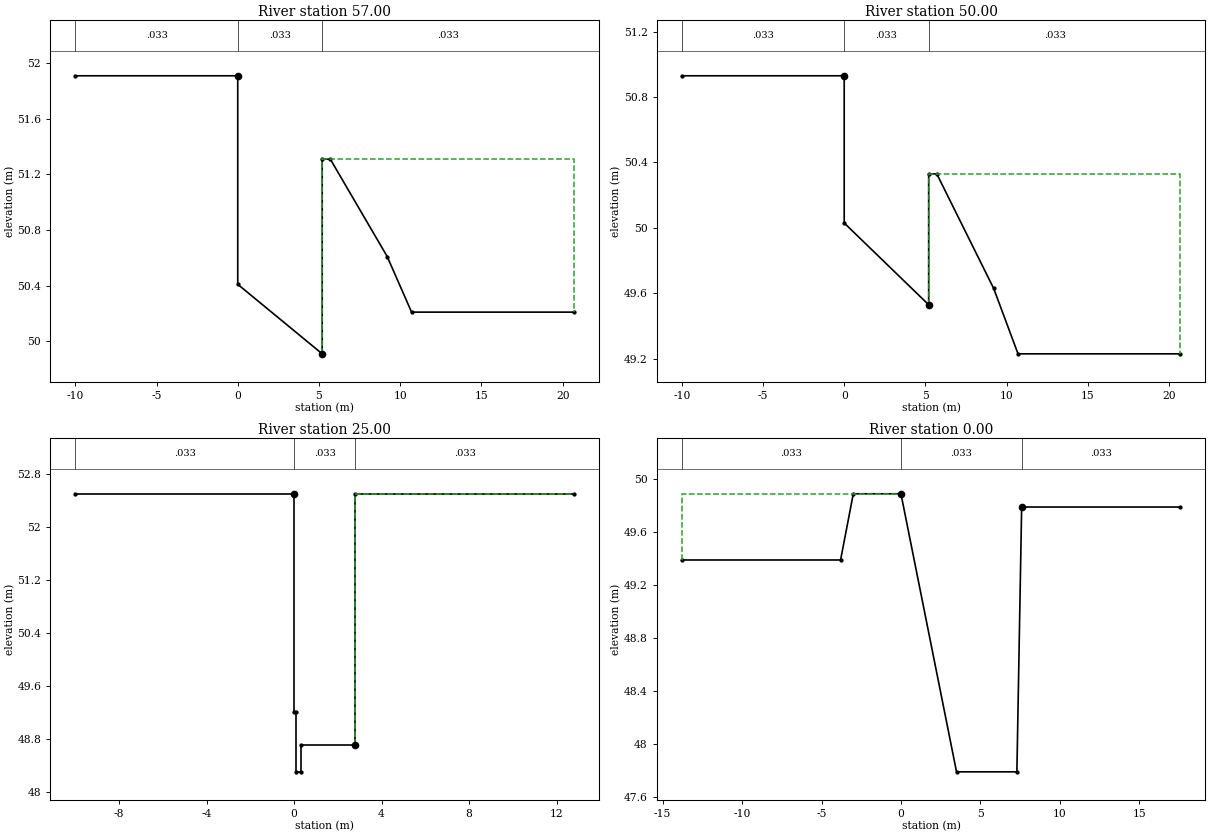
Type RM Length L Ch R = 1 ,57.00   ,7,7,7
BEGIN DESCRIPTION:
1.007
END DESCRIPTION:
#Sta/Elev= 9
     -10   51.91       0   51.91       0   50.41     5.2   49.91     5.2   51.31
     5.7   51.31     9.2   50.61    10.7   50.21    20.7   50.21
#Mann= 3 , 0 , 0
     -10    .033       0       0    .033       0     5.2    .033       0
#XS Ineff= 2 , 0
               0   51.91     5.2           51.31
Permanent Ineff=
       F       F
Bank Sta=0,5.2
XS Rating Curve= 0
Exp/Cntr=.3,.1

Type RM Length L Ch R = 1 ,50.00   ,25,25,25
BEGIN DESCRIPTION:
1
END DESCRIPTION:
#Sta/Elev= 9
     -10   50.93       0   50.93       0   50.03     5.2   49.53     5.2   50.33
     5.7   50.33     9.2   49.63    10.7   49.23    20.7   49.23
#Mann= 3 , 0 , 0
     -10    .033       0       0    .033       0     5.2    .033       0
#XS Ineff= 2 , 0
               0   50.93     5.2           50.33
Permanent Ineff=
       F       F
Bank Sta=0,5.2
XS Rating Curve= 0
Exp/Cntr=.3,.1

Type RM Length L Ch R = 1 ,25.00   ,25,25,25
BEGIN DESCRIPTION:
0.025
END DESCRIPTION:
#Sta/Elev= 10
     -10    52.5       0    52.5       0    49.2      .1    49.2      .1    48.3
      .3    48.3      .3    48.7     2.8    48.7     2.8    52.5    12.8    52.5
#Mann= 3 , 0 , 0
     -10    .033       0       0    .033       0     2.8    .033       0
#XS Ineff= 2 , 0
               0    52.5     2.8            52.5
Permanent Ineff=
       F       F
Bank Sta=0,2.8
XS Rating Curve= 0
Exp/Cntr=.3,.1

Type RM Length L Ch R = 1 ,0.00    ,0,0,0
BEGIN DESCRIPTION:
0
END DESCRIPTION:
#Sta/Elev= 8
   -13.8   49.39    -3.8   49.39      -3   49.89       0   49.89     3.5   47.79
     7.3   47.79     7.6   49.79    17.6   49.79
#Mann= 3 , 0 , 0
   -13.8    .033       0       0    .033       0     7.6    .033       0
#XS Ineff= 2 , 0
               0   49.89     7.6           49.79
Permanent Ineff=
       F       F
Bank Sta=0,7.6
XS Rating Curve= 0
Exp/Cntr=.3,.1

Chan Stop Cuts=-1