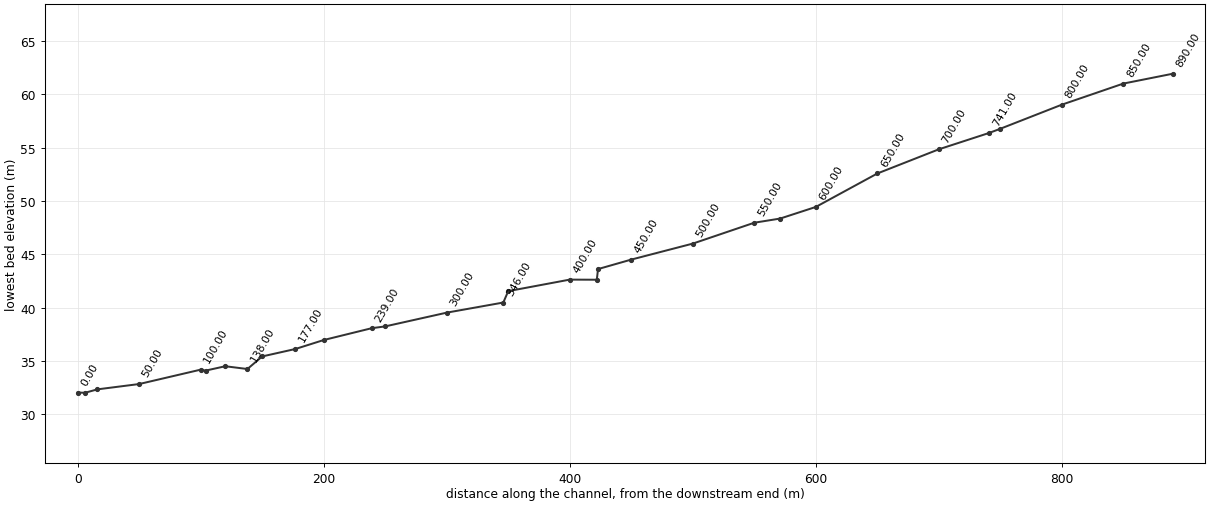
--- CHUNG.prj (project) ---

Proj Title=CHUNG
Current Plan=p01
Default Exp/Contr=.3,.1
SI Units
Geom File=g01
Flow File=f01
Plan File=p01
Y Axis Title=Elevation
X Axis Title(PF)=Main Channel Distance
X Axis Title(XS)=Station
BEGIN DESCRIPTION:
           BACK WATER COMPUTATION
      APPLICATION OF HEC-2 BY Samju Construction Engineering
      CHUNGSUKKYO-STREEM : 30 YR
END DESCRIPTION:
DSS Export Rating Curves= 0
DSS Export Rating Curve Sorted= 0
DSS Export Volume Flow Curves= 0
DXF OffsetX= 0
DXF OffsetY= 0
DXF ScaleX= 1
DXF ScaleY= 10

--- CHUNG.p01 (plan) ---

Plan Title=Imported Plan 01
Version=Version 3.0.1  Mar 2001
Short Identifier=Imported Pla
Geom File=g01
Flow File=f01
Subcritical Flow
K Sum by GR= 0
Std Step Tol= 0.003
Critical Tol= 0.003
Num of Std Step Trials= 20
Max Error Tol= 0.1
Flow Tol Ratio= 0.001
Split Flow NTrial= 30
Split Flow Tol= 0.02
Split Flow Ratio= 0.02
Log Output Level= 0
Friction Slope Method= 1
Unsteady Friction Slope Method= 2
Parabolic Critical Depth
Global Vel Dist= 0 , 0 , 0
Global Log Level= 0
CheckData=True
Encroach Param=-1 ,0,0, 0
Computation Interval=1HOUR
Output Interval=1HOUR
Run HTab= 0
Run UNet= 0
Run PostProcess= 0
UNET Theta= 1
UNET ZTol= 0.02
UNET ZSATol= 0.1
UNET MxIter= 20
UNET MaxInSteps= 20
UNET DtIC= 0
UNET DtMin= 0
UNET MaxCRTS= 20
UNET WFStab= 2
UNET SFStab= 1
UNET WFX= 1
UNET SFX= 1
UNET Convert EG Bridges=-1
UNET Use Existing IB Tables=-1
Instantaneous Interval=1HOUR
Write IC File= 0
Write Velocity= 0
Write Detailed= 0

--- CHUNG.f01 (steady flow) ---

Flow Title=Imported Flow 01
Version=Version 3.0.1  Mar 2001
Number of Profiles= 5
Profile Names=10YR,20YR,30YR,50YR,80YR
River Rch & RM=RIVER-1,Reach-1         ,890.00
   11.22   12.36   13.03   13.87   14.64
Boundary for River Rch & Prof#=RIVER-1,Reach-1         , 1
Up Type= 0
Dn Type= 3
Dn Slope=.026
Boundary for River Rch & Prof#=RIVER-1,Reach-1         , 2
Up Type= 0
Dn Type= 3
Dn Slope=.026
Boundary for River Rch & Prof#=RIVER-1,Reach-1         , 3
Up Type= 0
Dn Type= 3
Dn Slope=.026
Boundary for River Rch & Prof#=RIVER-1,Reach-1         , 4
Up Type= 0
Dn Type= 3
Dn Slope=.026
Boundary for River Rch & Prof#=RIVER-1,Reach-1         , 5
Up Type= 0
Dn Type= 3
Dn Slope=.026
DSS Import GetInterval= 0
DSS Import GetPeak= 0
DSS Import FillOption= 0

--- CHUNG.g01 (geometry) ---

Geom Title=Imported Geom 01
Version=Version 3.0.1  Mar 2001

River Reach=RIVER-1         ,Reach-1
Reach XY= 2
              .5             .95              .5             .05

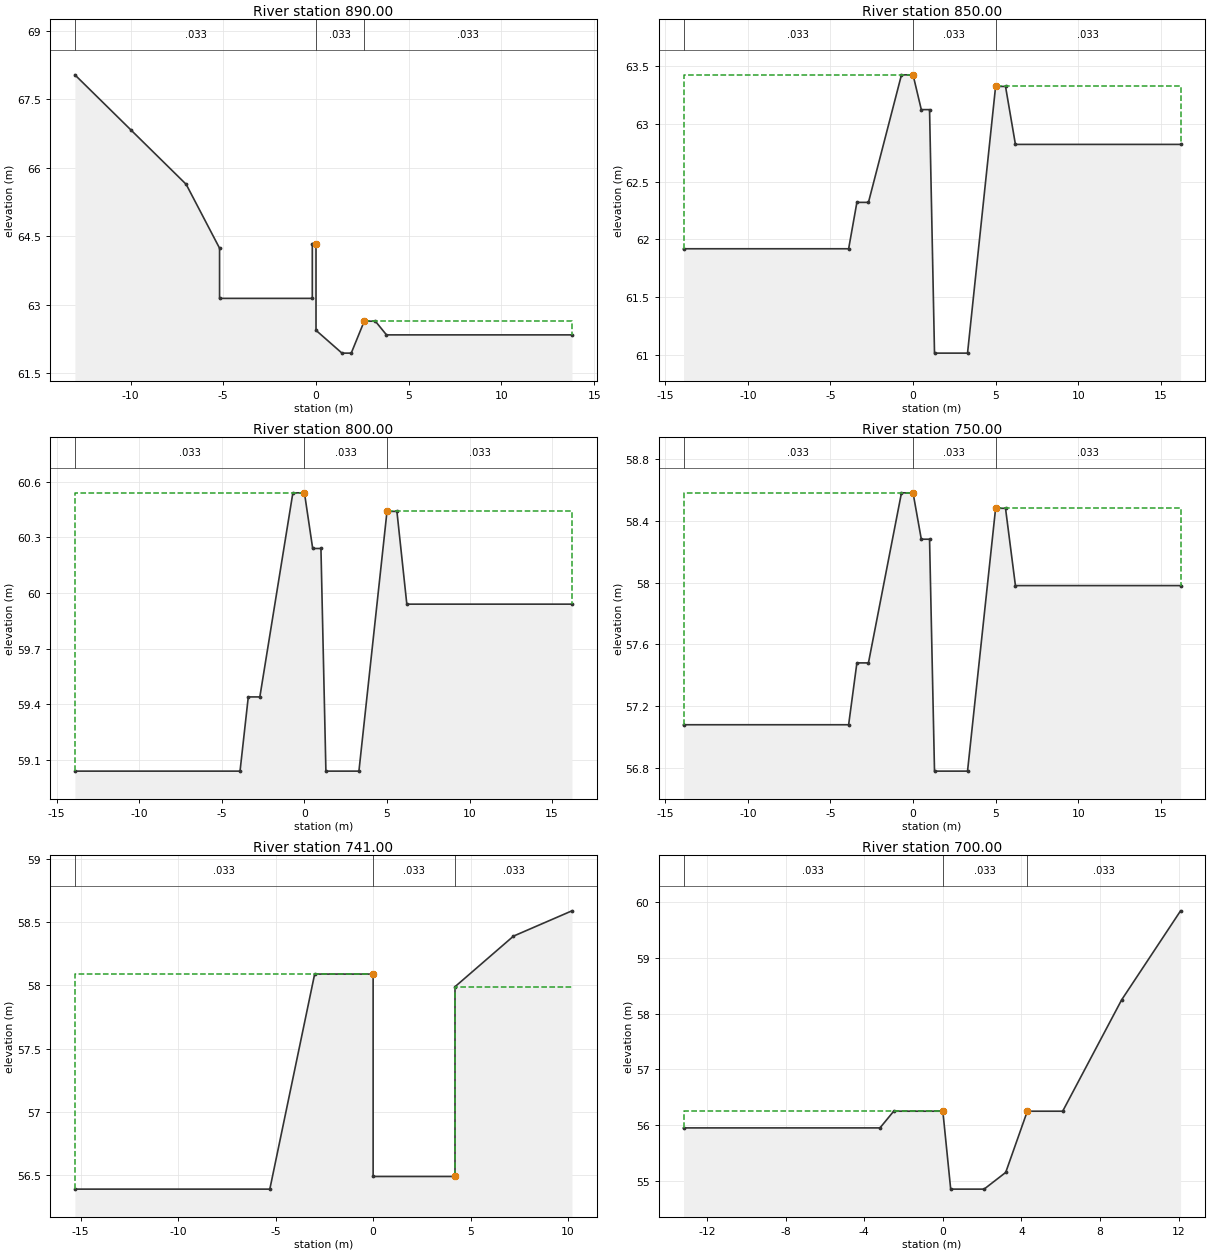
Type RM Length L Ch R = 1 ,890.00  ,40,40,40
BEGIN DESCRIPTION:
17.04
END DESCRIPTION:
#Sta/Elev= 15
     -13   68.04     -10   66.84      -7   65.64    -5.2   64.24    -5.2   63.14
     -.2   63.14     -.2   64.34       0   64.34       0   62.44     1.4   61.94
     1.9   61.94     2.6   62.64     3.2   62.64     3.8   62.34    13.8   62.34
#Mann= 3 , 0 , 0
     -13    .033       0       0    .033       0     2.6    .033       0
#XS Ineff= 2 , 0
               0   64.34     2.6           62.64
Permanent Ineff=
       F       F
Bank Sta=0,2.6
XS Rating Curve= 0
Exp/Cntr=.3,.1

Type RM Length L Ch R = 1 ,850.00  ,50,50,50
BEGIN DESCRIPTION:
17
END DESCRIPTION:
#Sta/Elev= 14
   -13.9   61.92    -3.9   61.92    -3.4   62.32    -2.7   62.32     -.7   63.42
       0   63.42      .5   63.12       1   63.12     1.3   61.02     3.3   61.02
       5   63.32     5.6   63.32     6.2   62.82    16.2   62.82
#Mann= 3 , 0 , 0
   -13.9    .033       0       0    .033       0       5    .033       0
#XS Ineff= 2 , 0
               0   63.42       5           63.32
Permanent Ineff=
       F       F
Bank Sta=0,5
XS Rating Curve= 0
Exp/Cntr=.3,.1

Type RM Length L Ch R = 1 ,800.00  ,50,50,50
BEGIN DESCRIPTION:
16
END DESCRIPTION:
#Sta/Elev= 14
   -13.9   59.04    -3.9   59.04    -3.4   59.44    -2.7   59.44     -.7   60.54
       0   60.54      .5   60.24       1   60.24     1.3   59.04     3.3   59.04
       5   60.44     5.6   60.44     6.2   59.94    16.2   59.94
#Mann= 3 , 0 , 0
   -13.9    .033       0       0    .033       0       5    .033       0
#XS Ineff= 2 , 0
               0   60.54       5           60.44
Permanent Ineff=
       F       F
Bank Sta=0,5
XS Rating Curve= 0
Exp/Cntr=.3,.1

Type RM Length L Ch R = 1 ,750.00  ,9,9,9
BEGIN DESCRIPTION:
15
END DESCRIPTION:
#Sta/Elev= 14
   -13.9   57.08    -3.9   57.08    -3.4   57.48    -2.7   57.48     -.7   58.58
       0   58.58      .5   58.28       1   58.28     1.3   56.78     3.3   56.78
       5   58.48     5.6   58.48     6.2   57.98    16.2   57.98
#Mann= 3 , 0 , 0
   -13.9    .033       0       0    .033       0       5    .033       0
#XS Ineff= 2 , 0
               0   58.58       5           58.48
Permanent Ineff=
       F       F
Bank Sta=0,5
XS Rating Curve= 0
Exp/Cntr=.3,.1

Type RM Length L Ch R = 1 ,741.00  ,41,41,41
BEGIN DESCRIPTION:
14.041
END DESCRIPTION:
#Sta/Elev= 9
   -15.3   56.39    -5.3   56.39      -3   58.09       0   58.09       0   56.49
     4.2   56.49     4.2   57.99     7.2   58.39    10.2   58.59
#Mann= 3 , 0 , 0
   -15.3    .033       0       0    .033       0     4.2    .033       0
#XS Ineff= 2 , 0
               0   58.09     4.2           57.99
Permanent Ineff=
       F       F
Bank Sta=0,4.2
XS Rating Curve= 0
Exp/Cntr=.3,.1

Type RM Length L Ch R = 1 ,700.00  ,50,50,50
BEGIN DESCRIPTION:
14
END DESCRIPTION:
#Sta/Elev= 11
   -13.2   55.95    -3.2   55.95    -2.5   56.25       0   56.25      .4   54.85
     2.1   54.85     3.2   55.15     4.3   56.25     6.1   56.25     9.1   58.25
    12.1   59.85
#Mann= 3 , 0 , 0
   -13.2    .033       0       0    .033       0     4.3    .033       0
#XS Ineff= 2 , 0
               0   56.25     4.3           56.25
Permanent Ineff=
       F       F
Bank Sta=0,4.3
XS Rating Curve= 0
Exp/Cntr=.3,.1

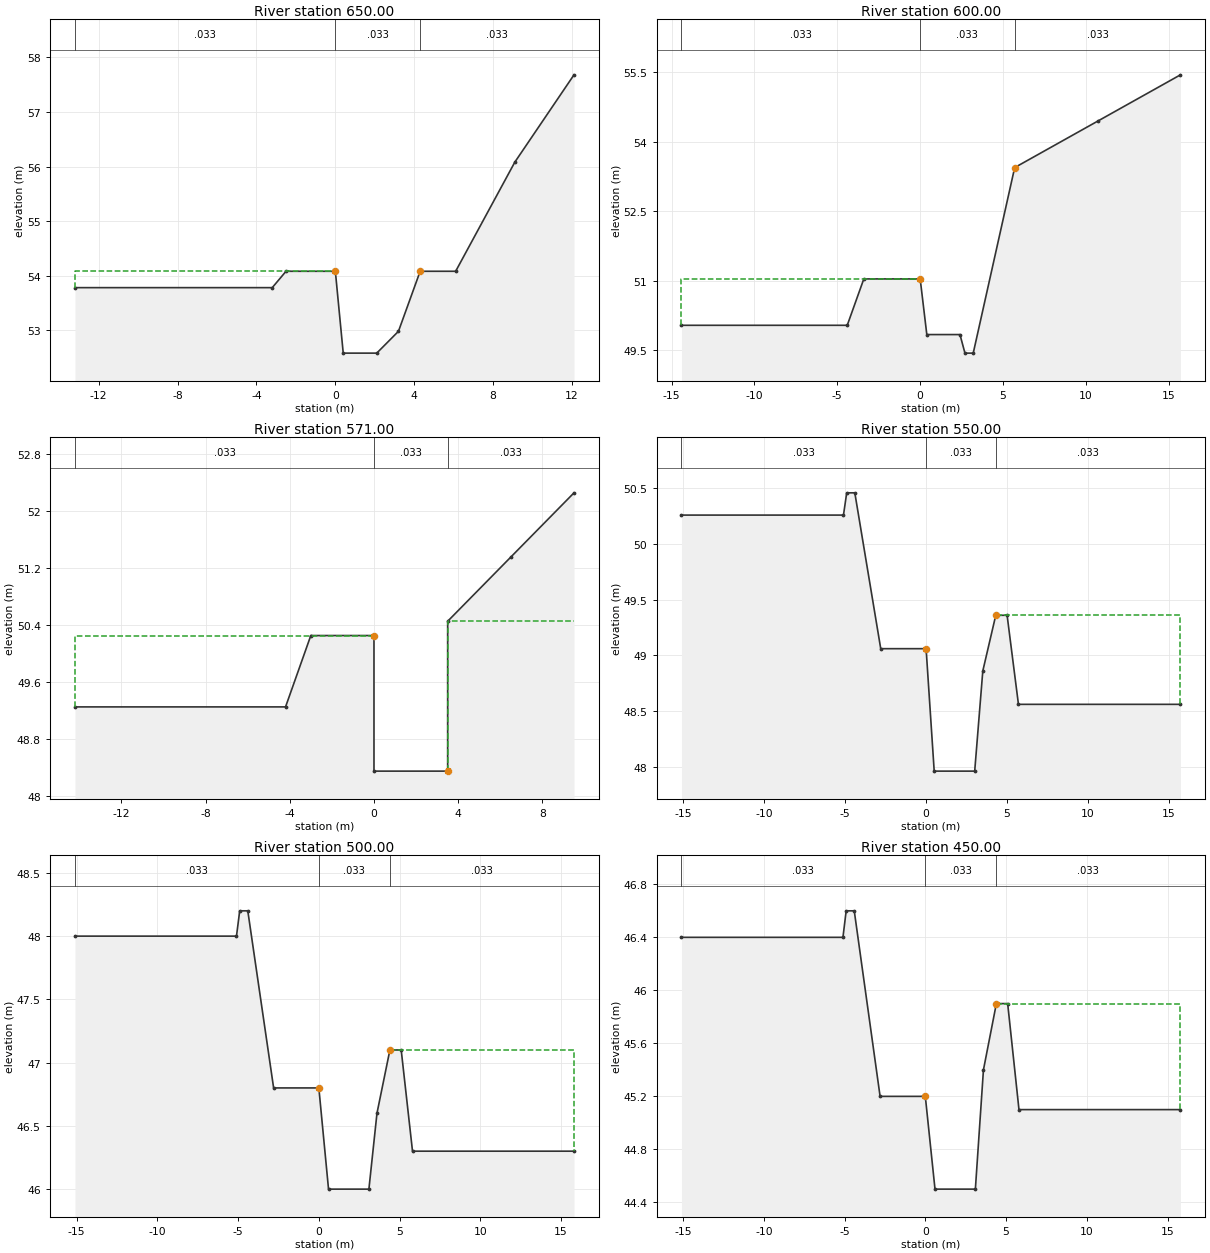
Type RM Length L Ch R = 1 ,650.00  ,50,50,50
BEGIN DESCRIPTION:
13
END DESCRIPTION:
#Sta/Elev= 11
   -13.2   53.78    -3.2   53.78    -2.5   54.08       0   54.08      .4   52.58
     2.1   52.58     3.2   52.98     4.3   54.08     6.1   54.08     9.1   56.08
    12.1   57.68
#Mann= 3 , 0 , 0
   -13.2    .033       0       0    .033       0     4.3    .033       0
#XS Ineff= 2 , 0
               0   54.08     4.3           54.08
Permanent Ineff=
       F       F
Bank Sta=0,4.3
XS Rating Curve= 0
Exp/Cntr=.3,.1

Type RM Length L Ch R = 1 ,600.00  ,29,29,29
BEGIN DESCRIPTION:
12
END DESCRIPTION:
#Sta/Elev= 11
   -14.4   50.04    -4.4   50.04    -3.4   51.04       0   51.04      .4   49.84
     2.4   49.84     2.7   49.44     3.2   49.44     5.7   53.44    10.7   54.44
    15.7   55.44
#Mann= 3 , 0 , 0
   -14.4    .033       0       0    .033       0     5.7    .033       0
#XS Ineff= 2 , 0
               0   51.04     5.7           53.44
Permanent Ineff=
       F       F
Bank Sta=0,5.7
XS Rating Curve= 0
Exp/Cntr=.3,.1

Type RM Length L Ch R = 1 ,571.00  ,21,21,21
BEGIN DESCRIPTION:
11.021
END DESCRIPTION:
#Sta/Elev= 9
   -14.2   49.25    -4.2   49.25      -3   50.25       0   50.25       0   48.35
     3.5   48.35     3.5   50.45     6.5   51.35     9.5   52.25
#Mann= 3 , 0 , 0
   -14.2    .033       0       0    .033       0     3.5    .033       0
#XS Ineff= 2 , 0
               0   50.25     3.5           50.45
Permanent Ineff=
       F       F
Bank Sta=0,3.5
XS Rating Curve= 0
Exp/Cntr=.3,.1

Type RM Length L Ch R = 1 ,550.00  ,50,50,50
BEGIN DESCRIPTION:
11
END DESCRIPTION:
#Sta/Elev= 13
   -15.1   50.26    -5.1   50.26    -4.9   50.46    -4.4   50.46    -2.8   49.06
       0   49.06      .5   47.96       3   47.96     3.5   48.86     4.3   49.36
       5   49.36     5.7   48.56    15.7   48.56
#Mann= 3 , 0 , 0
   -15.1    .033       0       0    .033       0     4.3    .033       0
#XS Ineff= 2 , 0
               0   49.06     4.3           49.36
Permanent Ineff=
       F       F
Bank Sta=0,4.3
XS Rating Curve= 0
Exp/Cntr=.3,.1

Type RM Length L Ch R = 1 ,500.00  ,50,50,50
BEGIN DESCRIPTION:
10
END DESCRIPTION:
#Sta/Elev= 13
   -15.1      48    -5.1      48    -4.9    48.2    -4.4    48.2    -2.8    46.8
       0    46.8      .6      46     3.1      46     3.6    46.6     4.4    47.1
     5.1    47.1     5.8    46.3    15.8    46.3
#Mann= 3 , 0 , 0
   -15.1    .033       0       0    .033       0     4.4    .033       0
#XS Ineff= 2 , 0
               0    46.8     4.4            47.1
Permanent Ineff=
       F       F
Bank Sta=0,4.4
XS Rating Curve= 0
Exp/Cntr=.3,.1

Type RM Length L Ch R = 1 ,450.00  ,27,27,27
BEGIN DESCRIPTION:
9
END DESCRIPTION:
#Sta/Elev= 13
   -15.1    46.4    -5.1    46.4    -4.9    46.6    -4.4    46.6    -2.8    45.2
       0    45.2      .6    44.5     3.1    44.5     3.6    45.4     4.4    45.9
     5.1    45.9     5.8    45.1    15.8    45.1
#Mann= 3 , 0 , 0
   -15.1    .033       0       0    .033       0     4.4    .033       0
#XS Ineff= 2 , 0
               0    45.2     4.4            45.9
Permanent Ineff=
       F       F
Bank Sta=0,4.4
XS Rating Curve= 0
Exp/Cntr=.3,.1

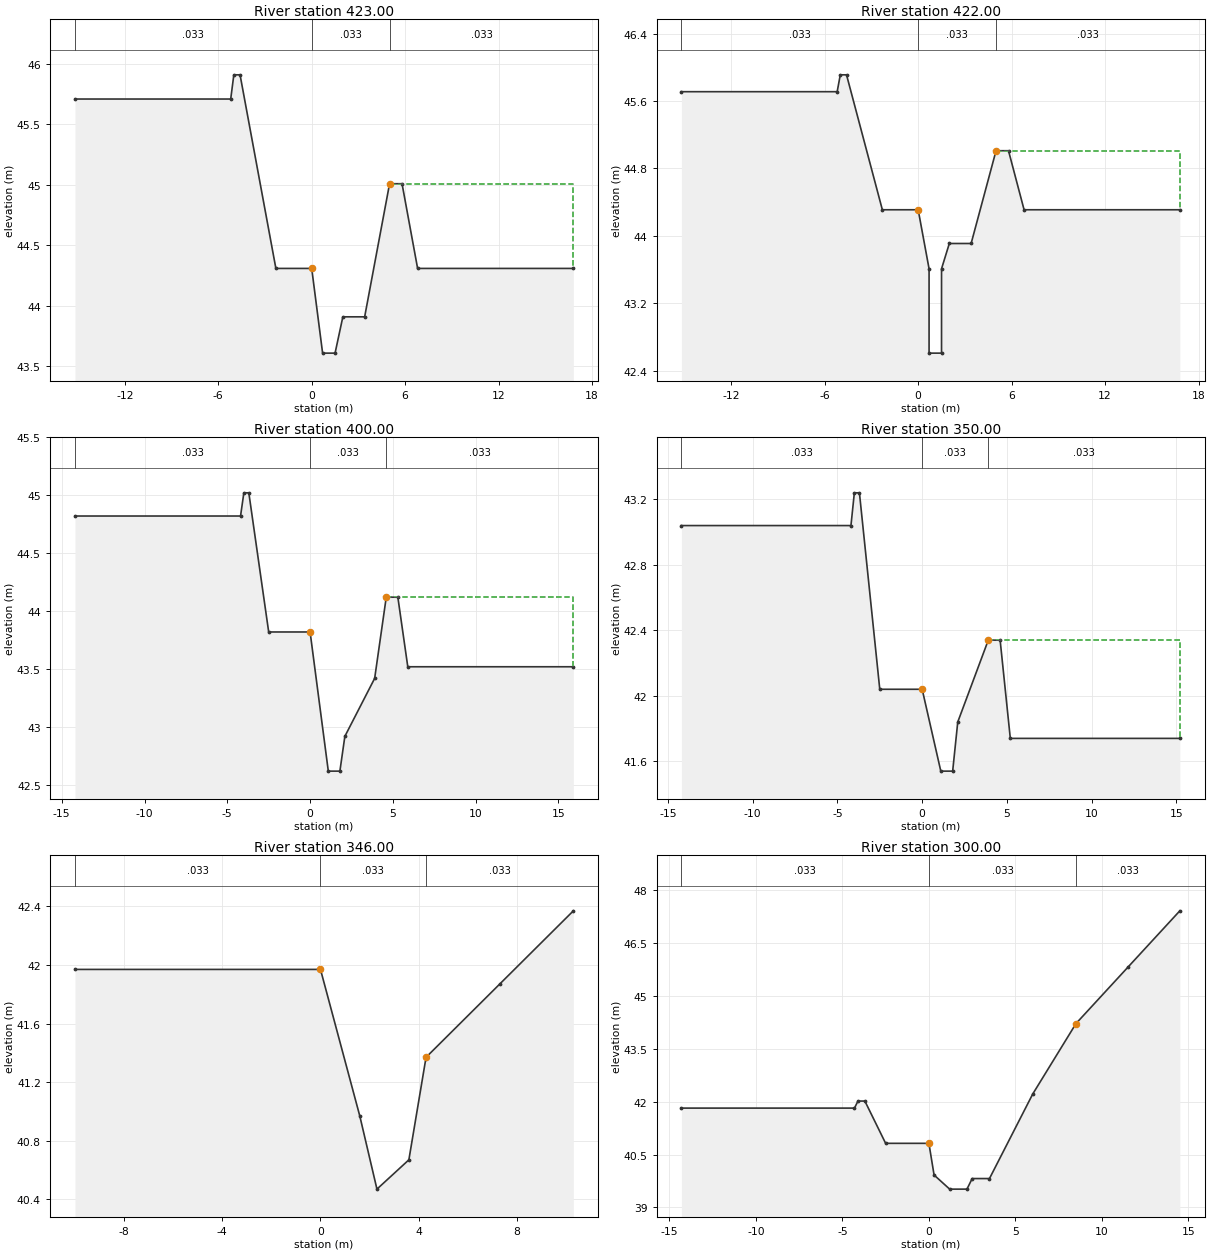
Type RM Length L Ch R = 1 ,423.00  ,1,1,1
BEGIN DESCRIPTION:
8.023
END DESCRIPTION:
#Sta/Elev= 14
   -15.2   45.71    -5.2   45.71      -5   45.91    -4.6   45.91    -2.3   44.31
       0   44.31      .7   43.61     1.5   43.61       2   43.91     3.4   43.91
       5   45.01     5.8   45.01     6.8   44.31    16.8   44.31
#Mann= 3 , 0 , 0
   -15.2    .033       0       0    .033       0       5    .033       0
#XS Ineff= 2 , 0
               0   44.31       5           45.01
Permanent Ineff=
       F       F
Bank Sta=0,5
XS Rating Curve= 0
Exp/Cntr=.3,.1

Type RM Length L Ch R = 1 ,422.00  ,22,22,22
BEGIN DESCRIPTION:
8.022
END DESCRIPTION:
#Sta/Elev= 16
   -15.2   45.71    -5.2   45.71      -5   45.91    -4.6   45.91    -2.3   44.31
       0   44.31      .7   43.61      .7   42.61     1.5   42.61     1.5   43.61
       2   43.91     3.4   43.91       5   45.01     5.8   45.01     6.8   44.31
    16.8   44.31
#Mann= 3 , 0 , 0
   -15.2    .033       0       0    .033       0       5    .033       0
#XS Ineff= 2 , 0
               0   44.31       5           45.01
Permanent Ineff=
       F       F
Bank Sta=0,5
XS Rating Curve= 0
Exp/Cntr=.3,.1

Type RM Length L Ch R = 1 ,400.00  ,50,50,50
BEGIN DESCRIPTION:
8
END DESCRIPTION:
#Sta/Elev= 14
   -14.2   44.82    -4.2   44.82      -4   45.02    -3.7   45.02    -2.5   43.82
       0   43.82     1.1   42.62     1.8   42.62     2.1   42.92     3.9   43.42
     4.6   44.12     5.3   44.12     5.9   43.52    15.9   43.52
#Mann= 3 , 0 , 0
   -14.2    .033       0       0    .033       0     4.6    .033       0
#XS Ineff= 2 , 0
               0   43.82     4.6           44.12
Permanent Ineff=
       F       F
Bank Sta=0,4.6
XS Rating Curve= 0
Exp/Cntr=.3,.1

Type RM Length L Ch R = 1 ,350.00  ,4,4,4
BEGIN DESCRIPTION:
7
END DESCRIPTION:
#Sta/Elev= 13
   -14.2   43.04    -4.2   43.04      -4   43.24    -3.7   43.24    -2.5   42.04
       0   42.04     1.1   41.54     1.8   41.54     2.1   41.84     3.9   42.34
     4.6   42.34     5.2   41.74    15.2   41.74
#Mann= 3 , 0 , 0
   -14.2    .033       0       0    .033       0     3.9    .033       0
#XS Ineff= 2 , 0
               0   42.04     3.9           42.34
Permanent Ineff=
       F       F
Bank Sta=0,3.9
XS Rating Curve= 0
Exp/Cntr=.3,.1

Type RM Length L Ch R = 1 ,346.00  ,46,46,46
BEGIN DESCRIPTION:
6.046
END DESCRIPTION:
#Sta/Elev= 8
     -10   41.97       0   41.97     1.6   40.97     2.3   40.47     3.6   40.67
     4.3   41.37     7.3   41.87    10.3   42.37
#Mann= 3 , 0 , 0
     -10    .033       0       0    .033       0     4.3    .033       0
#XS Ineff= 2 , 0
               0   41.97     4.3           41.37
Permanent Ineff=
       F       F
Bank Sta=0,4.3
XS Rating Curve= 0
Exp/Cntr=.3,.1

Type RM Length L Ch R = 1 ,300.00  ,50,50,50
BEGIN DESCRIPTION:
6
END DESCRIPTION:
#Sta/Elev= 15
   -14.3   41.82    -4.3   41.82    -4.1   42.02    -3.7   42.02    -2.5   40.82
       0   40.82      .3   39.92     1.2   39.52     2.2   39.52     2.5   39.82
     3.5   39.82       6   42.22     8.5   44.22    11.5   45.82    14.5   47.42
#Mann= 3 , 0 , 0
   -14.3    .033       0       0    .033       0     8.5    .033       0
#XS Ineff= 2 , 0
               0   40.82     8.5           44.22
Permanent Ineff=
       F       F
Bank Sta=0,8.5
XS Rating Curve= 0
Exp/Cntr=.3,.1

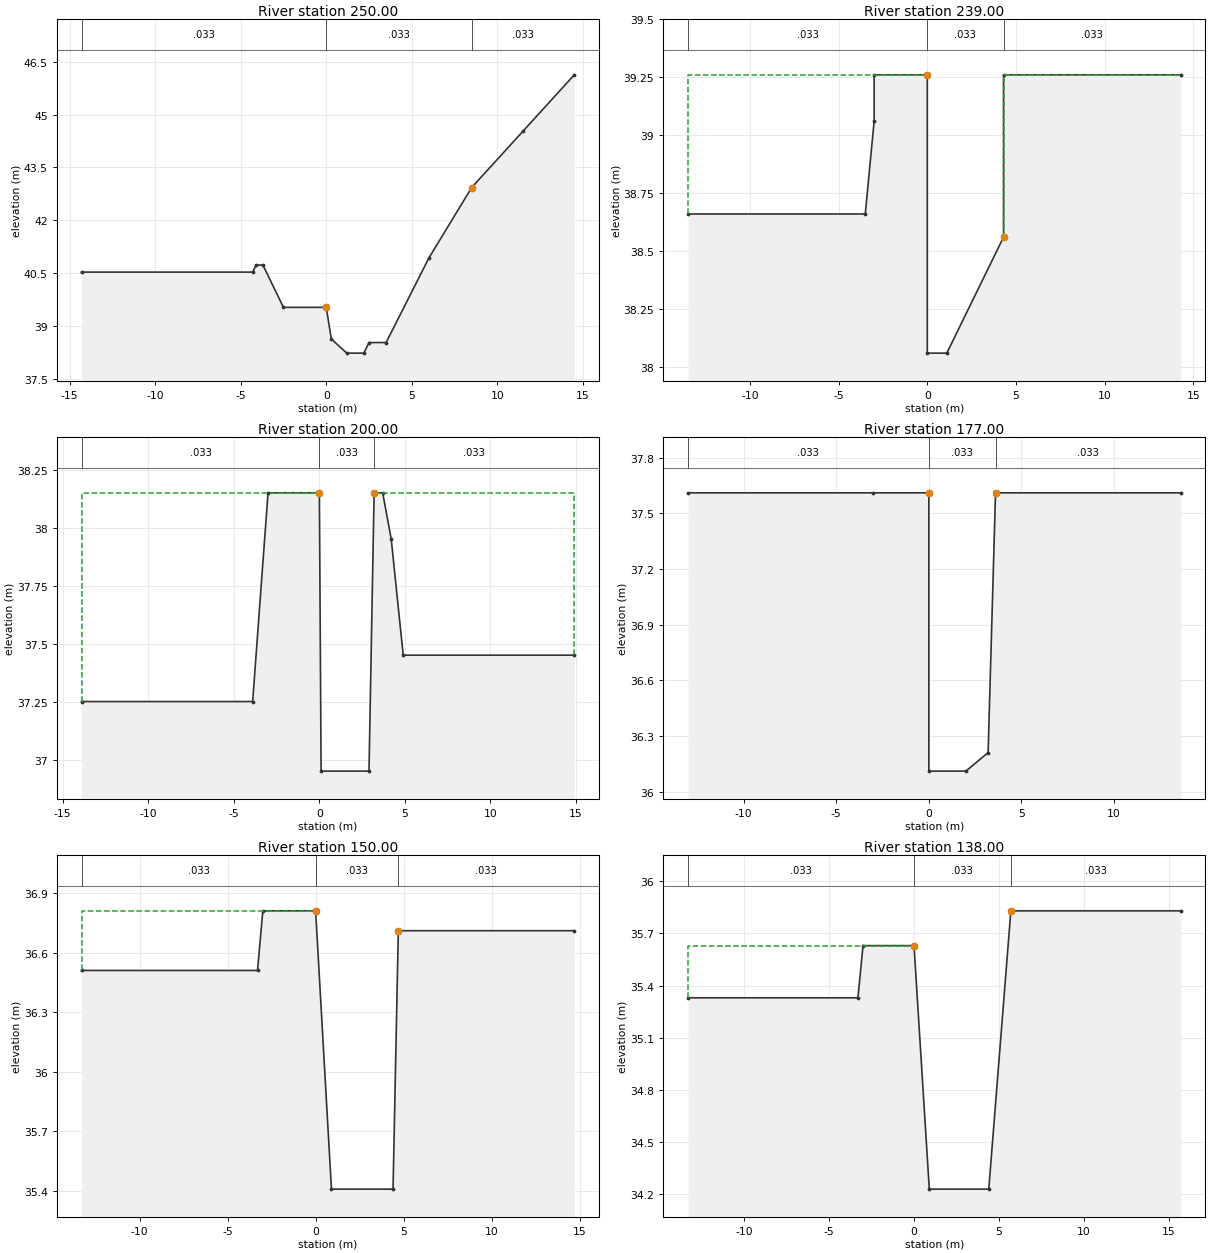
Type RM Length L Ch R = 1 ,250.00  ,11,11,11
BEGIN DESCRIPTION:
5
END DESCRIPTION:
#Sta/Elev= 15
   -14.3   40.53    -4.3   40.53    -4.1   40.73    -3.7   40.73    -2.5   39.53
       0   39.53      .3   38.63     1.2   38.23     2.2   38.23     2.5   38.53
     3.5   38.53       6   40.93     8.5   42.93    11.5   44.53    14.5   46.13
#Mann= 3 , 0 , 0
   -14.3    .033       0       0    .033       0     8.5    .033       0
#XS Ineff= 2 , 0
               0   39.53     8.5           42.93
Permanent Ineff=
       F       F
Bank Sta=0,8.5
XS Rating Curve= 0
Exp/Cntr=.3,.1

Type RM Length L Ch R = 1 ,239.00  ,39,39,39
BEGIN DESCRIPTION:
4.039
END DESCRIPTION:
#Sta/Elev= 10
   -13.5   38.66    -3.5   38.66      -3   39.06      -3   39.26       0   39.26
       0   38.06     1.1   38.06     4.3   38.56     4.3   39.26    14.3   39.26
#Mann= 3 , 0 , 0
   -13.5    .033       0       0    .033       0     4.3    .033       0
#XS Ineff= 2 , 0
               0   39.26     4.3           39.26
Permanent Ineff=
       F       F
Bank Sta=0,4.3
XS Rating Curve= 0
Exp/Cntr=.3,.1

Type RM Length L Ch R = 1 ,200.00  ,23,23,23
BEGIN DESCRIPTION:
4
END DESCRIPTION:
#Sta/Elev= 11
   -13.9   37.25    -3.9   37.25      -3   38.15       0   38.15      .1   36.95
     2.9   36.95     3.2   38.15     3.7   38.15     4.2   37.95     4.9   37.45
    14.9   37.45
#Mann= 3 , 0 , 0
   -13.9    .033       0       0    .033       0     3.2    .033       0
#XS Ineff= 2 , 0
               0   38.15     3.2           38.15
Permanent Ineff=
       F       F
Bank Sta=0,3.2
XS Rating Curve= 0
Exp/Cntr=.3,.1

Type RM Length L Ch R = 1 ,177.00  ,27,27,27
BEGIN DESCRIPTION:
3.027
END DESCRIPTION:
#Sta/Elev= 8
     -13   37.61      -3   37.61       0   37.61       0   36.11       2   36.11
     3.2   36.21     3.6   37.61    13.6   37.61
#Mann= 3 , 0 , 0
     -13    .033       0       0    .033       0     3.6    .033       0
#XS Ineff= 2 , 0
               0   37.61     3.6           37.61
Permanent Ineff=
       F       F
Bank Sta=0,3.6
XS Rating Curve= 0
Exp/Cntr=.3,.1

Type RM Length L Ch R = 1 ,150.00  ,12,12,12
BEGIN DESCRIPTION:
3
END DESCRIPTION:
#Sta/Elev= 8
   -13.3   36.51    -3.3   36.51      -3   36.81       0   36.81      .9   35.41
     4.4   35.41     4.7   36.71    14.7   36.71
#Mann= 3 , 0 , 0
   -13.3    .033       0       0    .033       0     4.7    .033       0
#XS Ineff= 2 , 0
               0   36.81     4.7           36.71
Permanent Ineff=
       F       F
Bank Sta=0,4.7
XS Rating Curve= 0
Exp/Cntr=.3,.1

Type RM Length L Ch R = 1 ,138.00  ,18,18,18
BEGIN DESCRIPTION:
2.038
END DESCRIPTION:
#Sta/Elev= 8
   -13.3   35.33    -3.3   35.33      -3   35.63       0   35.63      .9   34.23
     4.4   34.23     5.7   35.83    15.7   35.83
#Mann= 3 , 0 , 0
   -13.3    .033       0       0    .033       0     5.7    .033       0
#XS Ineff= 2 , 0
               0   35.63     5.7           35.83
Permanent Ineff=
       F       F
Bank Sta=0,5.7
XS Rating Curve= 0
Exp/Cntr=.3,.1

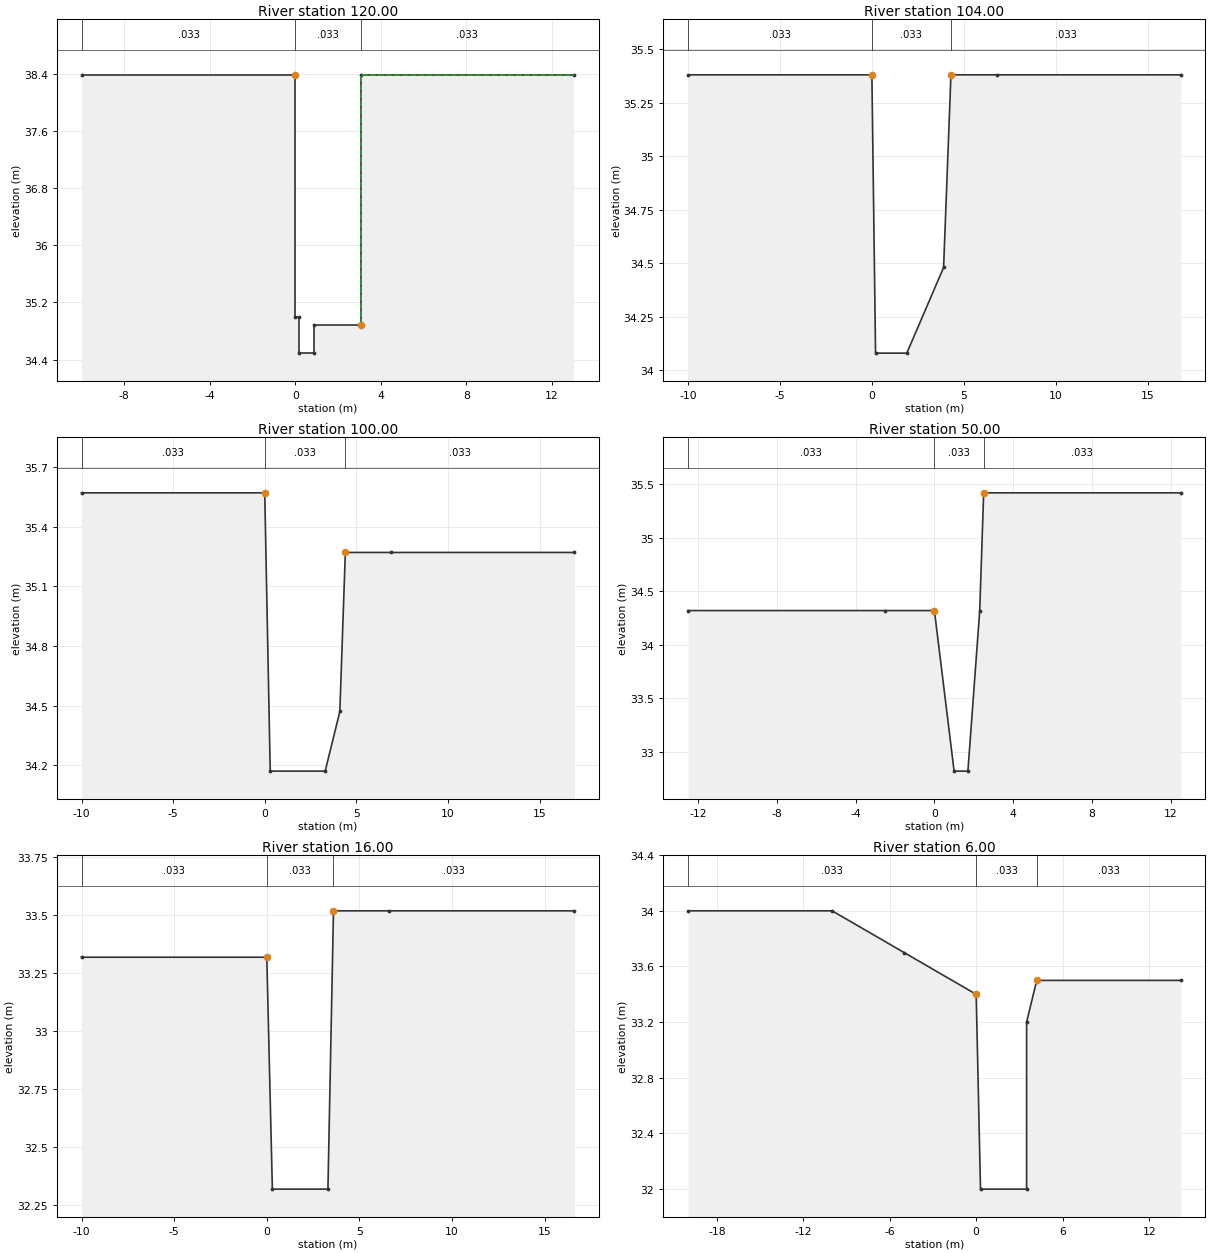
Type RM Length L Ch R = 1 ,120.00  ,16,16,16
BEGIN DESCRIPTION:
2.02
END DESCRIPTION:
#Sta/Elev= 10
     -10   38.39       0   38.39       0   34.99     .15   34.99     .15   34.49
     .85   34.49     .85   34.89    3.05   34.89    3.05   38.39   13.05   38.39
#Mann= 3 , 0 , 0
     -10    .033       0       0    .033       0    3.05    .033       0
#XS Ineff= 2 , 0
               0   38.39    3.05           38.39
Permanent Ineff=
       F       F
Bank Sta=0,3.05
XS Rating Curve= 0
Exp/Cntr=.3,.1

Type RM Length L Ch R = 1 ,104.00  ,4,4,4
BEGIN DESCRIPTION:
2.004
END DESCRIPTION:
#Sta/Elev= 8
     -10   35.38       0   35.38      .2   34.08     1.9   34.08     3.9   34.48
     4.3   35.38     6.8   35.38    16.8   35.38
#Mann= 3 , 0 , 0
     -10    .033       0       0    .033       0     4.3    .033       0
#XS Ineff= 2 , 0
               0   35.38     4.3           35.38
Permanent Ineff=
       F       F
Bank Sta=0,4.3
XS Rating Curve= 0
Exp/Cntr=.3,.1

Type RM Length L Ch R = 1 ,100.00  ,50,50,50
BEGIN DESCRIPTION:
2
END DESCRIPTION:
#Sta/Elev= 8
     -10   35.57       0   35.57      .3   34.17     3.3   34.17     4.1   34.47
     4.4   35.27     6.9   35.27    16.9   35.27
#Mann= 3 , 0 , 0
     -10    .033       0       0    .033       0     4.4    .033       0
#XS Ineff= 2 , 0
               0   35.57     4.4           35.27
Permanent Ineff=
       F       F
Bank Sta=0,4.4
XS Rating Curve= 0
Exp/Cntr=.3,.1

Type RM Length L Ch R = 1 ,50.00   ,34,34,34
BEGIN DESCRIPTION:
1
END DESCRIPTION:
#Sta/Elev= 8
   -12.5   34.32    -2.5   34.32       0   34.32       1   32.82     1.7   32.82
     2.3   34.32     2.5   35.42    12.5   35.42
#Mann= 3 , 0 , 0
   -12.5    .033       0       0    .033       0     2.5    .033       0
#XS Ineff= 2 , 0
               0   34.32     2.5           35.42
Permanent Ineff=
       F       F
Bank Sta=0,2.5
XS Rating Curve= 0
Exp/Cntr=.3,.1

Type RM Length L Ch R = 1 ,16.00   ,10,10,10
BEGIN DESCRIPTION:
0.016
END DESCRIPTION:
#Sta/Elev= 7
     -10   33.32       0   33.32      .3   32.32     3.3   32.32     3.6   33.52
     6.6   33.52    16.6   33.52
#Mann= 3 , 0 , 0
     -10    .033       0       0    .033       0     3.6    .033       0
#XS Ineff= 2 , 0
               0   33.32     3.6           33.52
Permanent Ineff=
       F       F
Bank Sta=0,3.6
XS Rating Curve= 0
Exp/Cntr=.3,.1

Type RM Length L Ch R = 1 ,6.00    ,6,6,6
BEGIN DESCRIPTION:
0.006
END DESCRIPTION:
#Sta/Elev= 9
     -20      34     -10      34      -5    33.7       0    33.4      .3      32
     3.5      32     3.5    33.2     4.2    33.5    14.2    33.5
#Mann= 3 , 0 , 0
     -20    .033       0       0    .033       0     4.2    .033       0
#XS Ineff= 2 , 0
               0    33.4     4.2            33.5
Permanent Ineff=
       F       F
Bank Sta=0,4.2
XS Rating Curve= 0
Exp/Cntr=.3,.1

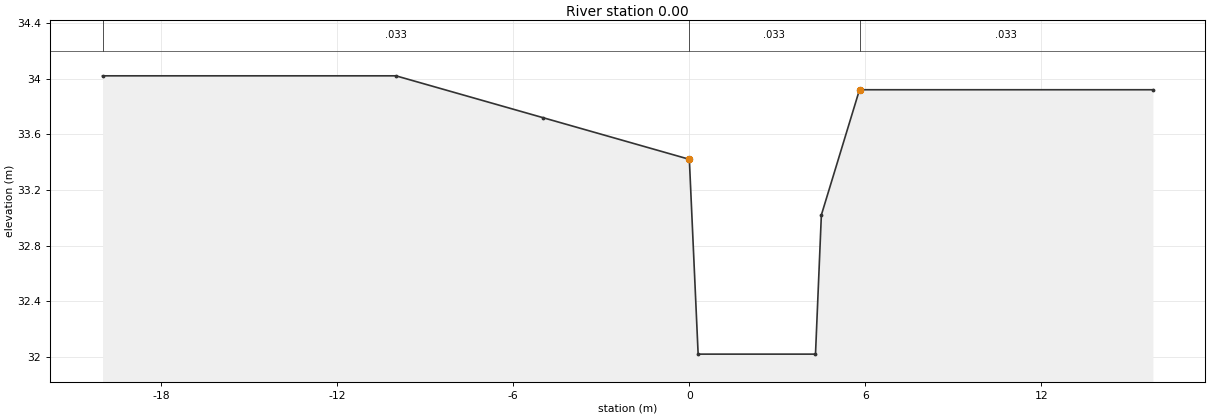
Type RM Length L Ch R = 1 ,0.00    ,0,0,0
BEGIN DESCRIPTION:
0
END DESCRIPTION:
#Sta/Elev= 9
     -20   34.02     -10   34.02      -5   33.72       0   33.42      .3   32.02
     4.3   32.02     4.5   33.02     5.8   33.92    15.8   33.92
#Mann= 3 , 0 , 0
     -20    .033       0       0    .033       0     5.8    .033       0
#XS Ineff= 2 , 0
               0   33.42     5.8           33.92
Permanent Ineff=
       F       F
Bank Sta=0,5.8
XS Rating Curve= 0
Exp/Cntr=.3,.1

Chan Stop Cuts=-1