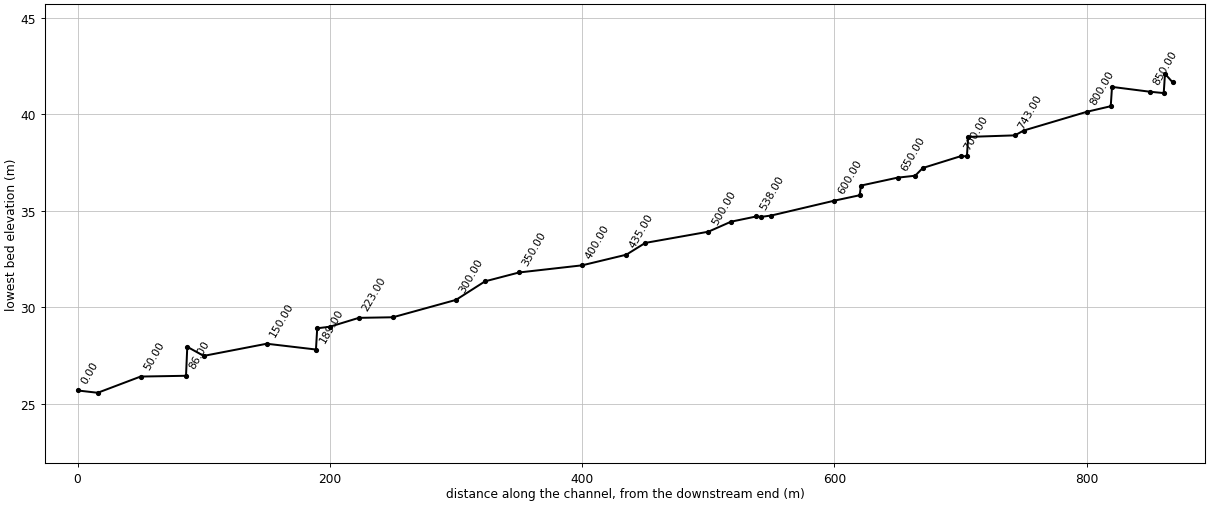
--- HRC.prj (project) ---

Proj Title=HRC
Current Plan=p01
Default Exp/Contr=.3,.1
SI Units
Geom File=g01
Flow File=f01
Plan File=p01
Y Axis Title=Elevation
X Axis Title(PF)=Main Channel Distance
X Axis Title(XS)=Station
BEGIN DESCRIPTION:
           BACK WATER COMPUTATION
      APPLICATION OF HEC-2 BY Samju Construction Engineering
      HWEROUNG-STREEM : 30 YR
END DESCRIPTION:
DSS Export Rating Curves= 0
DSS Export Rating Curve Sorted= 0
DSS Export Volume Flow Curves= 0
DXF OffsetX= 0
DXF OffsetY= 0
DXF ScaleX= 1
DXF ScaleY= 10

--- HRC.p01 (plan) ---

Plan Title=Imported Plan 01
Version=Version 3.0.1  Mar 2001
Short Identifier=Imported Pla
Geom File=g01
Flow File=f01
Subcritical Flow
K Sum by GR= 0
Std Step Tol= 0.003
Critical Tol= 0.003
Num of Std Step Trials= 20
Max Error Tol= 0.1
Flow Tol Ratio= 0.001
Split Flow NTrial= 30
Split Flow Tol= 0.02
Split Flow Ratio= 0.02
Log Output Level= 0
Friction Slope Method= 1
Unsteady Friction Slope Method= 2
Parabolic Critical Depth
Global Vel Dist= 0 , 0 , 0
Global Log Level= 0
CheckData=True
Encroach Param=-1 ,0,0, 0
Computation Interval=1HOUR
Output Interval=1HOUR
Run HTab= 0
Run UNet= 0
Run PostProcess= 0
UNET Theta= 1
UNET ZTol= 0.02
UNET ZSATol= 0.1
UNET MxIter= 20
UNET MaxInSteps= 20
UNET DtIC= 0
UNET DtMin= 0
UNET MaxCRTS= 20
UNET WFStab= 2
UNET SFStab= 1
UNET WFX= 1
UNET SFX= 1
UNET Convert EG Bridges=-1
UNET Use Existing IB Tables=-1
Instantaneous Interval=1HOUR
Write IC File= 0
Write Velocity= 0
Write Detailed= 0

--- HRC.f01 (steady flow) ---

Flow Title=Imported Flow 01
Version=Version 3.0.1  Mar 2001
Number of Profiles= 5
Profile Names=10YR,20YR,30YR,50YR,80YR
River Rch & RM=RIVER-1,Reach-1         ,868.00
   12.86   14.17   14.93    15.9   16.78
Boundary for River Rch & Prof#=RIVER-1,Reach-1         , 1
Up Type= 0
Dn Type= 3
Dn Slope=.02
Boundary for River Rch & Prof#=RIVER-1,Reach-1         , 2
Up Type= 0
Dn Type= 3
Dn Slope=.02
Boundary for River Rch & Prof#=RIVER-1,Reach-1         , 3
Up Type= 0
Dn Type= 3
Dn Slope=.02
Boundary for River Rch & Prof#=RIVER-1,Reach-1         , 4
Up Type= 0
Dn Type= 3
Dn Slope=.02
Boundary for River Rch & Prof#=RIVER-1,Reach-1         , 5
Up Type= 0
Dn Type= 3
Dn Slope=.02
DSS Import GetInterval= 0
DSS Import GetPeak= 0
DSS Import FillOption= 0

--- HRC.g01 (geometry) ---

Geom Title=Imported Geom 01
Version=Version 3.0.1  Mar 2001

River Reach=RIVER-1         ,Reach-1
Reach XY= 2
              .5             .95              .5             .05

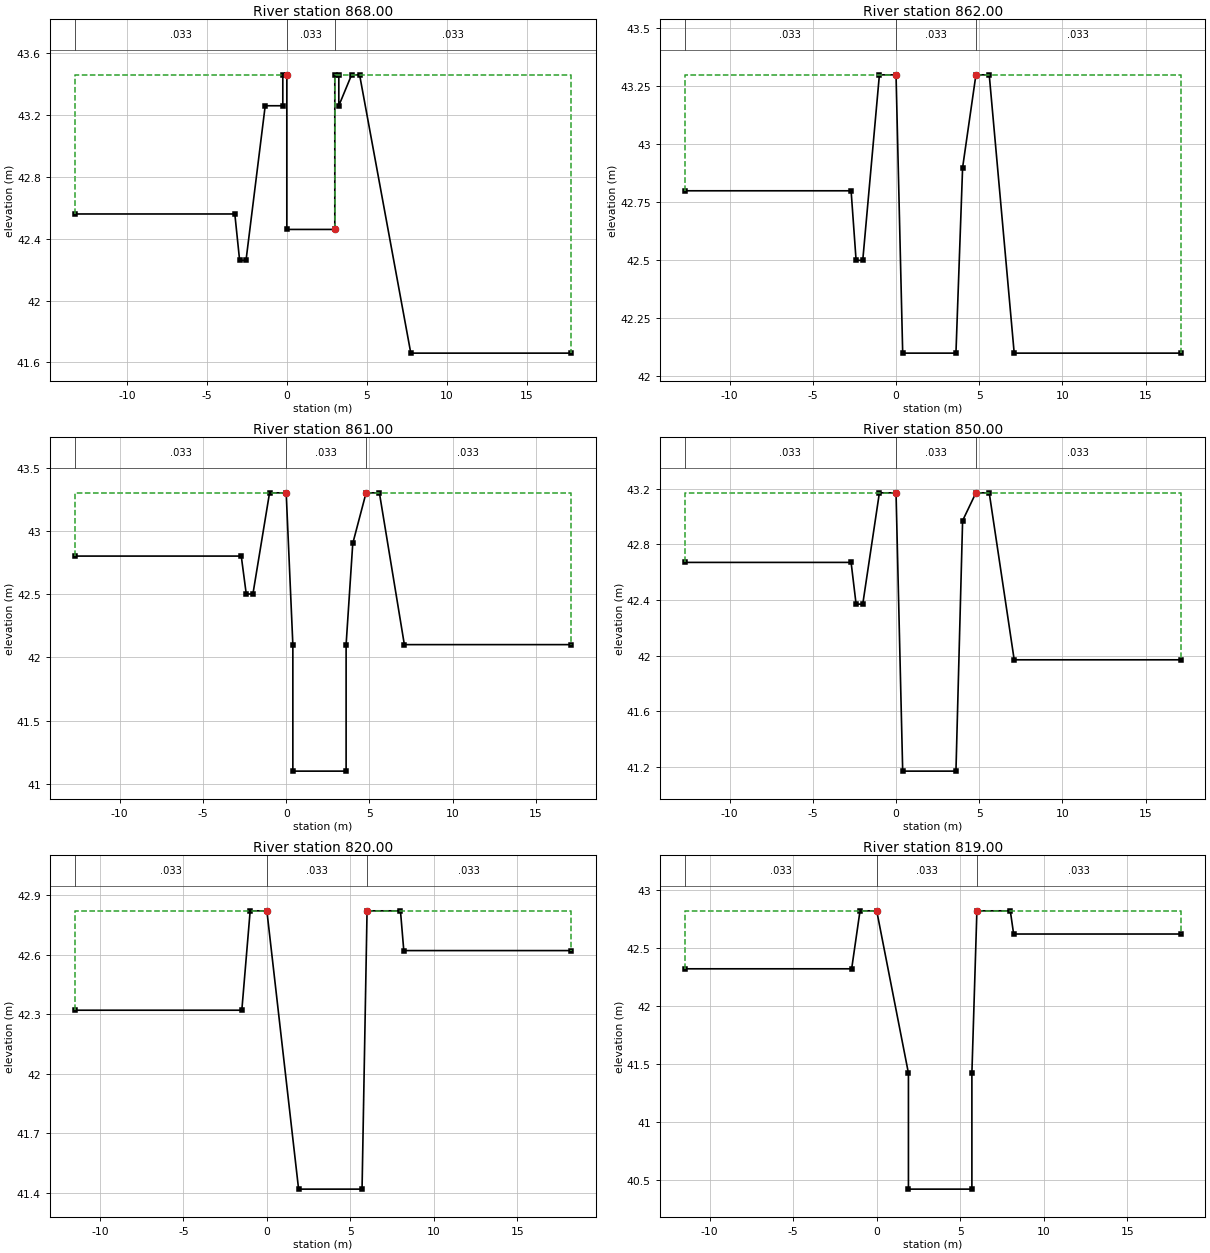
Type RM Length L Ch R = 1 ,868.00  ,6,6,6
BEGIN DESCRIPTION:
17.018
END DESCRIPTION:
#Sta/Elev= 17
  -13.25   42.56   -3.25   42.56   -2.95   42.26   -2.55   42.26   -1.35   43.26
    -.25   43.26    -.25   43.46       0   43.46       0   42.46       3   42.46
       3   43.46    3.25   43.46    3.25   43.26    4.05   43.46    4.55   43.46
    7.75   41.66   17.75   41.66
#Mann= 3 , 0 , 0
  -13.25    .033       0       0    .033       0       3    .033       0
#XS Ineff= 2 , 0
               0   43.46       3           43.46
Permanent Ineff=
       F       F
Bank Sta=0,3
XS Rating Curve= 0
Exp/Cntr=.3,.1

Type RM Length L Ch R = 1 ,862.00  ,1,1,1
BEGIN DESCRIPTION:
17.012
END DESCRIPTION:
#Sta/Elev= 13
   -12.7    42.8    -2.7    42.8    -2.4    42.5      -2    42.5      -1    43.3
       0    43.3      .4    42.1     3.6    42.1       4    42.9     4.8    43.3
     5.6    43.3     7.1    42.1    17.1    42.1
#Mann= 3 , 0 , 0
   -12.7    .033       0       0    .033       0     4.8    .033       0
#XS Ineff= 2 , 0
               0    43.3     4.8            43.3
Permanent Ineff=
       F       F
Bank Sta=0,4.8
XS Rating Curve= 0
Exp/Cntr=.3,.1

Type RM Length L Ch R = 1 ,861.00  ,11,11,11
BEGIN DESCRIPTION:
17.011
END DESCRIPTION:
#Sta/Elev= 15
   -12.7    42.8    -2.7    42.8    -2.4    42.5      -2    42.5      -1    43.3
       0    43.3      .4    42.1      .4    41.1     3.6    41.1     3.6    42.1
       4    42.9     4.8    43.3     5.6    43.3     7.1    42.1    17.1    42.1
#Mann= 3 , 0 , 0
   -12.7    .033       0       0    .033       0     4.8    .033       0
#XS Ineff= 2 , 0
               0    43.3     4.8            43.3
Permanent Ineff=
       F       F
Bank Sta=0,4.8
XS Rating Curve= 0
Exp/Cntr=.3,.1

Type RM Length L Ch R = 1 ,850.00  ,30,30,30
BEGIN DESCRIPTION:
17
END DESCRIPTION:
#Sta/Elev= 13
   -12.7   42.67    -2.7   42.67    -2.4   42.37      -2   42.37      -1   43.17
       0   43.17      .4   41.17     3.6   41.17       4   42.97     4.8   43.17
     5.6   43.17     7.1   41.97    17.1   41.97
#Mann= 3 , 0 , 0
   -12.7    .033       0       0    .033       0     4.8    .033       0
#XS Ineff= 2 , 0
               0   43.17     4.8           43.17
Permanent Ineff=
       F       F
Bank Sta=0,4.8
XS Rating Curve= 0
Exp/Cntr=.3,.1

Type RM Length L Ch R = 1 ,820.00  ,1,1,1
BEGIN DESCRIPTION:
16.02
END DESCRIPTION:
#Sta/Elev= 10
   -11.5   42.32    -1.5   42.32      -1   42.82       0   42.82     1.9   41.42
     5.7   41.42       6   42.82       8   42.82     8.2   42.62    18.2   42.62
#Mann= 3 , 0 , 0
   -11.5    .033       0       0    .033       0       6    .033       0
#XS Ineff= 2 , 0
               0   42.82       6           42.82
Permanent Ineff=
       F       F
Bank Sta=0,6
XS Rating Curve= 0
Exp/Cntr=.3,.1

Type RM Length L Ch R = 1 ,819.00  ,19,19,19
BEGIN DESCRIPTION:
16.019
END DESCRIPTION:
#Sta/Elev= 12
   -11.5   42.32    -1.5   42.32      -1   42.82       0   42.82     1.9   41.42
     1.9   40.42     5.7   40.42     5.7   41.42       6   42.82       8   42.82
     8.2   42.62    18.2   42.62
#Mann= 3 , 0 , 0
   -11.5    .033       0       0    .033       0       6    .033       0
#XS Ineff= 2 , 0
               0   42.82       6           42.82
Permanent Ineff=
       F       F
Bank Sta=0,6
XS Rating Curve= 0
Exp/Cntr=.3,.1

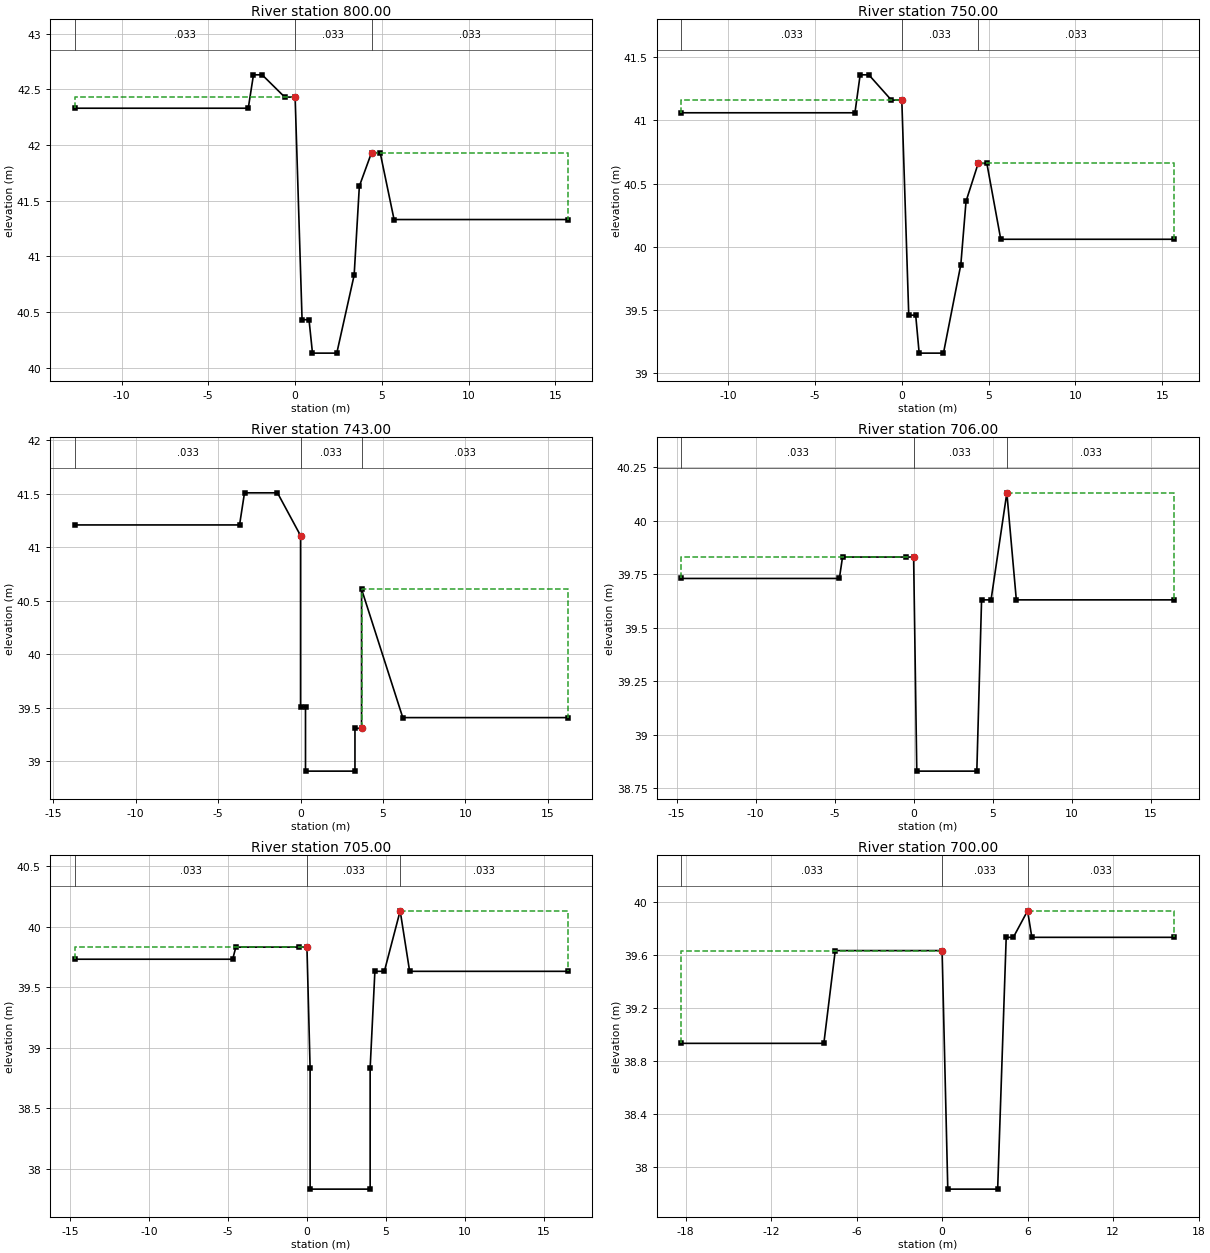
Type RM Length L Ch R = 1 ,800.00  ,50,50,50
BEGIN DESCRIPTION:
16
END DESCRIPTION:
#Sta/Elev= 16
   -12.7   42.33    -2.7   42.33    -2.4   42.63    -1.9   42.63     -.6   42.43
       0   42.43      .4   40.43      .8   40.43       1   40.13     2.4   40.13
     3.4   40.83     3.7   41.63     4.4   41.93     4.9   41.93     5.7   41.33
    15.7   41.33
#Mann= 3 , 0 , 0
   -12.7    .033       0       0    .033       0     4.4    .033       0
#XS Ineff= 2 , 0
               0   42.43     4.4           41.93
Permanent Ineff=
       F       F
Bank Sta=0,4.4
XS Rating Curve= 0
Exp/Cntr=.3,.1

Type RM Length L Ch R = 1 ,750.00  ,7,7,7
BEGIN DESCRIPTION:
15
END DESCRIPTION:
#Sta/Elev= 16
   -12.7   41.06    -2.7   41.06    -2.4   41.36    -1.9   41.36     -.6   41.16
       0   41.16      .4   39.46      .8   39.46       1   39.16     2.4   39.16
     3.4   39.86     3.7   40.36     4.4   40.66     4.9   40.66     5.7   40.06
    15.7   40.06
#Mann= 3 , 0 , 0
   -12.7    .033       0       0    .033       0     4.4    .033       0
#XS Ineff= 2 , 0
               0   41.16     4.4           40.66
Permanent Ineff=
       F       F
Bank Sta=0,4.4
XS Rating Curve= 0
Exp/Cntr=.3,.1

Type RM Length L Ch R = 1 ,743.00  ,37,37,37
BEGIN DESCRIPTION:
14.043
END DESCRIPTION:
#Sta/Elev= 14
   -13.7   41.21    -3.7   41.21    -3.4   41.51    -1.4   41.51       0   41.11
       0   39.51      .3   39.51      .3   38.91     3.3   38.91     3.3   39.31
     3.7   39.31     3.7   40.61     6.2   39.41    16.2   39.41
#Mann= 3 , 0 , 0
   -13.7    .033       0       0    .033       0     3.7    .033       0
#XS Ineff= 2 , 0
               0   41.11     3.7           40.61
Permanent Ineff=
       F       F
Bank Sta=0,3.7
XS Rating Curve= 0
Exp/Cntr=.3,.1

Type RM Length L Ch R = 1 ,706.00  ,1,1,1
BEGIN DESCRIPTION:
14.006
END DESCRIPTION:
#Sta/Elev= 12
   -14.7   39.73    -4.7   39.73    -4.5   39.83     -.5   39.83       0   39.83
      .2   38.83       4   38.83     4.3   39.63     4.9   39.63     5.9   40.13
     6.5   39.63    16.5   39.63
#Mann= 3 , 0 , 0
   -14.7    .033       0       0    .033       0     5.9    .033       0
#XS Ineff= 2 , 0
               0   39.83     5.9           40.13
Permanent Ineff=
       F       F
Bank Sta=0,5.9
XS Rating Curve= 0
Exp/Cntr=.3,.1

Type RM Length L Ch R = 1 ,705.00  ,5,5,5
BEGIN DESCRIPTION:
14.005
END DESCRIPTION:
#Sta/Elev= 14
   -14.7   39.73    -4.7   39.73    -4.5   39.83     -.5   39.83       0   39.83
      .2   38.83      .2   37.83       4   37.83       4   38.83     4.3   39.63
     4.9   39.63     5.9   40.13     6.5   39.63    16.5   39.63
#Mann= 3 , 0 , 0
   -14.7    .033       0       0    .033       0     5.9    .033       0
#XS Ineff= 2 , 0
               0   39.83     5.9           40.13
Permanent Ineff=
       F       F
Bank Sta=0,5.9
XS Rating Curve= 0
Exp/Cntr=.3,.1

Type RM Length L Ch R = 1 ,700.00  ,30,30,30
BEGIN DESCRIPTION:
14
END DESCRIPTION:
#Sta/Elev= 11
   -18.3   38.93    -8.3   38.93    -7.5   39.63       0   39.63      .4   37.83
     3.9   37.83     4.5   39.73       5   39.73       6   39.93     6.3   39.73
    16.3   39.73
#Mann= 3 , 0 , 0
   -18.3    .033       0       0    .033       0       6    .033       0
#XS Ineff= 2 , 0
               0   39.63       6           39.93
Permanent Ineff=
       F       F
Bank Sta=0,6
XS Rating Curve= 0
Exp/Cntr=.3,.1

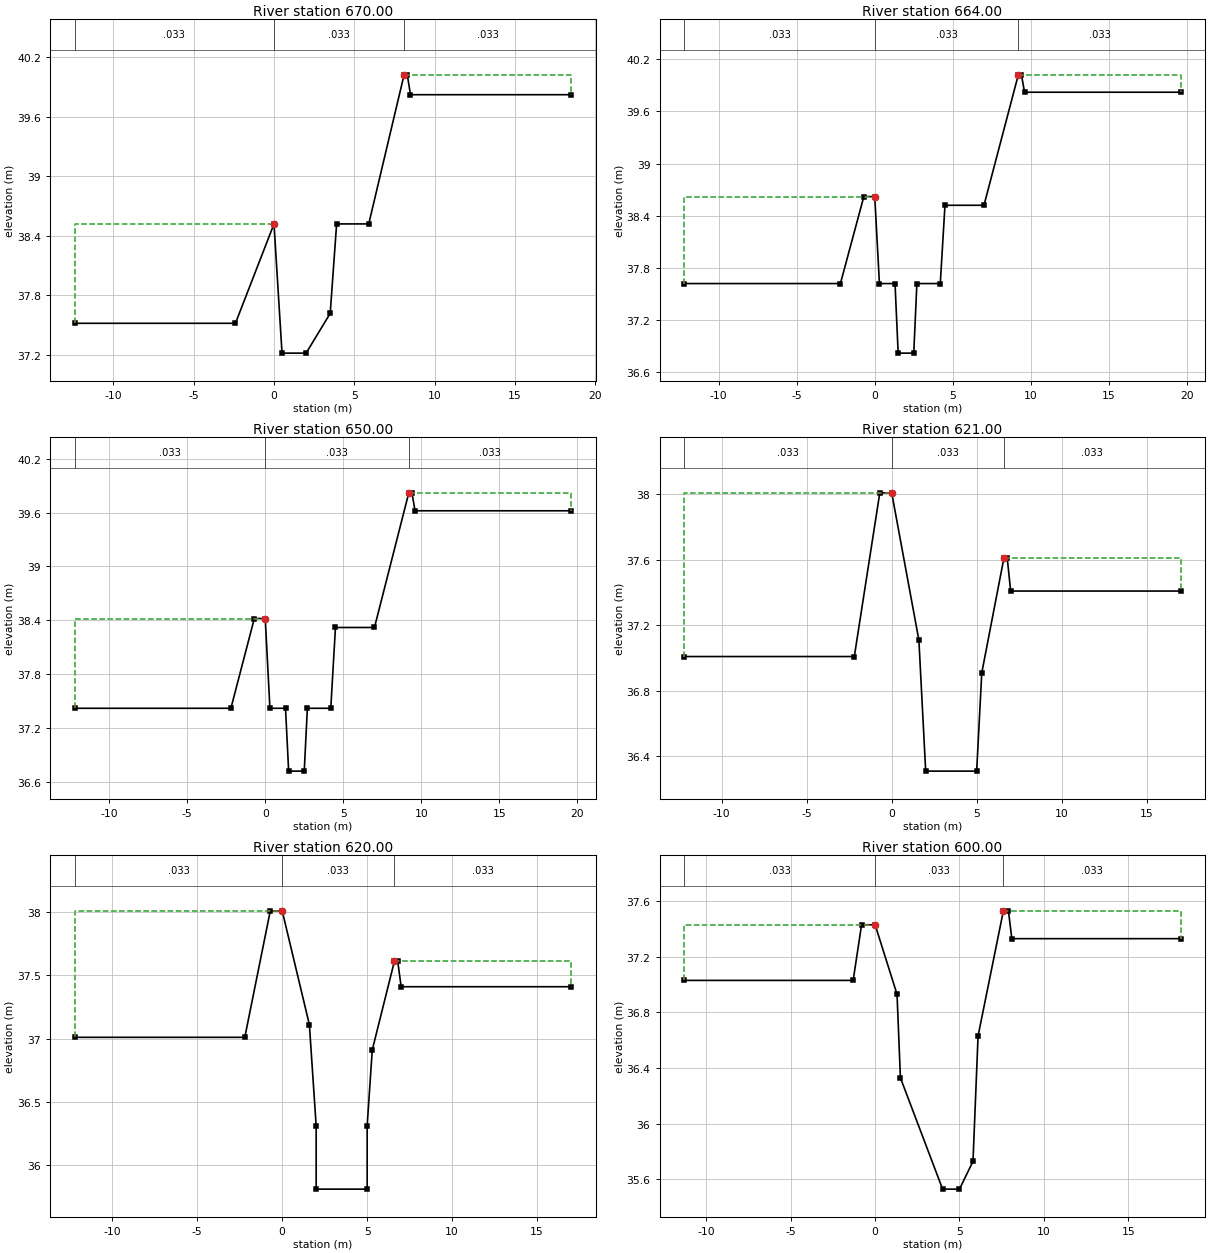
Type RM Length L Ch R = 1 ,670.00  ,6,6,6
BEGIN DESCRIPTION:
13.02
END DESCRIPTION:
#Sta/Elev= 12
   -12.4   37.52    -2.4   37.52       0   38.52      .5   37.22       2   37.22
     3.5   37.62     3.9   38.52     5.9   38.52     8.1   40.02     8.3   40.02
     8.5   39.82    18.5   39.82
#Mann= 3 , 0 , 0
   -12.4    .033       0       0    .033       0     8.1    .033       0
#XS Ineff= 2 , 0
               0   38.52     8.1           40.02
Permanent Ineff=
       F       F
Bank Sta=0,8.1
XS Rating Curve= 0
Exp/Cntr=.3,.1

Type RM Length L Ch R = 1 ,664.00  ,14,14,14
BEGIN DESCRIPTION:
13.014
END DESCRIPTION:
#Sta/Elev= 16
   -12.2   37.62    -2.2   37.62     -.7   38.62       0   38.62      .3   37.62
     1.3   37.62     1.5   36.82     2.5   36.82     2.7   37.62     4.2   37.62
     4.5   38.52       7   38.52     9.2   40.02     9.4   40.02     9.6   39.82
    19.6   39.82
#Mann= 3 , 0 , 0
   -12.2    .033       0       0    .033       0     9.2    .033       0
#XS Ineff= 2 , 0
               0   38.62     9.2           40.02
Permanent Ineff=
       F       F
Bank Sta=0,9.2
XS Rating Curve= 0
Exp/Cntr=.3,.1

Type RM Length L Ch R = 1 ,650.00  ,29,29,29
BEGIN DESCRIPTION:
13
END DESCRIPTION:
#Sta/Elev= 16
   -12.2   37.42    -2.2   37.42     -.7   38.42       0   38.42      .3   37.42
     1.3   37.42     1.5   36.72     2.5   36.72     2.7   37.42     4.2   37.42
     4.5   38.32       7   38.32     9.2   39.82     9.4   39.82     9.6   39.62
    19.6   39.62
#Mann= 3 , 0 , 0
   -12.2    .033       0       0    .033       0     9.2    .033       0
#XS Ineff= 2 , 0
               0   38.42     9.2           39.82
Permanent Ineff=
       F       F
Bank Sta=0,9.2
XS Rating Curve= 0
Exp/Cntr=.3,.1

Type RM Length L Ch R = 1 ,621.00  ,1,1,1
BEGIN DESCRIPTION:
12.021
END DESCRIPTION:
#Sta/Elev= 12
   -12.2   37.01    -2.2   37.01     -.7   38.01       0   38.01     1.6   37.11
       2   36.31       5   36.31     5.3   36.91     6.6   37.61     6.8   37.61
       7   37.41      17   37.41
#Mann= 3 , 0 , 0
   -12.2    .033       0       0    .033       0     6.6    .033       0
#XS Ineff= 2 , 0
               0   38.01     6.6           37.61
Permanent Ineff=
       F       F
Bank Sta=0,6.6
XS Rating Curve= 0
Exp/Cntr=.3,.1

Type RM Length L Ch R = 1 ,620.00  ,20,20,20
BEGIN DESCRIPTION:
12.02
END DESCRIPTION:
#Sta/Elev= 14
   -12.2   37.01    -2.2   37.01     -.7   38.01       0   38.01     1.6   37.11
       2   36.31       2   35.81       5   35.81       5   36.31     5.3   36.91
     6.6   37.61     6.8   37.61       7   37.41      17   37.41
#Mann= 3 , 0 , 0
   -12.2    .033       0       0    .033       0     6.6    .033       0
#XS Ineff= 2 , 0
               0   38.01     6.6           37.61
Permanent Ineff=
       F       F
Bank Sta=0,6.6
XS Rating Curve= 0
Exp/Cntr=.3,.1

Type RM Length L Ch R = 1 ,600.00  ,50,50,50
BEGIN DESCRIPTION:
12
END DESCRIPTION:
#Sta/Elev= 14
   -11.3   37.03    -1.3   37.03     -.8   37.43       0   37.43     1.3   36.93
     1.5   36.33       4   35.53       5   35.53     5.8   35.73     6.1   36.63
     7.6   37.53     7.9   37.53     8.1   37.33    18.1   37.33
#Mann= 3 , 0 , 0
   -11.3    .033       0       0    .033       0     7.6    .033       0
#XS Ineff= 2 , 0
               0   37.43     7.6           37.53
Permanent Ineff=
       F       F
Bank Sta=0,7.6
XS Rating Curve= 0
Exp/Cntr=.3,.1

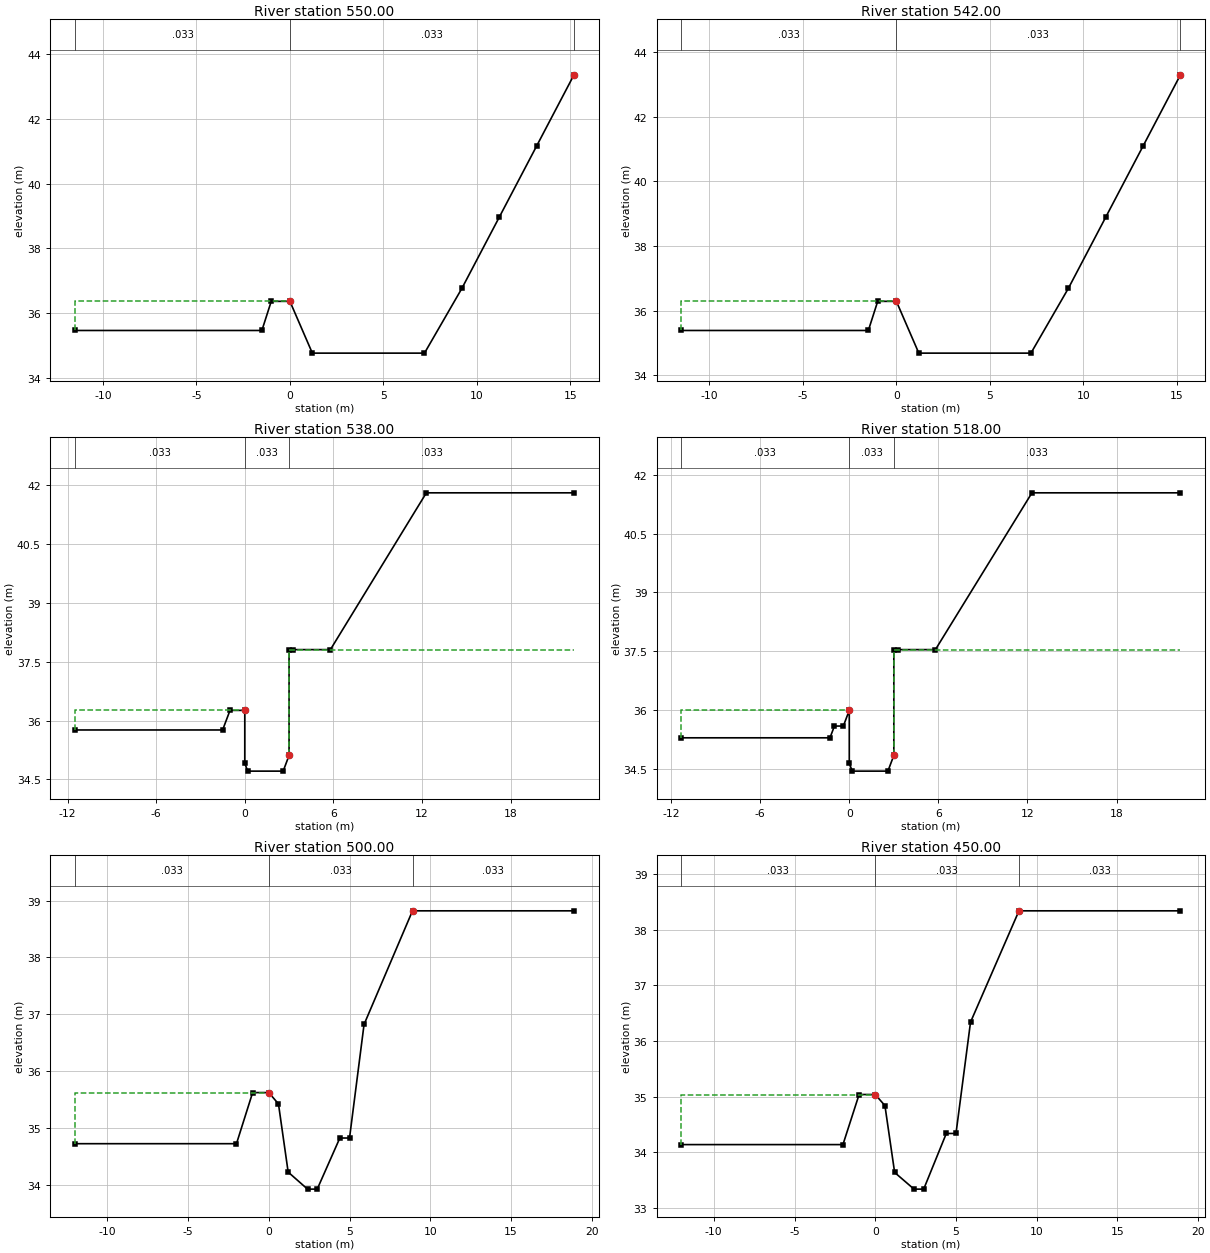
Type RM Length L Ch R = 1 ,550.00  ,8,8,8
BEGIN DESCRIPTION:
11
END DESCRIPTION:
#Sta/Elev= 10
   -11.5   35.46    -1.5   35.46      -1   36.36       0   36.36     1.2   34.76
     7.2   34.76     9.2   36.76    11.2   38.96    13.2   41.16    15.2   43.36
#Mann= 3 , 0 , 0
   -11.5    .033       0       0    .033       0    15.2    .033       0
#XS Ineff= 2 , 0
               0   36.36    15.2           43.36
Permanent Ineff=
       F       F
Bank Sta=0,15.2
XS Rating Curve= 0
Exp/Cntr=.3,.1

Type RM Length L Ch R = 1 ,542.00  ,4,4,4
BEGIN DESCRIPTION:
10.042
END DESCRIPTION:
#Sta/Elev= 10
   -11.5   35.39    -1.5   35.39      -1   36.29       0   36.29     1.2   34.69
     7.2   34.69     9.2   36.69    11.2   38.89    13.2   41.09    15.2   43.29
#Mann= 3 , 0 , 0
   -11.5    .033       0       0    .033       0    15.2    .033       0
#XS Ineff= 2 , 0
               0   36.29    15.2           43.29
Permanent Ineff=
       F       F
Bank Sta=0,15.2
XS Rating Curve= 0
Exp/Cntr=.3,.1

Type RM Length L Ch R = 1 ,538.00  ,20,20,20
BEGIN DESCRIPTION:
10.038
END DESCRIPTION:
#Sta/Elev= 13
   -11.5   35.76    -1.5   35.76      -1   36.26       0   36.26       0   34.91
      .2   34.71     2.6   34.71       3   35.11       3   37.81     3.3   37.81
     5.8   37.81    12.3   41.81    22.3   41.81
#Mann= 3 , 0 , 0
   -11.5    .033       0       0    .033       0       3    .033       0
#XS Ineff= 2 , 0
               0   36.26       3           37.81
Permanent Ineff=
       F       F
Bank Sta=0,3
XS Rating Curve= 0
Exp/Cntr=.3,.1

Type RM Length L Ch R = 1 ,518.00  ,18,18,18
BEGIN DESCRIPTION:
10.018
END DESCRIPTION:
#Sta/Elev= 14
   -11.3   35.29    -1.3   35.29      -1   35.59     -.4   35.59       0   35.99
       0   34.64      .2   34.44     2.6   34.44       3   34.84       3   37.54
     3.3   37.54     5.8   37.54    12.3   41.54    22.3   41.54
#Mann= 3 , 0 , 0
   -11.3    .033       0       0    .033       0       3    .033       0
#XS Ineff= 2 , 0
               0   35.99       3           37.54
Permanent Ineff=
       F       F
Bank Sta=0,3
XS Rating Curve= 0
Exp/Cntr=.3,.1

Type RM Length L Ch R = 1 ,500.00  ,50,50,50
BEGIN DESCRIPTION:
10
END DESCRIPTION:
#Sta/Elev= 13
     -12   34.72      -2   34.72      -1   35.62       0   35.62      .6   35.42
     1.2   34.22     2.4   33.92       3   33.92     4.4   34.82       5   34.82
     5.9   36.82     8.9   38.82    18.9   38.82
#Mann= 3 , 0 , 0
     -12    .033       0       0    .033       0     8.9    .033       0
#XS Ineff= 2 , 0
               0   35.62     8.9           38.82
Permanent Ineff=
       F       F
Bank Sta=0,8.9
XS Rating Curve= 0
Exp/Cntr=.3,.1

Type RM Length L Ch R = 1 ,450.00  ,15,15,15
BEGIN DESCRIPTION:
9
END DESCRIPTION:
#Sta/Elev= 13
     -12   34.14      -2   34.14      -1   35.04       0   35.04      .6   34.84
     1.2   33.64     2.4   33.34       3   33.34     4.4   34.34       5   34.34
     5.9   36.34     8.9   38.34    18.9   38.34
#Mann= 3 , 0 , 0
     -12    .033       0       0    .033       0     8.9    .033       0
#XS Ineff= 2 , 0
               0   35.04     8.9           38.34
Permanent Ineff=
       F       F
Bank Sta=0,8.9
XS Rating Curve= 0
Exp/Cntr=.3,.1

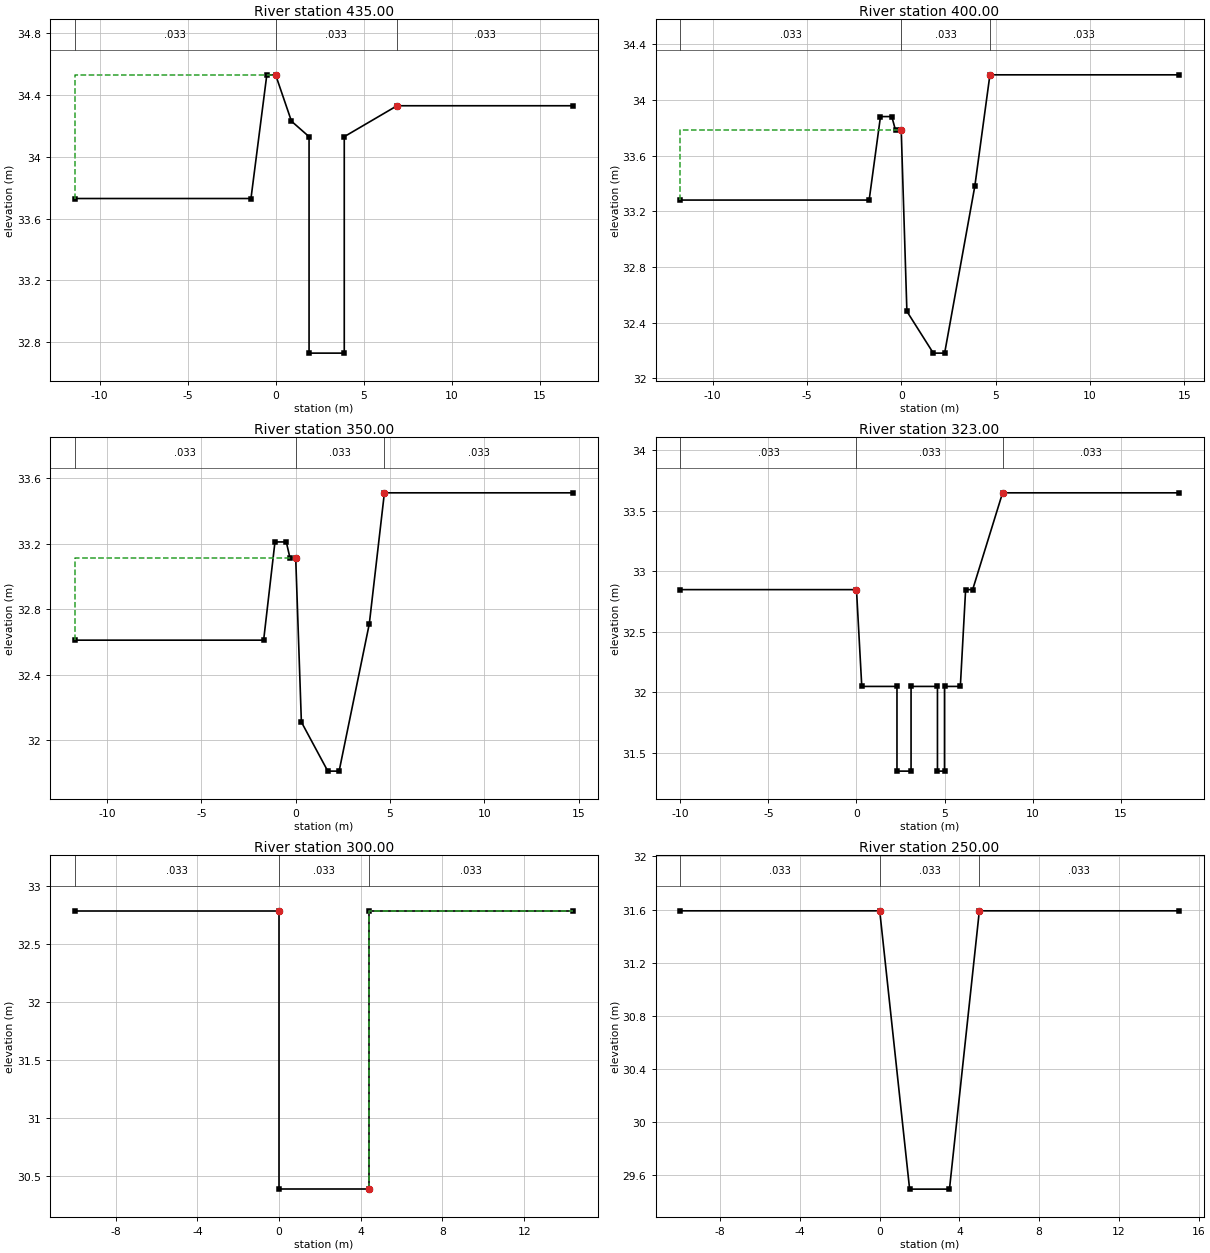
Type RM Length L Ch R = 1 ,435.00  ,35,35,35
BEGIN DESCRIPTION:
8.035
END DESCRIPTION:
#Sta/Elev= 11
   -11.4   33.73    -1.4   33.73     -.5   34.53       0   34.53      .9   34.23
     1.9   34.13     1.9   32.73     3.9   32.73     3.9   34.13     6.9   34.33
    16.9   34.33
#Mann= 3 , 0 , 0
   -11.4    .033       0       0    .033       0     6.9    .033       0
#XS Ineff= 2 , 0
               0   34.53     6.9           34.33
Permanent Ineff=
       F       F
Bank Sta=0,6.9
XS Rating Curve= 0
Exp/Cntr=.3,.1

Type RM Length L Ch R = 1 ,400.00  ,50,50,50
BEGIN DESCRIPTION:
8
END DESCRIPTION:
#Sta/Elev= 12
   -11.7   33.28    -1.7   33.28    -1.1   33.88     -.5   33.88     -.3   33.78
       0   33.78      .3   32.48     1.7   32.18     2.3   32.18     3.9   33.38
     4.7   34.18    14.7   34.18
#Mann= 3 , 0 , 0
   -11.7    .033       0       0    .033       0     4.7    .033       0
#XS Ineff= 2 , 0
               0   33.78     4.7           34.18
Permanent Ineff=
       F       F
Bank Sta=0,4.7
XS Rating Curve= 0
Exp/Cntr=.3,.1

Type RM Length L Ch R = 1 ,350.00  ,27,27,27
BEGIN DESCRIPTION:
7
END DESCRIPTION:
#Sta/Elev= 12
   -11.7   32.61    -1.7   32.61    -1.1   33.21     -.5   33.21     -.3   33.11
       0   33.11      .3   32.11     1.7   31.81     2.3   31.81     3.9   32.71
     4.7   33.51    14.7   33.51
#Mann= 3 , 0 , 0
   -11.7    .033       0       0    .033       0     4.7    .033       0
#XS Ineff= 2 , 0
               0   33.11     4.7           33.51
Permanent Ineff=
       F       F
Bank Sta=0,4.7
XS Rating Curve= 0
Exp/Cntr=.3,.1

Type RM Length L Ch R = 1 ,323.00  ,23,23,23
BEGIN DESCRIPTION:
6.023
END DESCRIPTION:
#Sta/Elev= 16
     -10   32.85       0   32.85      .3   32.05     2.3   32.05     2.3   31.35
     3.1   31.35     3.1   32.05     4.6   32.05     4.6   31.35       5   31.35
       5   32.05     5.9   32.05     6.2   32.85     6.6   32.85     8.3   33.65
    18.3   33.65
#Mann= 3 , 0 , 0
     -10    .033       0       0    .033       0     8.3    .033       0
#XS Ineff= 2 , 0
               0   32.85     8.3           33.65
Permanent Ineff=
       F       F
Bank Sta=0,8.3
XS Rating Curve= 0
Exp/Cntr=.3,.1

Type RM Length L Ch R = 1 ,300.00  ,50,50,50
BEGIN DESCRIPTION:
6
END DESCRIPTION:
#Sta/Elev= 6
     -10   32.79       0   32.79       0   30.39     4.4   30.39     4.4   32.79
    14.4   32.79
#Mann= 3 , 0 , 0
     -10    .033       0       0    .033       0     4.4    .033       0
#XS Ineff= 2 , 0
               0   32.79     4.4           32.79
Permanent Ineff=
       F       F
Bank Sta=0,4.4
XS Rating Curve= 0
Exp/Cntr=.3,.1

Type RM Length L Ch R = 1 ,250.00  ,27,27,27
BEGIN DESCRIPTION:
5
END DESCRIPTION:
#Sta/Elev= 6
     -10   31.59       0   31.59     1.5   29.49     3.5   29.49       5   31.59
      15   31.59
#Mann= 3 , 0 , 0
     -10    .033       0       0    .033       0       5    .033       0
#XS Ineff= 2 , 0
               0   31.59       5           31.59
Permanent Ineff=
       F       F
Bank Sta=0,5
XS Rating Curve= 0
Exp/Cntr=.3,.1

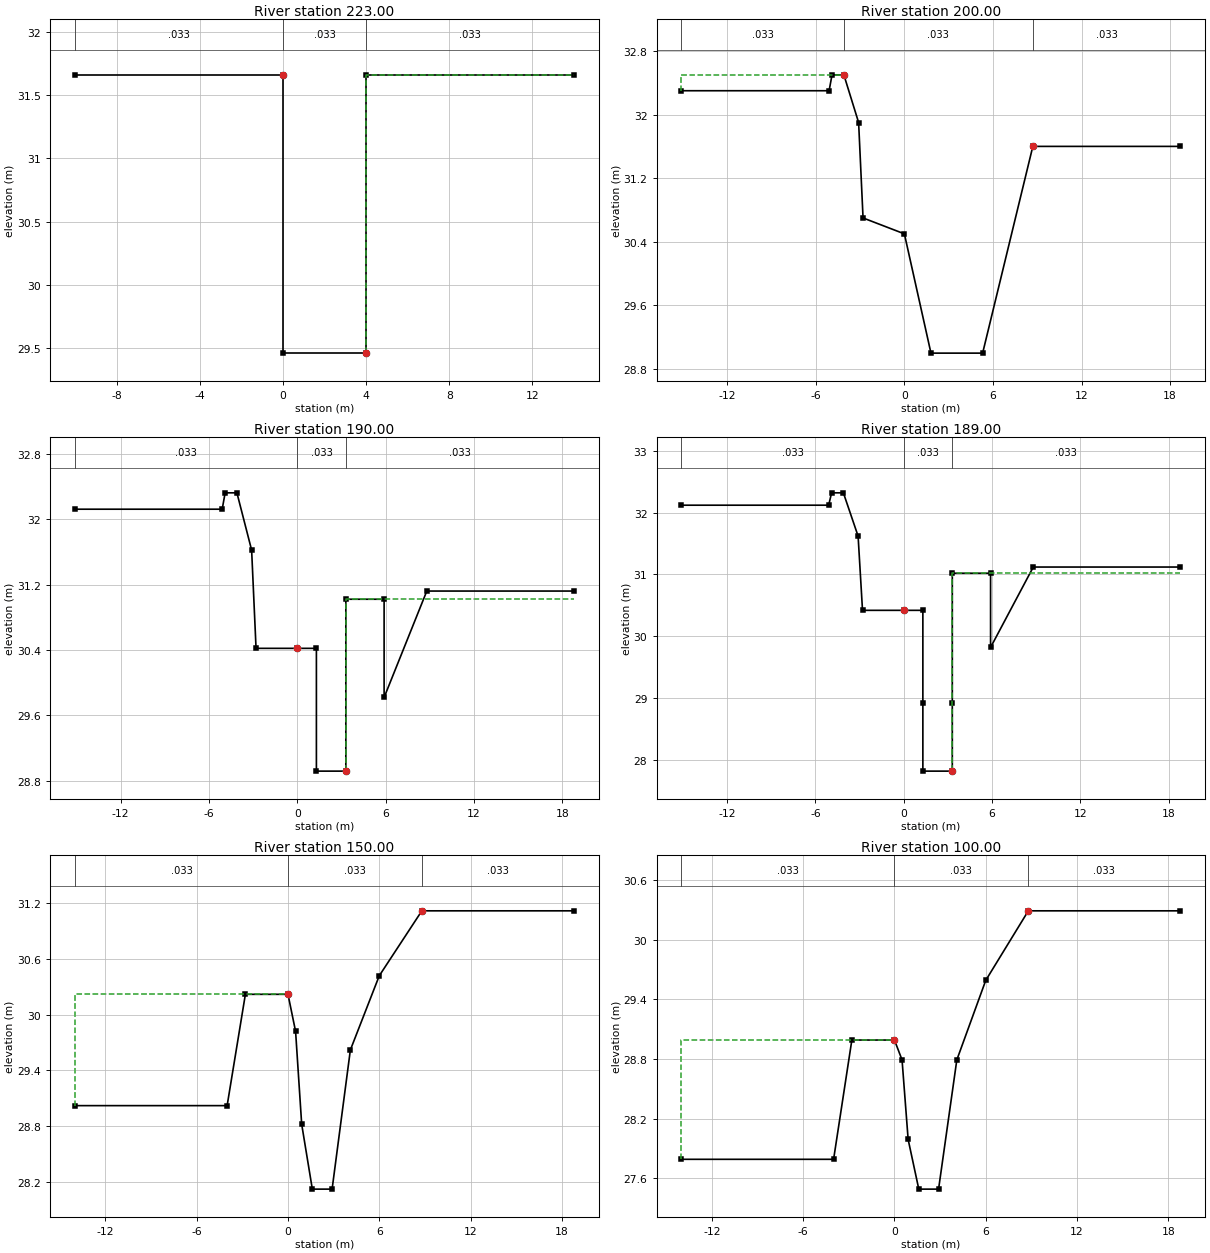
Type RM Length L Ch R = 1 ,223.00  ,23,23,23
BEGIN DESCRIPTION:
4.023
END DESCRIPTION:
#Sta/Elev= 6
     -10   31.66       0   31.66       0   29.46       4   29.46       4   31.66
      14   31.66
#Mann= 3 , 0 , 0
     -10    .033       0       0    .033       0       4    .033       0
#XS Ineff= 2 , 0
               0   31.66       4           31.66
Permanent Ineff=
       F       F
Bank Sta=0,4
XS Rating Curve= 0
Exp/Cntr=.3,.1

Type RM Length L Ch R = 1 ,200.00  ,10,10,10
BEGIN DESCRIPTION:
4
END DESCRIPTION:
#Sta/Elev= 11
   -15.1    32.3    -5.1    32.3    -4.9    32.5    -4.1    32.5    -3.1    31.9
    -2.8    30.7       0    30.5     1.8      29     5.3      29     8.7    31.6
    18.7    31.6
#Mann= 3 , 0 , 0
   -15.1    .033       0    -4.1    .033       0     8.7    .033       0
#XS Ineff= 2 , 0
            -4.1    32.5     8.7            31.6
Permanent Ineff=
       F       F
Bank Sta=-4.1,8.7
XS Rating Curve= 0
Exp/Cntr=.3,.1

Type RM Length L Ch R = 1 ,190.00  ,1,1,1
BEGIN DESCRIPTION:
3.04
END DESCRIPTION:
#Sta/Elev= 15
   -15.1   32.12    -5.1   32.12    -4.9   32.32    -4.1   32.32    -3.1   31.62
    -2.8   30.42       0   30.42     1.3   30.42     1.3   28.92     3.3   28.92
     3.3   31.02     5.9   31.02     5.9   29.82     8.8   31.12    18.8   31.12
#Mann= 3 , 0 , 0
   -15.1    .033       0       0    .033       0     3.3    .033       0
#XS Ineff= 2 , 0
               0   30.42     3.3           31.02
Permanent Ineff=
       F       F
Bank Sta=0,3.3
XS Rating Curve= 0
Exp/Cntr=.3,.1

Type RM Length L Ch R = 1 ,189.00  ,39,39,39
BEGIN DESCRIPTION:
3.039
END DESCRIPTION:
#Sta/Elev= 17
   -15.1   32.12    -5.1   32.12    -4.9   32.32    -4.1   32.32    -3.1   31.62
    -2.8   30.42       0   30.42     1.3   30.42     1.3   28.92     1.3   27.82
     3.3   27.82     3.3   28.92     3.3   31.02     5.9   31.02     5.9   29.82
     8.8   31.12    18.8   31.12
#Mann= 3 , 0 , 0
   -15.1    .033       0       0    .033       0     3.3    .033       0
#XS Ineff= 2 , 0
               0   30.42     3.3           31.02
Permanent Ineff=
       F       F
Bank Sta=0,3.3
XS Rating Curve= 0
Exp/Cntr=.3,.1

Type RM Length L Ch R = 1 ,150.00  ,50,50,50
BEGIN DESCRIPTION:
3
END DESCRIPTION:
#Sta/Elev= 12
     -14   29.02      -4   29.02    -2.8   30.22       0   30.22      .5   29.82
      .9   28.82     1.6   28.12     2.9   28.12     4.1   29.62       6   30.42
     8.8   31.12    18.8   31.12
#Mann= 3 , 0 , 0
     -14    .033       0       0    .033       0     8.8    .033       0
#XS Ineff= 2 , 0
               0   30.22     8.8           31.12
Permanent Ineff=
       F       F
Bank Sta=0,8.8
XS Rating Curve= 0
Exp/Cntr=.3,.1

Type RM Length L Ch R = 1 ,100.00  ,13,13,13
BEGIN DESCRIPTION:
2
END DESCRIPTION:
#Sta/Elev= 12
     -14   27.79      -4   27.79    -2.8   28.99       0   28.99      .5   28.79
      .9   27.99     1.6   27.49     2.9   27.49     4.1   28.79       6   29.59
     8.8   30.29    18.8   30.29
#Mann= 3 , 0 , 0
     -14    .033       0       0    .033       0     8.8    .033       0
#XS Ineff= 2 , 0
               0   28.99     8.8           30.29
Permanent Ineff=
       F       F
Bank Sta=0,8.8
XS Rating Curve= 0
Exp/Cntr=.3,.1

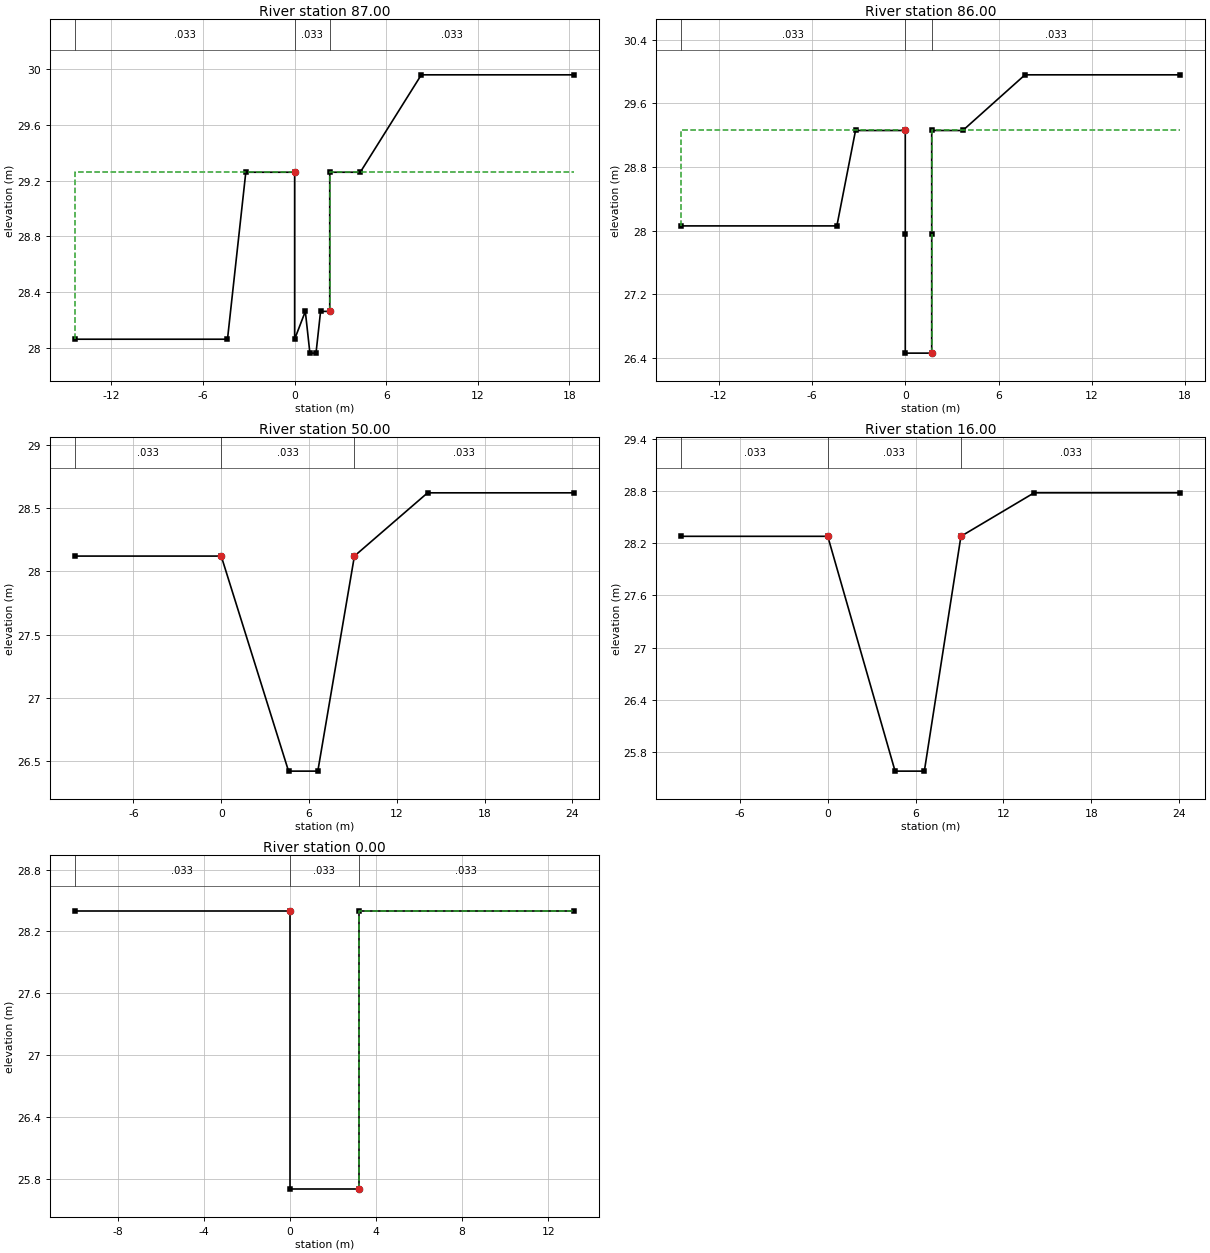
Type RM Length L Ch R = 1 ,87.00   ,1,1,1
BEGIN DESCRIPTION:
1.037
END DESCRIPTION:
#Sta/Elev= 14
   -14.4   28.06    -4.4   28.06    -3.2   29.26       0   29.26       0   28.06
      .7   28.26       1   27.96     1.4   27.96     1.7   28.26     2.3   28.26
     2.3   29.26     4.3   29.26     8.3   29.96    18.3   29.96
#Mann= 3 , 0 , 0
   -14.4    .033       0       0    .033       0     2.3    .033       0
#XS Ineff= 2 , 0
               0   29.26     2.3           29.26
Permanent Ineff=
       F       F
Bank Sta=0,2.3
XS Rating Curve= 0
Exp/Cntr=.3,.1

Type RM Length L Ch R = 1 ,86.00   ,36,36,36
BEGIN DESCRIPTION:
1.036
END DESCRIPTION:
#Sta/Elev= 12
   -14.4   28.06    -4.4   28.06    -3.2   29.26       0   29.26       0   27.96
       0   26.46     1.7   26.46     1.7   27.96     1.7   29.26     3.7   29.26
     7.7   29.96    17.7   29.96
#Mann= 3 , 0 , 0
   -14.4    .033       0       0    .033       0     1.7    .033       0
#XS Ineff= 2 , 0
               0   29.26     1.7           29.26
Permanent Ineff=
       F       F
Bank Sta=0,1.7
XS Rating Curve= 0
Exp/Cntr=.3,.1

Type RM Length L Ch R = 1 ,50.00   ,34,34,34
BEGIN DESCRIPTION:
1
END DESCRIPTION:
#Sta/Elev= 7
     -10   28.12       0   28.12     4.6   26.42     6.6   26.42     9.1   28.12
    14.1   28.62    24.1   28.62
#Mann= 3 , 0 , 0
     -10    .033       0       0    .033       0     9.1    .033       0
#XS Ineff= 2 , 0
               0   28.12     9.1           28.12
Permanent Ineff=
       F       F
Bank Sta=0,9.1
XS Rating Curve= 0
Exp/Cntr=.3,.1

Type RM Length L Ch R = 1 ,16.00   ,16,16,16
BEGIN DESCRIPTION:
0.016
END DESCRIPTION:
#Sta/Elev= 7
     -10   28.28       0   28.28     4.6   25.58     6.6   25.58     9.1   28.28
    14.1   28.78    24.1   28.78
#Mann= 3 , 0 , 0
     -10    .033       0       0    .033       0     9.1    .033       0
#XS Ineff= 2 , 0
               0   28.28     9.1           28.28
Permanent Ineff=
       F       F
Bank Sta=0,9.1
XS Rating Curve= 0
Exp/Cntr=.3,.1

Type RM Length L Ch R = 1 ,0.00    ,0,0,0
BEGIN DESCRIPTION:
0
END DESCRIPTION:
#Sta/Elev= 6
     -10    28.4       0    28.4       0    25.7     3.2    25.7     3.2    28.4
    13.2    28.4
#Mann= 3 , 0 , 0
     -10    .033       0       0    .033       0     3.2    .033       0
#XS Ineff= 2 , 0
               0    28.4     3.2            28.4
Permanent Ineff=
       F       F
Bank Sta=0,3.2
XS Rating Curve= 0
Exp/Cntr=.3,.1

Chan Stop Cuts=-1