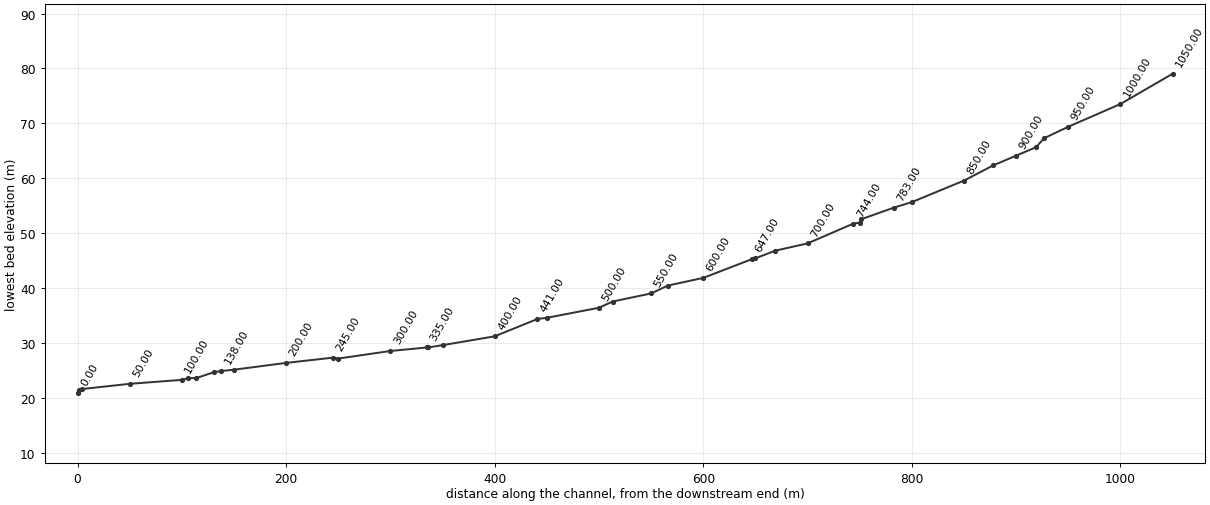
--- DAK.prj (project) ---

Proj Title=DAK
Current Plan=p01
Default Exp/Contr=.3,.1
SI Units
Geom File=g01
Flow File=f01
Plan File=p01
Y Axis Title=Elevation
X Axis Title(PF)=Main Channel Distance
X Axis Title(XS)=Station
BEGIN DESCRIPTION:
           BACK WATER COMPUTATION
      APPLICATION OF HEC-2 BY Samju Construction Engineering
      DAKBATKOL-STREEM : 30 YR
END DESCRIPTION:
DSS Export Rating Curves= 0
DSS Export Rating Curve Sorted= 0
DSS Export Volume Flow Curves= 0
DXF OffsetX= 0
DXF OffsetY= 0
DXF ScaleX= 1
DXF ScaleY= 10

--- DAK.p01 (plan) ---

Plan Title=Imported Plan 01
Version=Version 3.0.1  Mar 2001
Short Identifier=Imported Pla
Geom File=g01
Flow File=f01
Subcritical Flow
K Sum by GR= 0
Std Step Tol= 0.003
Critical Tol= 0.003
Num of Std Step Trials= 20
Max Error Tol= 0.1
Flow Tol Ratio= 0.001
Split Flow NTrial= 30
Split Flow Tol= 0.02
Split Flow Ratio= 0.02
Log Output Level= 0
Friction Slope Method= 1
Unsteady Friction Slope Method= 2
Parabolic Critical Depth
Global Vel Dist= 0 , 0 , 0
Global Log Level= 0
CheckData=True
Encroach Param=-1 ,0,0, 0
Computation Interval=1HOUR
Output Interval=1HOUR
Run HTab= 0
Run UNet= 0
Run PostProcess= 0
UNET Theta= 1
UNET ZTol= 0.02
UNET ZSATol= 0.1
UNET MxIter= 20
UNET MaxInSteps= 20
UNET DtIC= 0
UNET DtMin= 0
UNET MaxCRTS= 20
UNET WFStab= 2
UNET SFStab= 1
UNET WFX= 1
UNET SFX= 1
UNET Convert EG Bridges=-1
UNET Use Existing IB Tables=-1
Instantaneous Interval=1HOUR
Write IC File= 0
Write Velocity= 0
Write Detailed= 0

--- DAK.f01 (steady flow) ---

Flow Title=Imported Flow 01
Version=Version 3.0.1  Mar 2001
Number of Profiles= 5
Profile Names=10YR,20YR,30YR,50YR,80YR
River Rch & RM=RIVER-1,Reach-1         ,1050.00
    6.94    7.65    8.06    8.58    9.05
Boundary for River Rch & Prof#=RIVER-1,Reach-1         , 1
Up Type= 0
Dn Type= 3
Dn Slope=.03
Boundary for River Rch & Prof#=RIVER-1,Reach-1         , 2
Up Type= 0
Dn Type= 3
Dn Slope=.03
Boundary for River Rch & Prof#=RIVER-1,Reach-1         , 3
Up Type= 0
Dn Type= 3
Dn Slope=.03
Boundary for River Rch & Prof#=RIVER-1,Reach-1         , 4
Up Type= 0
Dn Type= 3
Dn Slope=.03
Boundary for River Rch & Prof#=RIVER-1,Reach-1         , 5
Up Type= 0
Dn Type= 3
Dn Slope=.03
DSS Import GetInterval= 0
DSS Import GetPeak= 0
DSS Import FillOption= 0

--- DAK.g01 (geometry) ---

Geom Title=Imported Geom 01
Version=Version 3.0.1  Mar 2001

River Reach=RIVER-1         ,Reach-1
Reach XY= 2
              .5             .95              .5             .05

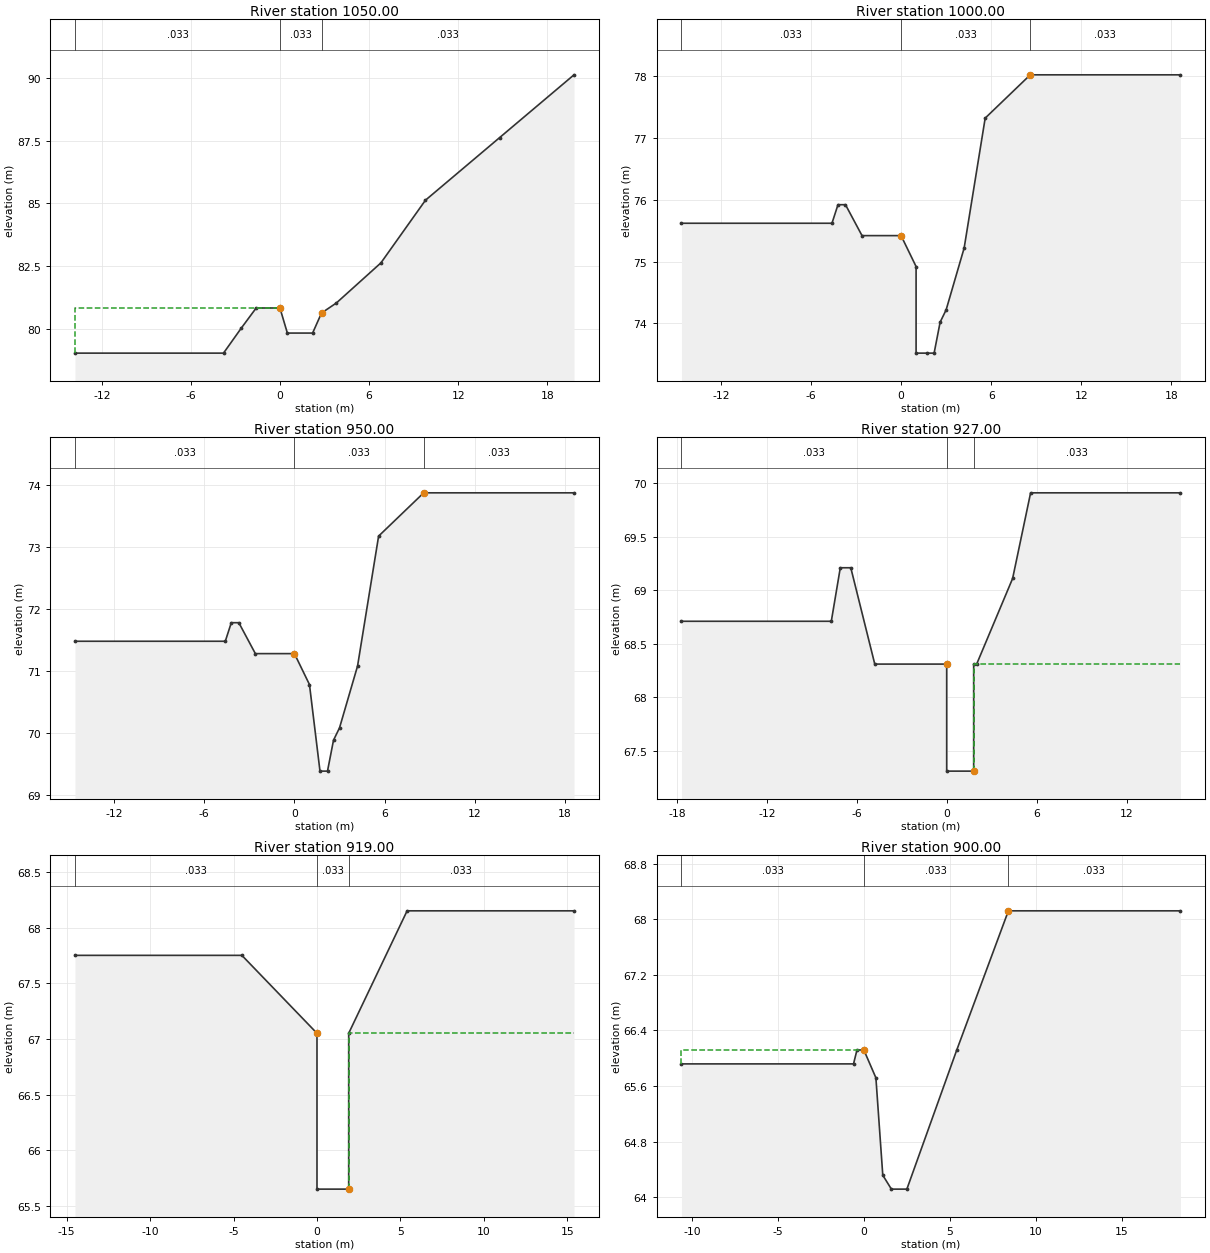
Type RM Length L Ch R = 1 ,1050.00 ,50,50,50
BEGIN DESCRIPTION:
21
END DESCRIPTION:
#Sta/Elev= 13
   -13.8   79.03    -3.8   79.03    -2.6   80.03    -1.6   80.83       0   80.83
      .5   79.83     2.2   79.83     2.8   80.63     3.8   81.03     6.8   82.63
     9.8   85.13    14.8   87.63    19.8   90.13
#Mann= 3 , 0 , 0
   -13.8    .033       0       0    .033       0     2.8    .033       0
#XS Ineff= 2 , 0
               0   80.83     2.8           80.63
Permanent Ineff=
       F       F
Bank Sta=0,2.8
XS Rating Curve= 0
Exp/Cntr=.3,.1

Type RM Length L Ch R = 1 ,1000.00 ,50,50,50
BEGIN DESCRIPTION:
20
END DESCRIPTION:
#Sta/Elev= 16
  -14.62   75.62    -4.6   75.62    -4.2   75.92    -3.7   75.92    -2.6   75.42
       0   75.42       1   74.92       1   73.52     1.7   73.52     2.2   73.52
     2.6   74.02       3   74.22     4.2   75.22     5.6   77.32     8.6   78.02
    18.6   78.02
#Mann= 3 , 0 , 0
  -14.62    .033       0       0    .033       0     8.6    .033       0
#XS Ineff= 2 , 0
               0   75.42     8.6           78.02
Permanent Ineff=
       F       F
Bank Sta=0,8.6
XS Rating Curve= 0
Exp/Cntr=.3,.1

Type RM Length L Ch R = 1 ,950.00  ,23,23,23
BEGIN DESCRIPTION:
19
END DESCRIPTION:
#Sta/Elev= 15
   -14.6   71.48    -4.6   71.48    -4.2   71.78    -3.7   71.78    -2.6   71.28
       0   71.28       1   70.78     1.7   69.38     2.2   69.38     2.6   69.88
       3   70.08     4.2   71.08     5.6   73.18     8.6   73.88    18.6   73.88
#Mann= 3 , 0 , 0
   -14.6    .033       0       0    .033       0     8.6    .033       0
#XS Ineff= 2 , 0
               0   71.28     8.6           73.88
Permanent Ineff=
       F       F
Bank Sta=0,8.6
XS Rating Curve= 0
Exp/Cntr=.3,.1

Type RM Length L Ch R = 1 ,927.00  ,8,8,8
BEGIN DESCRIPTION:
18.027
END DESCRIPTION:
#Sta/Elev= 13
   -17.7   68.71    -7.7   68.71    -7.1   69.21    -6.4   69.21    -4.8   68.31
       0   68.31       0   67.31     1.8   67.31     1.8   68.31       2   68.31
     4.4   69.11     5.6   69.91    15.6   69.91
#Mann= 3 , 0 , 0
   -17.7    .033       0       0    .033       0     1.8    .033       0
#XS Ineff= 2 , 0
               0   68.31     1.8           68.31
Permanent Ineff=
       F       F
Bank Sta=0,1.8
XS Rating Curve= 0
Exp/Cntr=.3,.1

Type RM Length L Ch R = 1 ,919.00  ,19,19,19
BEGIN DESCRIPTION:
18.019
END DESCRIPTION:
#Sta/Elev= 8
   -14.5   67.75    -4.5   67.75       0   67.05       0   65.65     1.9   65.65
     1.9   67.05     5.4   68.15    15.4   68.15
#Mann= 3 , 0 , 0
   -14.5    .033       0       0    .033       0     1.9    .033       0
#XS Ineff= 2 , 0
               0   67.05     1.9           67.05
Permanent Ineff=
       F       F
Bank Sta=0,1.9
XS Rating Curve= 0
Exp/Cntr=.3,.1

Type RM Length L Ch R = 1 ,900.00  ,22,22,22
BEGIN DESCRIPTION:
18
END DESCRIPTION:
#Sta/Elev= 11
   -10.6   65.92     -.6   65.92     -.4   66.12       0   66.12      .7   65.72
     1.1   64.32     1.6   64.12     2.5   64.12     5.4   66.12     8.4   68.12
    18.4   68.12
#Mann= 3 , 0 , 0
   -10.6    .033       0       0    .033       0     8.4    .033       0
#XS Ineff= 2 , 0
               0   66.12     8.4           68.12
Permanent Ineff=
       F       F
Bank Sta=0,8.4
XS Rating Curve= 0
Exp/Cntr=.3,.1

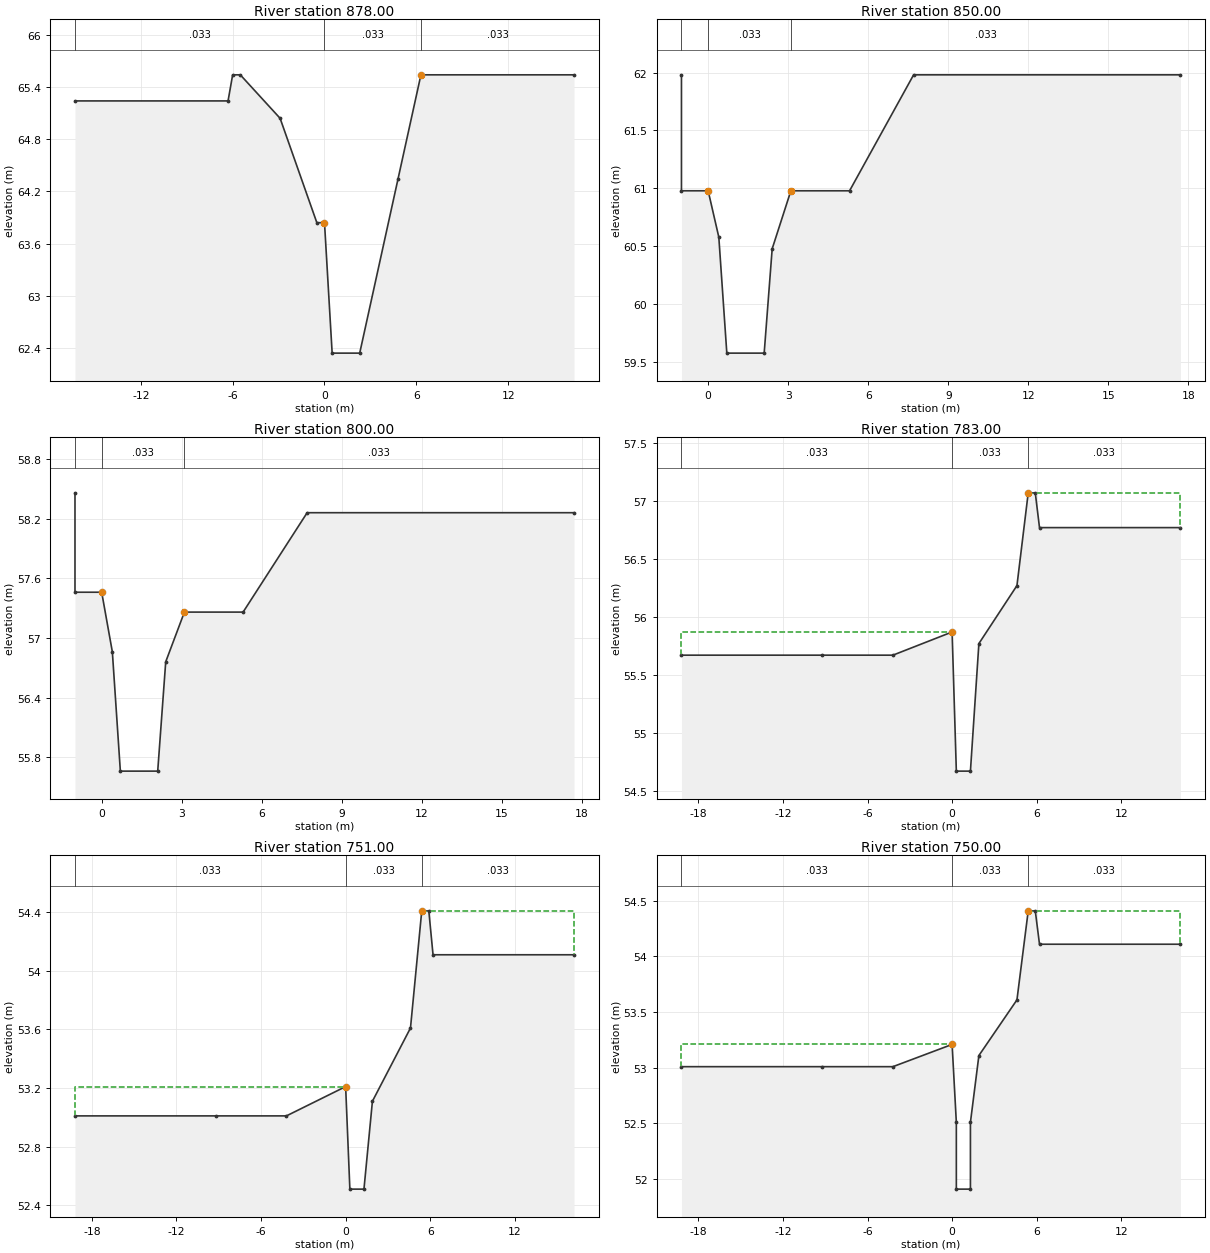
Type RM Length L Ch R = 1 ,878.00  ,28,28,28
BEGIN DESCRIPTION:
17.028
END DESCRIPTION:
#Sta/Elev= 12
   -16.3   65.24    -6.3   65.24      -6   65.54    -5.5   65.54    -2.9   65.04
     -.5   63.84       0   63.84      .5   62.34     2.3   62.34     4.8   64.34
     6.3   65.54    16.3   65.54
#Mann= 3 , 0 , 0
   -16.3    .033       0       0    .033       0     6.3    .033       0
#XS Ineff= 2 , 0
               0   63.84     6.3           65.54
Permanent Ineff=
       F       F
Bank Sta=0,6.3
XS Rating Curve= 0
Exp/Cntr=.3,.1

Type RM Length L Ch R = 1 ,850.00  ,50,50,50
BEGIN DESCRIPTION:
17
END DESCRIPTION:
#Sta/Elev= 11
      -1   61.98      -1   60.98       0   60.98      .4   60.58      .7   59.58
     2.1   59.58     2.4   60.48     3.1   60.98     5.3   60.98     7.7   61.98
    17.7   61.98
#Mann= 3 , 0 , 0
      -1    .033       0       0    .033       0     3.1    .033       0
#XS Ineff= 2 , 0
               0   60.98     3.1           60.98
Permanent Ineff=
       F       F
Bank Sta=0,3.1
XS Rating Curve= 0
Exp/Cntr=.3,.1

Type RM Length L Ch R = 1 ,800.00  ,17,17,17
BEGIN DESCRIPTION:
16
END DESCRIPTION:
#Sta/Elev= 11
      -1   58.46      -1   57.46       0   57.46      .4   56.86      .7   55.66
     2.1   55.66     2.4   56.76     3.1   57.26     5.3   57.26     7.7   58.26
    17.7   58.26
#Mann= 3 , 0 , 0
      -1    .033       0       0    .033       0     3.1    .033       0
#XS Ineff= 2 , 0
               0   57.46     3.1           57.26
Permanent Ineff=
       F       F
Bank Sta=0,3.1
XS Rating Curve= 0
Exp/Cntr=.3,.1

Type RM Length L Ch R = 1 ,783.00  ,32,32,32
BEGIN DESCRIPTION:
15.033
END DESCRIPTION:
#Sta/Elev= 12
   -19.2   55.67    -9.2   55.67    -4.2   55.67       0   55.87      .3   54.67
     1.3   54.67     1.9   55.77     4.6   56.27     5.4   57.07     5.9   57.07
     6.2   56.77    16.2   56.77
#Mann= 3 , 0 , 0
   -19.2    .033       0       0    .033       0     5.4    .033       0
#XS Ineff= 2 , 0
               0   55.87     5.4           57.07
Permanent Ineff=
       F       F
Bank Sta=0,5.4
XS Rating Curve= 0
Exp/Cntr=.3,.1

Type RM Length L Ch R = 1 ,751.00  ,1,1,1
BEGIN DESCRIPTION:
15.001
END DESCRIPTION:
#Sta/Elev= 12
   -19.2   53.01    -9.2   53.01    -4.2   53.01       0   53.21      .3   52.51
     1.3   52.51     1.9   53.11     4.6   53.61     5.4   54.41     5.9   54.41
     6.2   54.11    16.2   54.11
#Mann= 3 , 0 , 0
   -19.2    .033       0       0    .033       0     5.4    .033       0
#XS Ineff= 2 , 0
               0   53.21     5.4           54.41
Permanent Ineff=
       F       F
Bank Sta=0,5.4
XS Rating Curve= 0
Exp/Cntr=.3,.1

Type RM Length L Ch R = 1 ,750.00  ,6,6,6
BEGIN DESCRIPTION:
15
END DESCRIPTION:
#Sta/Elev= 14
   -19.2   53.01    -9.2   53.01    -4.2   53.01       0   53.21      .3   52.51
      .3   51.91     1.3   51.91     1.3   52.51     1.9   53.11     4.6   53.61
     5.4   54.41     5.9   54.41     6.2   54.11    16.2   54.11
#Mann= 3 , 0 , 0
   -19.2    .033       0       0    .033       0     5.4    .033       0
#XS Ineff= 2 , 0
               0   53.21     5.4           54.41
Permanent Ineff=
       F       F
Bank Sta=0,5.4
XS Rating Curve= 0
Exp/Cntr=.3,.1

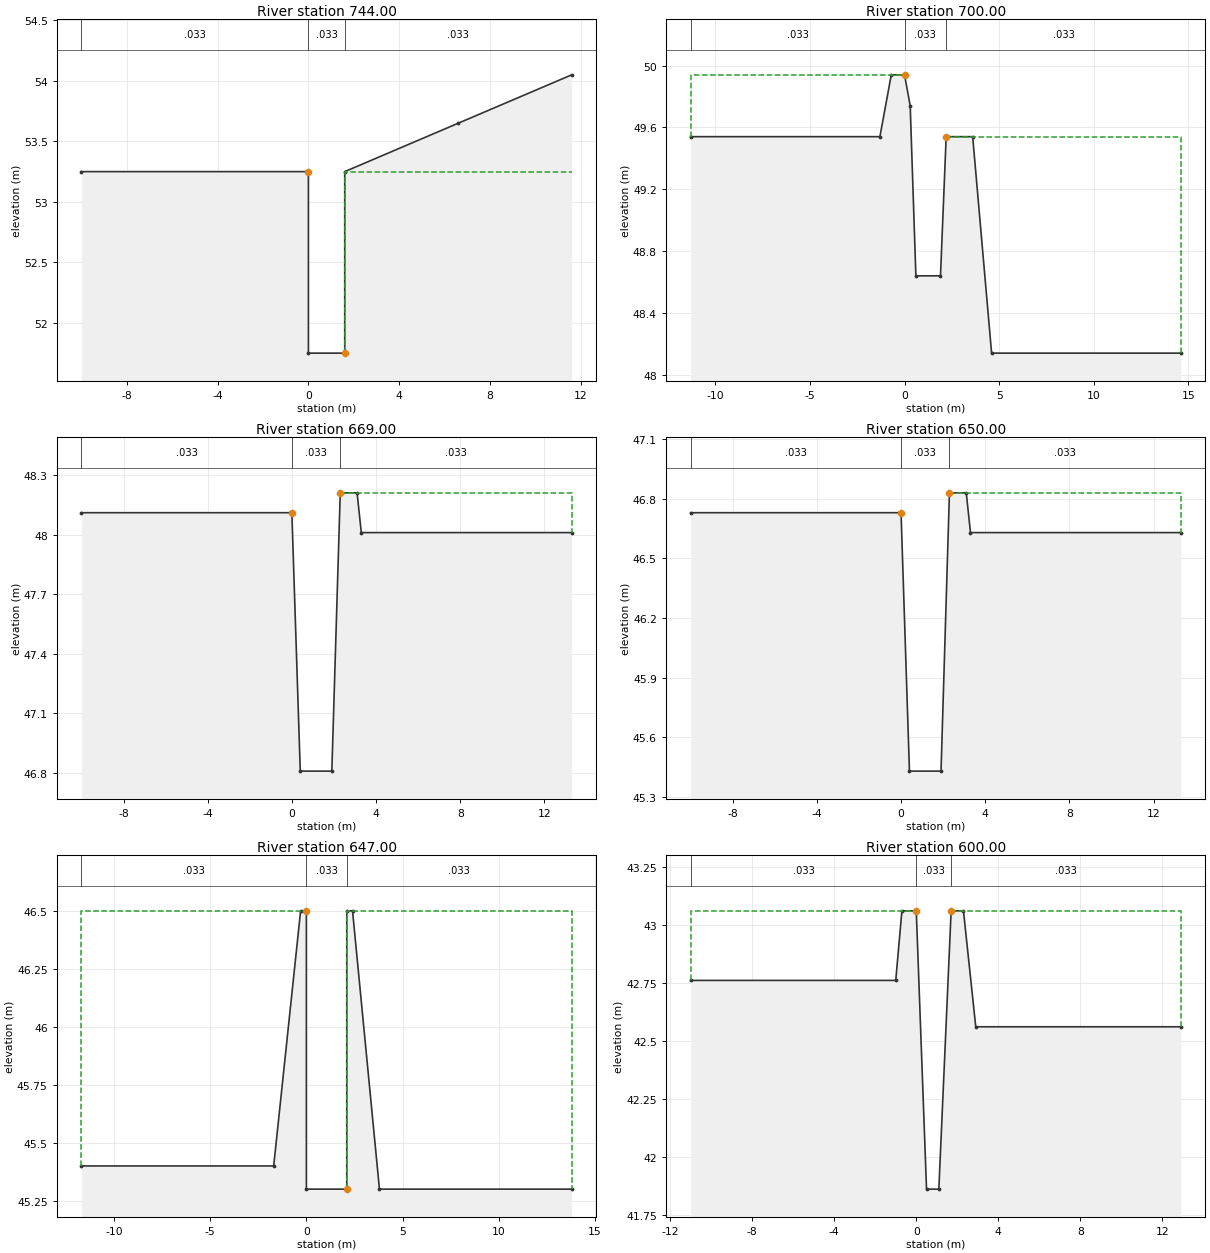
Type RM Length L Ch R = 1 ,744.00  ,44,44,44
BEGIN DESCRIPTION:
14.044
END DESCRIPTION:
#Sta/Elev= 7
     -10   53.25       0   53.25       0   51.75     1.6   51.75     1.6   53.25
     6.6   53.65    11.6   54.05
#Mann= 3 , 0 , 0
     -10    .033       0       0    .033       0     1.6    .033       0
#XS Ineff= 2 , 0
               0   53.25     1.6           53.25
Permanent Ineff=
       F       F
Bank Sta=0,1.6
XS Rating Curve= 0
Exp/Cntr=.3,.1

Type RM Length L Ch R = 1 ,700.00  ,31,31,31
BEGIN DESCRIPTION:
14
END DESCRIPTION:
#Sta/Elev= 11
   -11.3   49.54    -1.3   49.54     -.7   49.94       0   49.94      .3   49.74
      .6   48.64     1.9   48.64     2.2   49.54     3.6   49.54     4.6   48.14
    14.6   48.14
#Mann= 3 , 0 , 0
   -11.3    .033       0       0    .033       0     2.2    .033       0
#XS Ineff= 2 , 0
               0   49.94     2.2           49.54
Permanent Ineff=
       F       F
Bank Sta=0,2.2
XS Rating Curve= 0
Exp/Cntr=.3,.1

Type RM Length L Ch R = 1 ,669.00  ,19,19,19
BEGIN DESCRIPTION:
13.019
END DESCRIPTION:
#Sta/Elev= 8
     -10   48.11       0   48.11      .4   46.81     1.9   46.81     2.3   48.21
     3.1   48.21     3.3   48.01    13.3   48.01
#Mann= 3 , 0 , 0
     -10    .033       0       0    .033       0     2.3    .033       0
#XS Ineff= 2 , 0
               0   48.11     2.3           48.21
Permanent Ineff=
       F       F
Bank Sta=0,2.3
XS Rating Curve= 0
Exp/Cntr=.3,.1

Type RM Length L Ch R = 1 ,650.00  ,3,3,3
BEGIN DESCRIPTION:
13
END DESCRIPTION:
#Sta/Elev= 8
     -10   46.73       0   46.73      .4   45.43     1.9   45.43     2.3   46.83
     3.1   46.83     3.3   46.63    13.3   46.63
#Mann= 3 , 0 , 0
     -10    .033       0       0    .033       0     2.3    .033       0
#XS Ineff= 2 , 0
               0   46.73     2.3           46.83
Permanent Ineff=
       F       F
Bank Sta=0,2.3
XS Rating Curve= 0
Exp/Cntr=.3,.1

Type RM Length L Ch R = 1 ,647.00  ,47,47,47
BEGIN DESCRIPTION:
12.047
END DESCRIPTION:
#Sta/Elev= 10
   -11.7    45.4    -1.7    45.4     -.3    46.5       0    46.5       0    45.3
     2.1    45.3     2.1    46.5     2.4    46.5     3.8    45.3    13.8    45.3
#Mann= 3 , 0 , 0
   -11.7    .033       0       0    .033       0     2.1    .033       0
#XS Ineff= 2 , 0
               0    46.5     2.1            46.5
Permanent Ineff=
       F       F
Bank Sta=0,2.1
XS Rating Curve= 0
Exp/Cntr=.3,.1

Type RM Length L Ch R = 1 ,600.00  ,34,34,34
BEGIN DESCRIPTION:
12
END DESCRIPTION:
#Sta/Elev= 10
     -11   42.76      -1   42.76     -.7   43.06       0   43.06      .5   41.86
     1.1   41.86     1.7   43.06     2.3   43.06     2.9   42.56    12.9   42.56
#Mann= 3 , 0 , 0
     -11    .033       0       0    .033       0     1.7    .033       0
#XS Ineff= 2 , 0
               0   43.06     1.7           43.06
Permanent Ineff=
       F       F
Bank Sta=0,1.7
XS Rating Curve= 0
Exp/Cntr=.3,.1

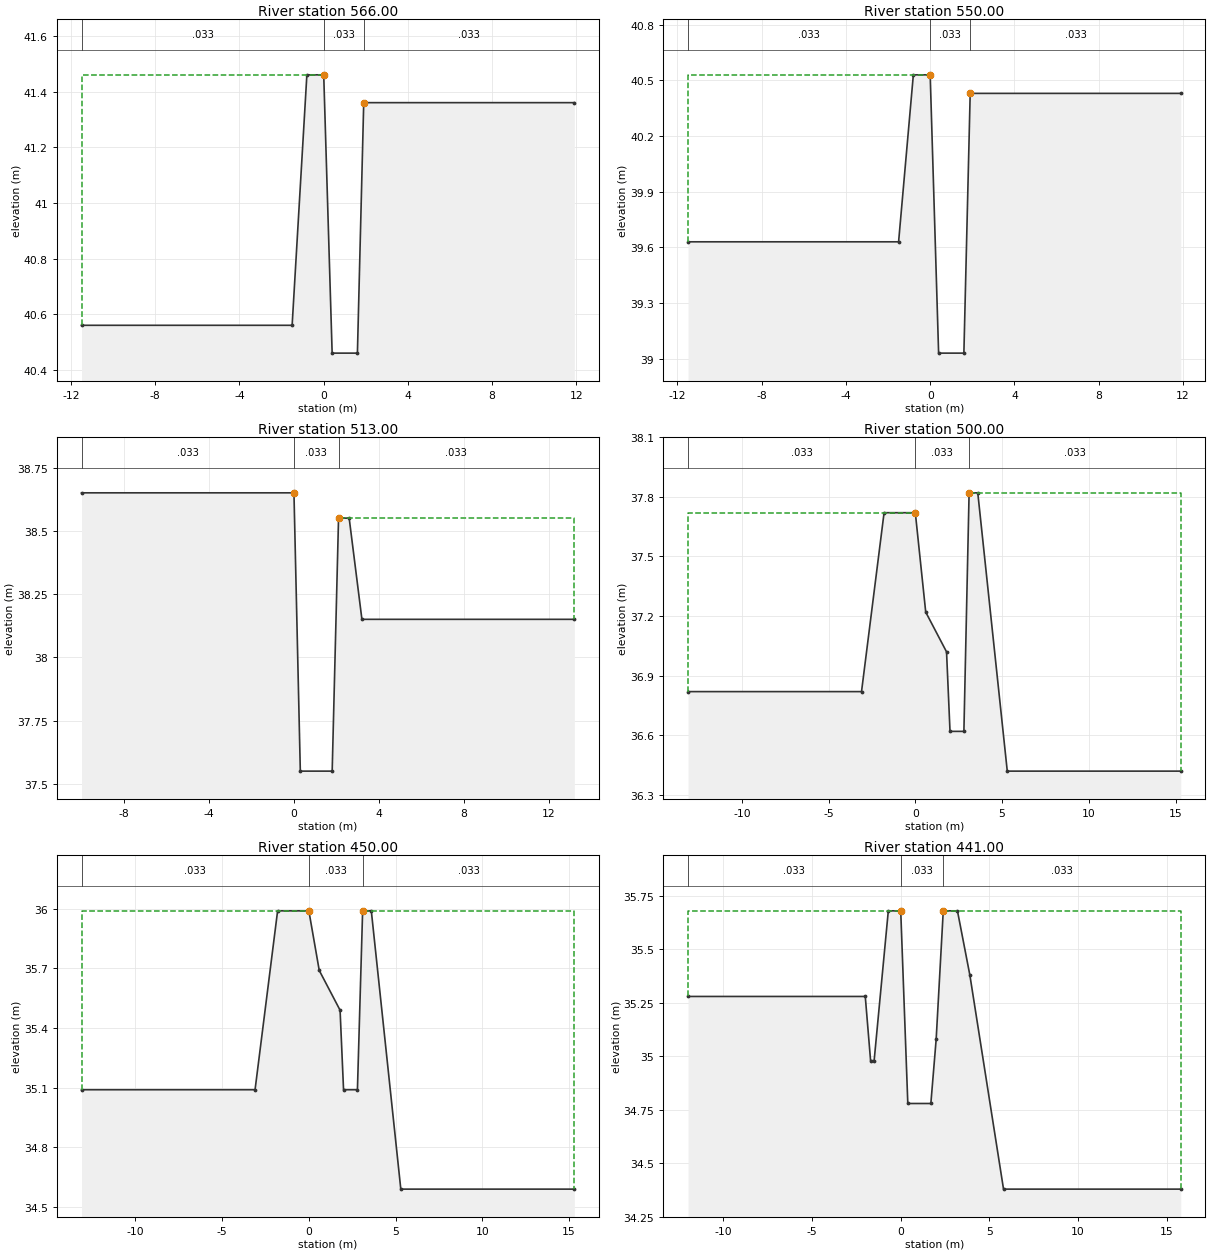
Type RM Length L Ch R = 1 ,566.00  ,16,16,16
BEGIN DESCRIPTION:
11.016
END DESCRIPTION:
#Sta/Elev= 8
   -11.5   40.56    -1.5   40.56     -.8   41.46       0   41.46      .4   40.46
     1.6   40.46     1.9   41.36    11.9   41.36
#Mann= 3 , 0 , 0
   -11.5    .033       0       0    .033       0     1.9    .033       0
#XS Ineff= 2 , 0
               0   41.46     1.9           41.36
Permanent Ineff=
       F       F
Bank Sta=0,1.9
XS Rating Curve= 0
Exp/Cntr=.3,.1

Type RM Length L Ch R = 1 ,550.00  ,37,37,37
BEGIN DESCRIPTION:
11
END DESCRIPTION:
#Sta/Elev= 8
   -11.5   39.63    -1.5   39.63     -.8   40.53       0   40.53      .4   39.03
     1.6   39.03     1.9   40.43    11.9   40.43
#Mann= 3 , 0 , 0
   -11.5    .033       0       0    .033       0     1.9    .033       0
#XS Ineff= 2 , 0
               0   40.53     1.9           40.43
Permanent Ineff=
       F       F
Bank Sta=0,1.9
XS Rating Curve= 0
Exp/Cntr=.3,.1

Type RM Length L Ch R = 1 ,513.00  ,13,13,13
BEGIN DESCRIPTION:
10.013
END DESCRIPTION:
#Sta/Elev= 8
     -10   38.65       0   38.65      .3   37.55     1.8   37.55     2.1   38.55
     2.6   38.55     3.2   38.15    13.2   38.15
#Mann= 3 , 0 , 0
     -10    .033       0       0    .033       0     2.1    .033       0
#XS Ineff= 2 , 0
               0   38.65     2.1           38.55
Permanent Ineff=
       F       F
Bank Sta=0,2.1
XS Rating Curve= 0
Exp/Cntr=.3,.1

Type RM Length L Ch R = 1 ,500.00  ,50,50,50
BEGIN DESCRIPTION:
10
END DESCRIPTION:
#Sta/Elev= 12
   -13.1   36.82    -3.1   36.82    -1.8   37.72       0   37.72      .6   37.22
     1.8   37.02       2   36.62     2.8   36.62     3.1   37.82     3.6   37.82
     5.3   36.42    15.3   36.42
#Mann= 3 , 0 , 0
   -13.1    .033       0       0    .033       0     3.1    .033       0
#XS Ineff= 2 , 0
               0   37.72     3.1           37.82
Permanent Ineff=
       F       F
Bank Sta=0,3.1
XS Rating Curve= 0
Exp/Cntr=.3,.1

Type RM Length L Ch R = 1 ,450.00  ,9,9,9
BEGIN DESCRIPTION:
9
END DESCRIPTION:
#Sta/Elev= 12
   -13.1   35.09    -3.1   35.09    -1.8   35.99       0   35.99      .6   35.69
     1.8   35.49       2   35.09     2.8   35.09     3.1   35.99     3.6   35.99
     5.3   34.59    15.3   34.59
#Mann= 3 , 0 , 0
   -13.1    .033       0       0    .033       0     3.1    .033       0
#XS Ineff= 2 , 0
               0   35.99     3.1           35.99
Permanent Ineff=
       F       F
Bank Sta=0,3.1
XS Rating Curve= 0
Exp/Cntr=.3,.1

Type RM Length L Ch R = 1 ,441.00  ,41,41,41
BEGIN DESCRIPTION:
8.041
END DESCRIPTION:
#Sta/Elev= 14
     -12   35.28      -2   35.28    -1.7   34.98    -1.5   34.98     -.7   35.68
       0   35.68      .4   34.78     1.7   34.78       2   35.08     2.4   35.68
     3.2   35.68     3.9   35.38     5.8   34.38    15.8   34.38
#Mann= 3 , 0 , 0
     -12    .033       0       0    .033       0     2.4    .033       0
#XS Ineff= 2 , 0
               0   35.68     2.4           35.68
Permanent Ineff=
       F       F
Bank Sta=0,2.4
XS Rating Curve= 0
Exp/Cntr=.3,.1

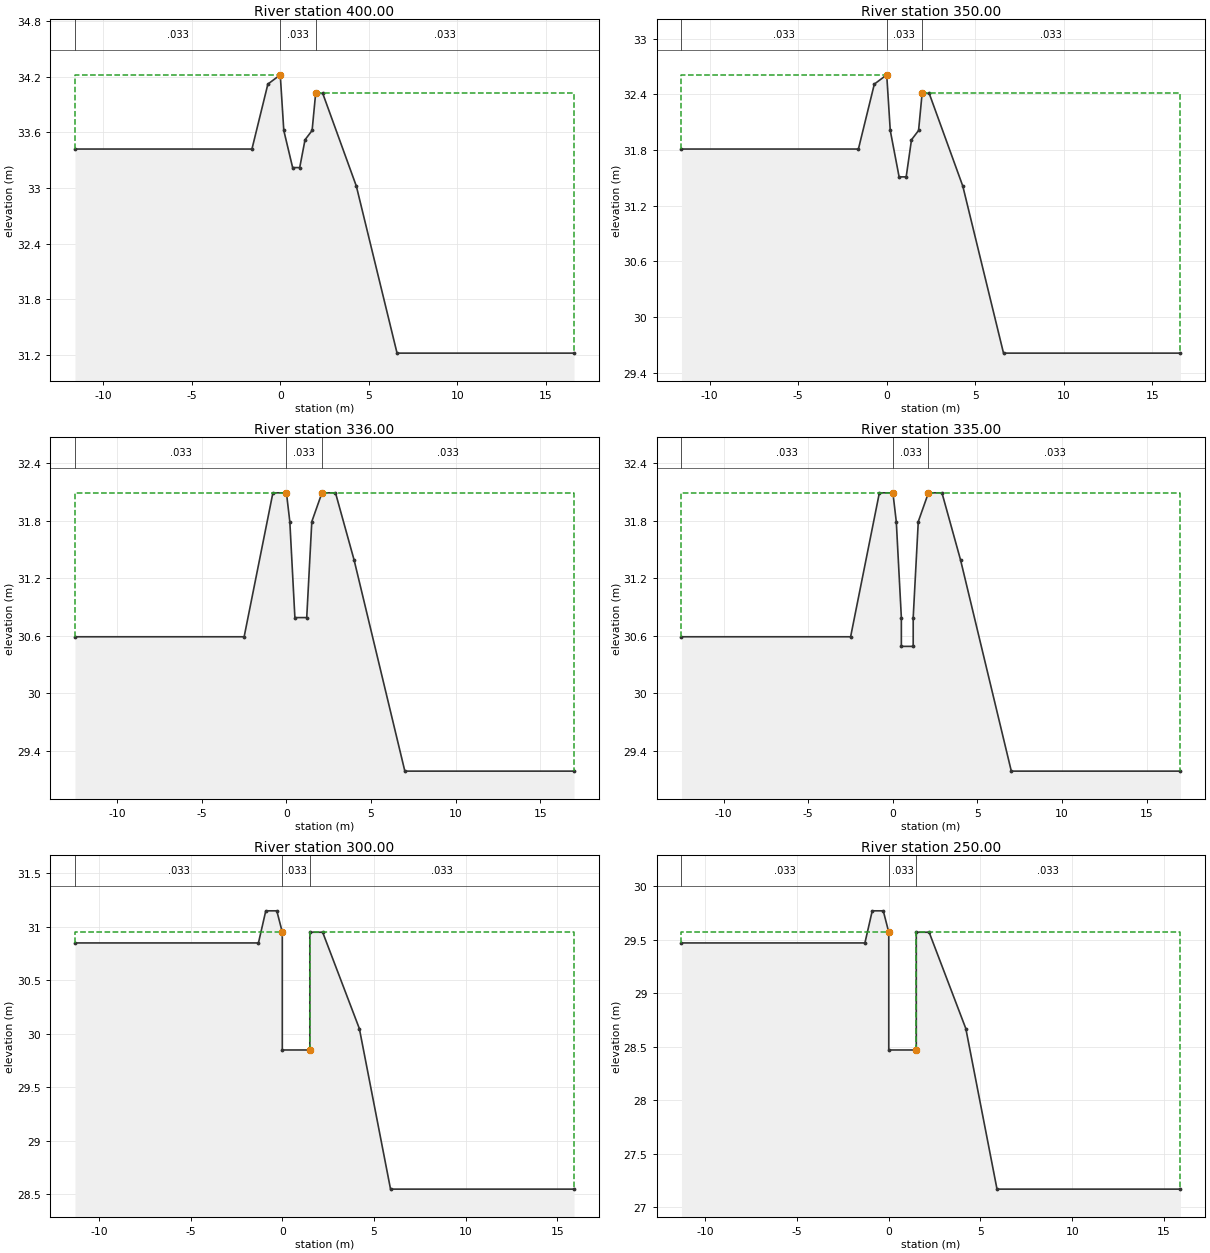
Type RM Length L Ch R = 1 ,400.00  ,50,50,50
BEGIN DESCRIPTION:
8
END DESCRIPTION:
#Sta/Elev= 14
   -11.6   33.42    -1.6   33.42     -.7   34.12       0   34.22      .2   33.62
      .7   33.22     1.1   33.22     1.4   33.52     1.8   33.62       2   34.02
     2.4   34.02     4.3   33.02     6.6   31.22    16.6   31.22
#Mann= 3 , 0 , 0
   -11.6    .033       0       0    .033       0       2    .033       0
#XS Ineff= 2 , 0
               0   34.22       2           34.02
Permanent Ineff=
       F       F
Bank Sta=0,2
XS Rating Curve= 0
Exp/Cntr=.3,.1

Type RM Length L Ch R = 1 ,350.00  ,14,14,14
BEGIN DESCRIPTION:
7
END DESCRIPTION:
#Sta/Elev= 14
   -11.6   31.81    -1.6   31.81     -.7   32.51       0   32.61      .2   32.01
      .7   31.51     1.1   31.51     1.4   31.91     1.8   32.01       2   32.41
     2.4   32.41     4.3   31.41     6.6   29.61    16.6   29.61
#Mann= 3 , 0 , 0
   -11.6    .033       0       0    .033       0       2    .033       0
#XS Ineff= 2 , 0
               0   32.61       2           32.41
Permanent Ineff=
       F       F
Bank Sta=0,2
XS Rating Curve= 0
Exp/Cntr=.3,.1

Type RM Length L Ch R = 1 ,336.00  ,1,1,1
BEGIN DESCRIPTION:
6.036
END DESCRIPTION:
#Sta/Elev= 13
   -12.5   30.59    -2.5   30.59     -.8   32.09       0   32.09      .2   31.79
      .5   30.79     1.2   30.79     1.5   31.79     2.1   32.09     2.9   32.09
       4   31.39       7   29.19      17   29.19
#Mann= 3 , 0 , 0
   -12.5    .033       0       0    .033       0     2.1    .033       0
#XS Ineff= 2 , 0
               0   32.09     2.1           32.09
Permanent Ineff=
       F       F
Bank Sta=0,2.1
XS Rating Curve= 0
Exp/Cntr=.3,.1

Type RM Length L Ch R = 1 ,335.00  ,35,35,35
BEGIN DESCRIPTION:
6.035
END DESCRIPTION:
#Sta/Elev= 15
   -12.5   30.59    -2.5   30.59     -.8   32.09       0   32.09      .2   31.79
      .5   30.79      .5   30.49     1.2   30.49     1.2   30.79     1.5   31.79
     2.1   32.09     2.9   32.09       4   31.39       7   29.19      17   29.19
#Mann= 3 , 0 , 0
   -12.5    .033       0       0    .033       0     2.1    .033       0
#XS Ineff= 2 , 0
               0   32.09     2.1           32.09
Permanent Ineff=
       F       F
Bank Sta=0,2.1
XS Rating Curve= 0
Exp/Cntr=.3,.1

Type RM Length L Ch R = 1 ,300.00  ,50,50,50
BEGIN DESCRIPTION:
6
END DESCRIPTION:
#Sta/Elev= 12
   -11.3   30.85    -1.3   30.85     -.9   31.15     -.3   31.15       0   30.95
       0   29.85     1.5   29.85     1.5   30.95     2.2   30.95     4.2   30.05
     5.9   28.55    15.9   28.55
#Mann= 3 , 0 , 0
   -11.3    .033       0       0    .033       0     1.5    .033       0
#XS Ineff= 2 , 0
               0   30.95     1.5           30.95
Permanent Ineff=
       F       F
Bank Sta=0,1.5
XS Rating Curve= 0
Exp/Cntr=.3,.1

Type RM Length L Ch R = 1 ,250.00  ,5,5,5
BEGIN DESCRIPTION:
5
END DESCRIPTION:
#Sta/Elev= 12
   -11.3   29.47    -1.3   29.47     -.9   29.77     -.3   29.77       0   29.57
       0   28.47     1.5   28.47     1.5   29.57     2.2   29.57     4.2   28.67
     5.9   27.17    15.9   27.17
#Mann= 3 , 0 , 0
   -11.3    .033       0       0    .033       0     1.5    .033       0
#XS Ineff= 2 , 0
               0   29.57     1.5           29.57
Permanent Ineff=
       F       F
Bank Sta=0,1.5
XS Rating Curve= 0
Exp/Cntr=.3,.1

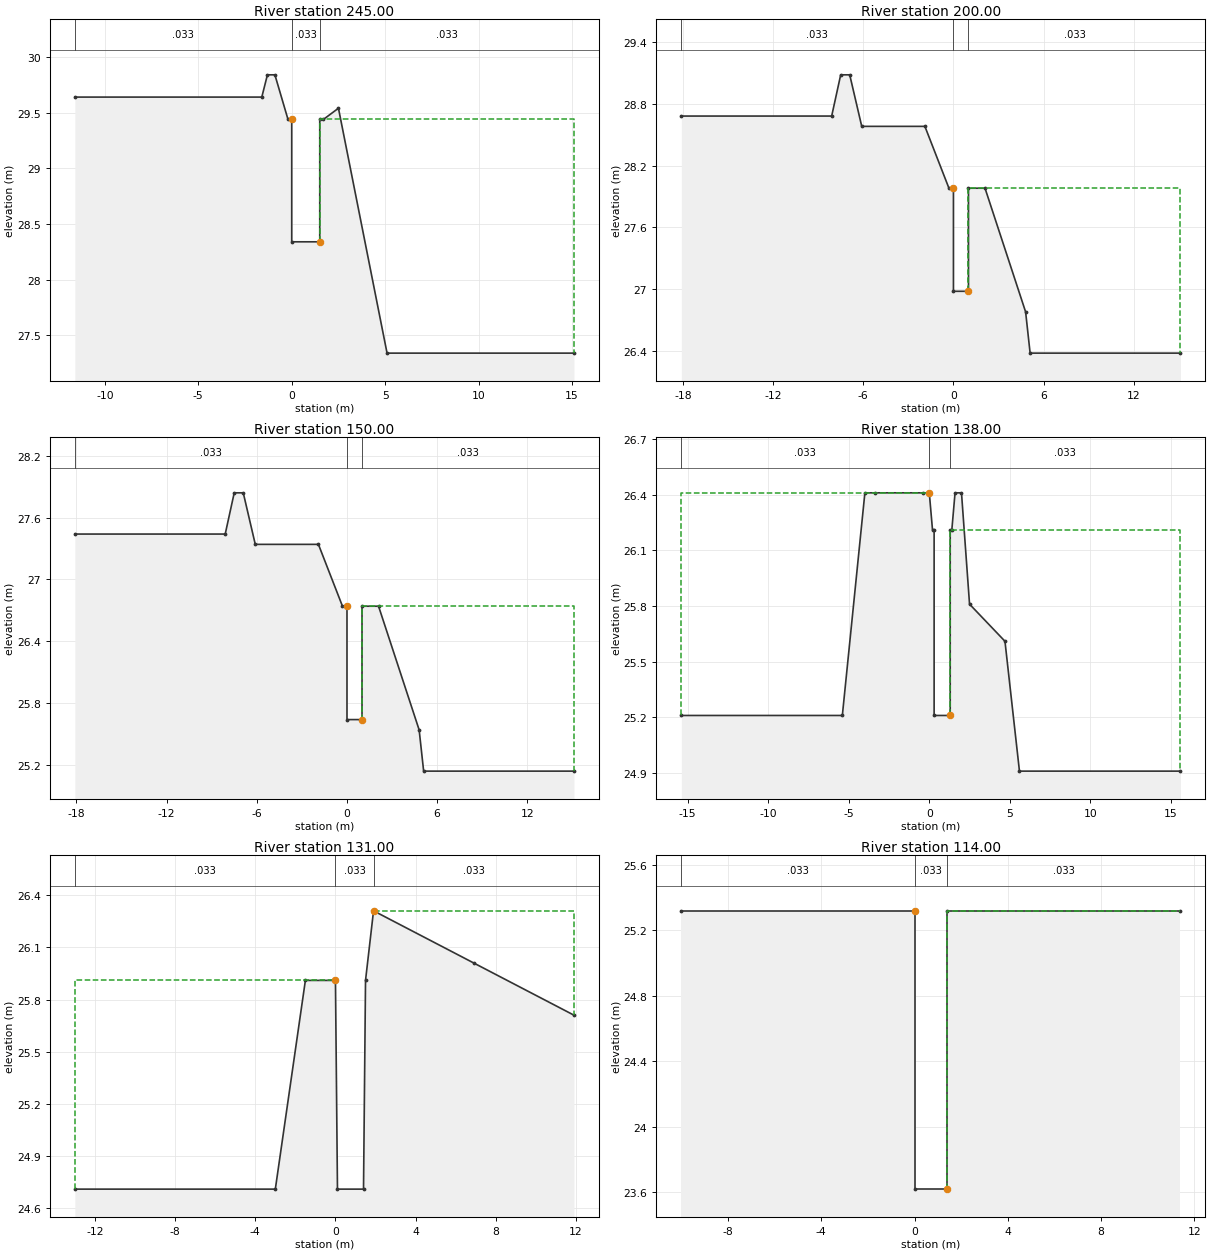
Type RM Length L Ch R = 1 ,245.00  ,45,45,45
BEGIN DESCRIPTION:
4.045
END DESCRIPTION:
#Sta/Elev= 13
   -11.6   29.64    -1.6   29.64    -1.3   29.84     -.9   29.84     -.2   29.44
       0   29.44       0   28.34     1.5   28.34     1.5   29.44     1.7   29.44
     2.5   29.54     5.1   27.34    15.1   27.34
#Mann= 3 , 0 , 0
   -11.6    .033       0       0    .033       0     1.5    .033       0
#XS Ineff= 2 , 0
               0   29.44     1.5           29.44
Permanent Ineff=
       F       F
Bank Sta=0,1.5
XS Rating Curve= 0
Exp/Cntr=.3,.1

Type RM Length L Ch R = 1 ,200.00  ,50,50,50
BEGIN DESCRIPTION:
4
END DESCRIPTION:
#Sta/Elev= 15
   -18.1   28.68    -8.1   28.68    -7.5   29.08    -6.9   29.08    -6.1   28.58
    -1.9   28.58     -.3   27.98       0   27.98       0   26.98       1   26.98
       1   27.98     2.1   27.98     4.8   26.78     5.1   26.38    15.1   26.38
#Mann= 3 , 0 , 0
   -18.1    .033       0       0    .033       0       1    .033       0
#XS Ineff= 2 , 0
               0   27.98       1           27.98
Permanent Ineff=
       F       F
Bank Sta=0,1
XS Rating Curve= 0
Exp/Cntr=.3,.1

Type RM Length L Ch R = 1 ,150.00  ,12,12,12
BEGIN DESCRIPTION:
3
END DESCRIPTION:
#Sta/Elev= 15
   -18.1   27.44    -8.1   27.44    -7.5   27.84    -6.9   27.84    -6.1   27.34
    -1.9   27.34     -.3   26.74       0   26.74       0   25.64       1   25.64
       1   26.74     2.1   26.74     4.8   25.54     5.1   25.14    15.1   25.14
#Mann= 3 , 0 , 0
   -18.1    .033       0       0    .033       0       1    .033       0
#XS Ineff= 2 , 0
               0   26.74       1           26.74
Permanent Ineff=
       F       F
Bank Sta=0,1
XS Rating Curve= 0
Exp/Cntr=.3,.1

Type RM Length L Ch R = 1 ,138.00  ,7,7,7
BEGIN DESCRIPTION:
2.038
END DESCRIPTION:
#Sta/Elev= 18
   -15.4   25.21    -5.4   25.21      -4   26.41    -3.4   26.41     -.4   26.41
       0   26.41      .2   26.21      .3   26.21      .3   25.21     1.3   25.21
     1.3   26.21     1.4   26.21     1.6   26.41       2   26.41     2.5   25.81
     4.7   25.61     5.6   24.91    15.6   24.91
#Mann= 3 , 0 , 0
   -15.4    .033       0       0    .033       0     1.3    .033       0
#XS Ineff= 2 , 0
               0   26.41     1.3           26.21
Permanent Ineff=
       F       F
Bank Sta=0,1.3
XS Rating Curve= 0
Exp/Cntr=.3,.1

Type RM Length L Ch R = 1 ,131.00  ,17,17,17
BEGIN DESCRIPTION:
2.031
END DESCRIPTION:
#Sta/Elev= 10
     -13   24.71      -3   24.71    -1.5   25.91       0   25.91      .1   24.71
     1.4   24.71     1.5   25.91     1.9   26.31     6.9   26.01    11.9   25.71
#Mann= 3 , 0 , 0
     -13    .033       0       0    .033       0     1.9    .033       0
#XS Ineff= 2 , 0
               0   25.91     1.9           26.31
Permanent Ineff=
       F       F
Bank Sta=0,1.9
XS Rating Curve= 0
Exp/Cntr=.3,.1

Type RM Length L Ch R = 1 ,114.00  ,8,8,8
BEGIN DESCRIPTION:
2.014
END DESCRIPTION:
#Sta/Elev= 6
     -10   25.32       0   25.32       0   23.62     1.4   23.62     1.4   25.32
    11.4   25.32
#Mann= 3 , 0 , 0
     -10    .033       0       0    .033       0     1.4    .033       0
#XS Ineff= 2 , 0
               0   25.32     1.4           25.32
Permanent Ineff=
       F       F
Bank Sta=0,1.4
XS Rating Curve= 0
Exp/Cntr=.3,.1

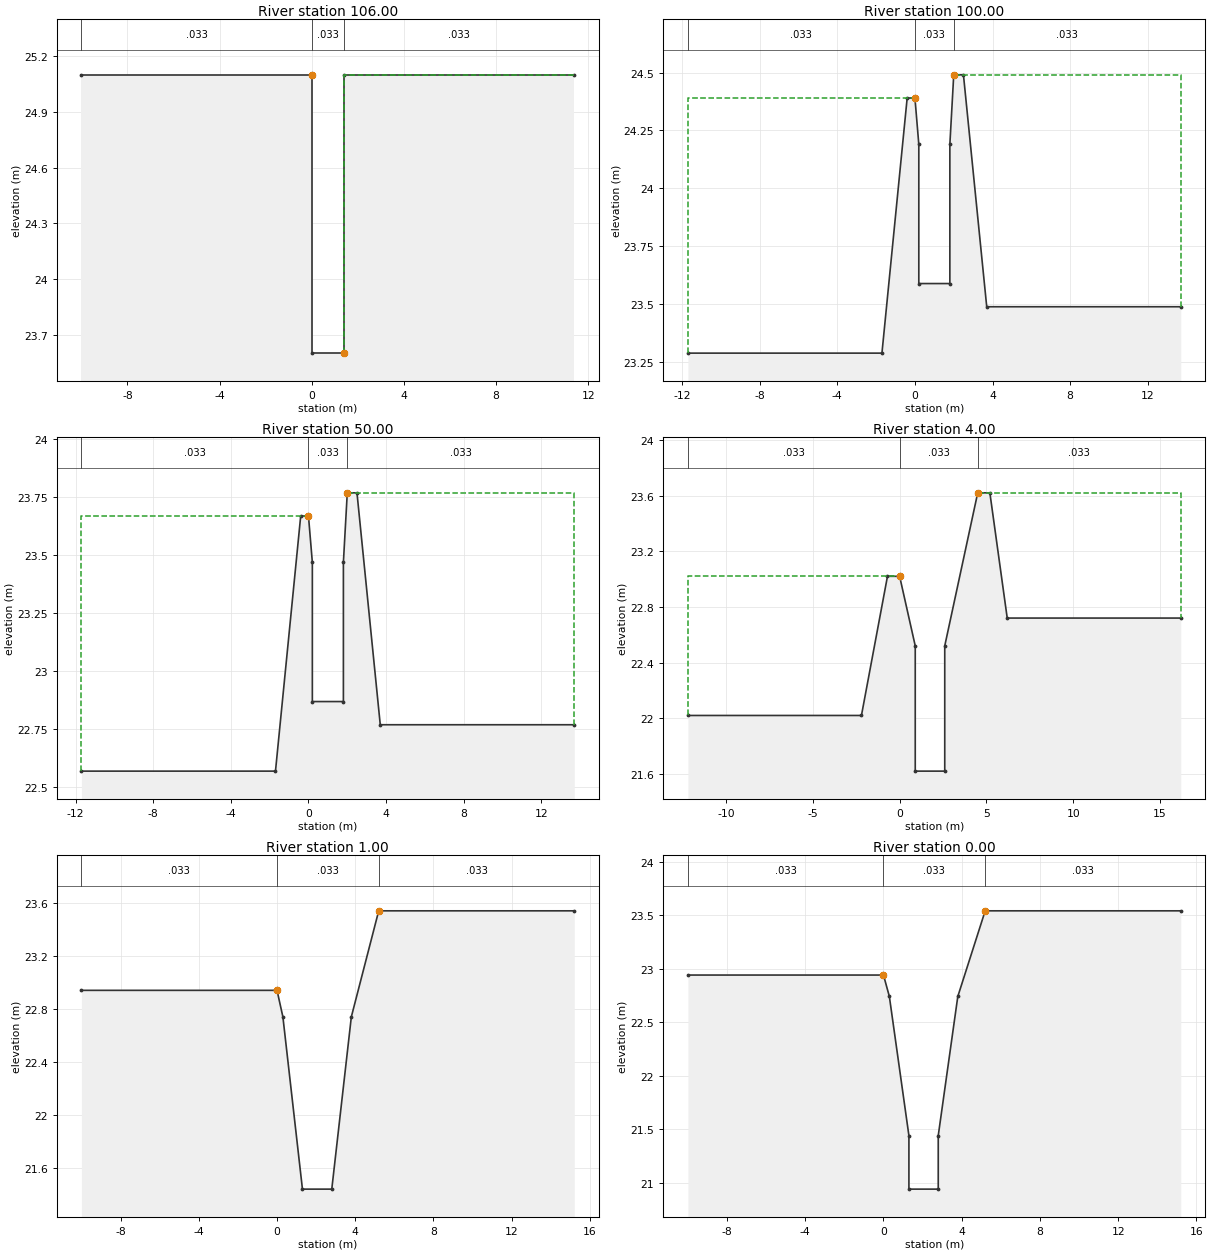
Type RM Length L Ch R = 1 ,106.00  ,6,6,6
BEGIN DESCRIPTION:
2.006
END DESCRIPTION:
#Sta/Elev= 6
     -10    25.1       0    25.1       0    23.6     1.4    23.6     1.4    25.1
    11.4    25.1
#Mann= 3 , 0 , 0
     -10    .033       0       0    .033       0     1.4    .033       0
#XS Ineff= 2 , 0
               0    25.1     1.4            25.1
Permanent Ineff=
       F       F
Bank Sta=0,1.4
XS Rating Curve= 0
Exp/Cntr=.3,.1

Type RM Length L Ch R = 1 ,100.00  ,50,50,50
BEGIN DESCRIPTION:
2
END DESCRIPTION:
#Sta/Elev= 12
   -11.7   23.29    -1.7   23.29     -.4   24.39       0   24.39      .2   24.19
      .2   23.59     1.8   23.59     1.8   24.19       2   24.49     2.5   24.49
     3.7   23.49    13.7   23.49
#Mann= 3 , 0 , 0
   -11.7    .033       0       0    .033       0       2    .033       0
#XS Ineff= 2 , 0
               0   24.39       2           24.49
Permanent Ineff=
       F       F
Bank Sta=0,2
XS Rating Curve= 0
Exp/Cntr=.3,.1

Type RM Length L Ch R = 1 ,50.00   ,46,46,46
BEGIN DESCRIPTION:
1
END DESCRIPTION:
#Sta/Elev= 12
   -11.7   22.57    -1.7   22.57     -.4   23.67       0   23.67      .2   23.47
      .2   22.87     1.8   22.87     1.8   23.47       2   23.77     2.5   23.77
     3.7   22.77    13.7   22.77
#Mann= 3 , 0 , 0
   -11.7    .033       0       0    .033       0       2    .033       0
#XS Ineff= 2 , 0
               0   23.67       2           23.77
Permanent Ineff=
       F       F
Bank Sta=0,2
XS Rating Curve= 0
Exp/Cntr=.3,.1

Type RM Length L Ch R = 1 ,4.00    ,3,3,3
BEGIN DESCRIPTION:
0.004
END DESCRIPTION:
#Sta/Elev= 12
   -12.2   22.02    -2.2   22.02     -.7   23.02       0   23.02      .9   22.52
      .9   21.62     2.6   21.62     2.6   22.52     4.5   23.62     5.2   23.62
     6.2   22.72    16.2   22.72
#Mann= 3 , 0 , 0
   -12.2    .033       0       0    .033       0     4.5    .033       0
#XS Ineff= 2 , 0
               0   23.02     4.5           23.62
Permanent Ineff=
       F       F
Bank Sta=0,4.5
XS Rating Curve= 0
Exp/Cntr=.3,.1

Type RM Length L Ch R = 1 ,1.00    ,1,1,1
BEGIN DESCRIPTION:
0.001
END DESCRIPTION:
#Sta/Elev= 8
     -10   22.94       0   22.94      .3   22.74     1.3   21.44     2.8   21.44
     3.8   22.74     5.2   23.54    15.2   23.54
#Mann= 3 , 0 , 0
     -10    .033       0       0    .033       0     5.2    .033       0
#XS Ineff= 2 , 0
               0   22.94     5.2           23.54
Permanent Ineff=
       F       F
Bank Sta=0,5.2
XS Rating Curve= 0
Exp/Cntr=.3,.1

Type RM Length L Ch R = 1 ,0.00    ,0,0,0
BEGIN DESCRIPTION:
0
END DESCRIPTION:
#Sta/Elev= 10
     -10   22.94       0   22.94      .3   22.74     1.3   21.44     1.3   20.94
     2.8   20.94     2.8   21.44     3.8   22.74     5.2   23.54    15.2   23.54
#Mann= 3 , 0 , 0
     -10    .033       0       0    .033       0     5.2    .033       0
#XS Ineff= 2 , 0
               0   22.94     5.2           23.54
Permanent Ineff=
       F       F
Bank Sta=0,5.2
XS Rating Curve= 0
Exp/Cntr=.3,.1

Chan Stop Cuts=-1