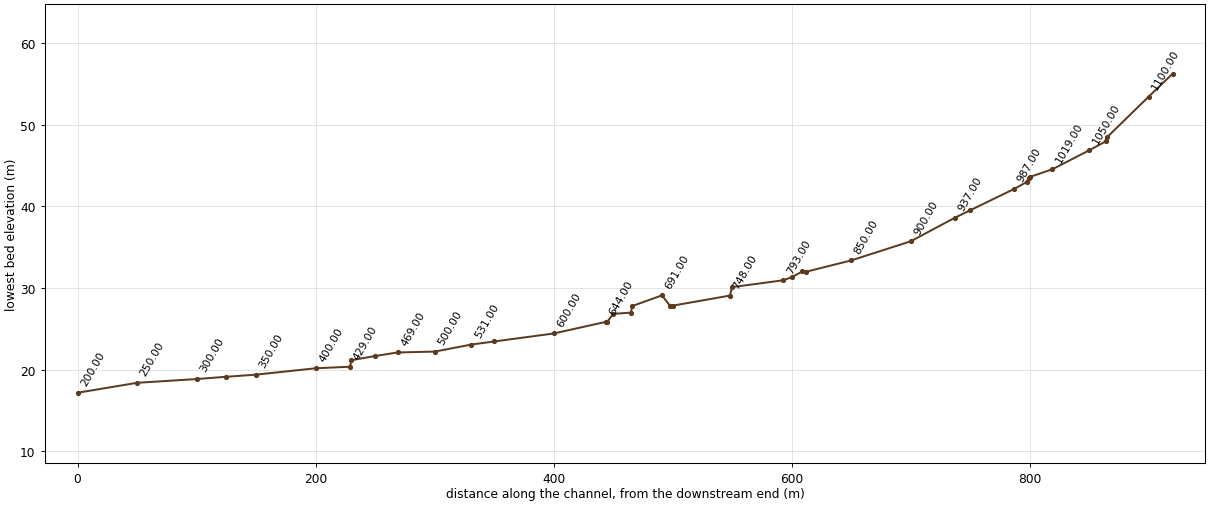
--- JJK.prj (project) ---

Proj Title=JJK
Current Plan=p01
Default Exp/Contr=.3,.1
SI Units
Geom File=g01
Flow File=f01
Plan File=p01
Y Axis Title=Elevation
X Axis Title(PF)=Main Channel Distance
X Axis Title(XS)=Station
BEGIN DESCRIPTION:
           BACK WATER COMPUTATION
      APPLICATION OF HEC-2 BY Samju Construction Engineering
      JANGJAKGOL-STREEM : 30 YR
END DESCRIPTION:
DSS Export Rating Curves= 0
DSS Export Rating Curve Sorted= 0
DSS Export Volume Flow Curves= 0
DXF OffsetX= 0
DXF OffsetY= 0
DXF ScaleX= 1
DXF ScaleY= 10

--- JJK.p01 (plan) ---

Plan Title=Imported Plan 01
Version=Version 3.0.1  Mar 2001
Short Identifier=Imported Pla
Geom File=g01
Flow File=f01
Subcritical Flow
K Sum by GR= 0
Std Step Tol= 0.003
Critical Tol= 0.003
Num of Std Step Trials= 20
Max Error Tol= 0.1
Flow Tol Ratio= 0.001
Split Flow NTrial= 30
Split Flow Tol= 0.02
Split Flow Ratio= 0.02
Log Output Level= 0
Friction Slope Method= 1
Unsteady Friction Slope Method= 2
Parabolic Critical Depth
Global Vel Dist= 0 , 0 , 0
Global Log Level= 0
CheckData=True
Encroach Param=-1 ,0,0, 0
Computation Interval=1HOUR
Output Interval=1HOUR
Run HTab= 0
Run UNet= 0
Run PostProcess= 0
UNET Theta= 1
UNET ZTol= 0.02
UNET ZSATol= 0.1
UNET MxIter= 20
UNET MaxInSteps= 20
UNET DtIC= 0
UNET DtMin= 0
UNET MaxCRTS= 20
UNET WFStab= 2
UNET SFStab= 1
UNET WFX= 1
UNET SFX= 1
UNET Convert EG Bridges=-1
UNET Use Existing IB Tables=-1
Instantaneous Interval=1HOUR
Write IC File= 0
Write Velocity= 0
Write Detailed= 0

--- JJK.f01 (steady flow) ---

Flow Title=Imported Flow 01
Version=Version 3.0.1  Mar 2001
Number of Profiles= 5
Profile Names=10YR,20YR,30YR,50YR,80YR
River Rch & RM=RIVER-1,Reach-1         ,1120.00
    4.67    5.14    5.42    5.76    6.09
Boundary for River Rch & Prof#=RIVER-1,Reach-1         , 1
Up Type= 0
Dn Type= 3
Dn Slope=.042
Boundary for River Rch & Prof#=RIVER-1,Reach-1         , 2
Up Type= 0
Dn Type= 3
Dn Slope=.042
Boundary for River Rch & Prof#=RIVER-1,Reach-1         , 3
Up Type= 0
Dn Type= 3
Dn Slope=.042
Boundary for River Rch & Prof#=RIVER-1,Reach-1         , 4
Up Type= 0
Dn Type= 3
Dn Slope=.042
Boundary for River Rch & Prof#=RIVER-1,Reach-1         , 5
Up Type= 0
Dn Type= 3
Dn Slope=.042
DSS Import GetInterval= 0
DSS Import GetPeak= 0
DSS Import FillOption= 0

--- JJK.g01 (geometry) ---

Geom Title=Imported Geom 01
Version=Version 3.0.1  Mar 2001

River Reach=RIVER-1         ,Reach-1
Reach XY= 2
              .5             .95              .5             .05

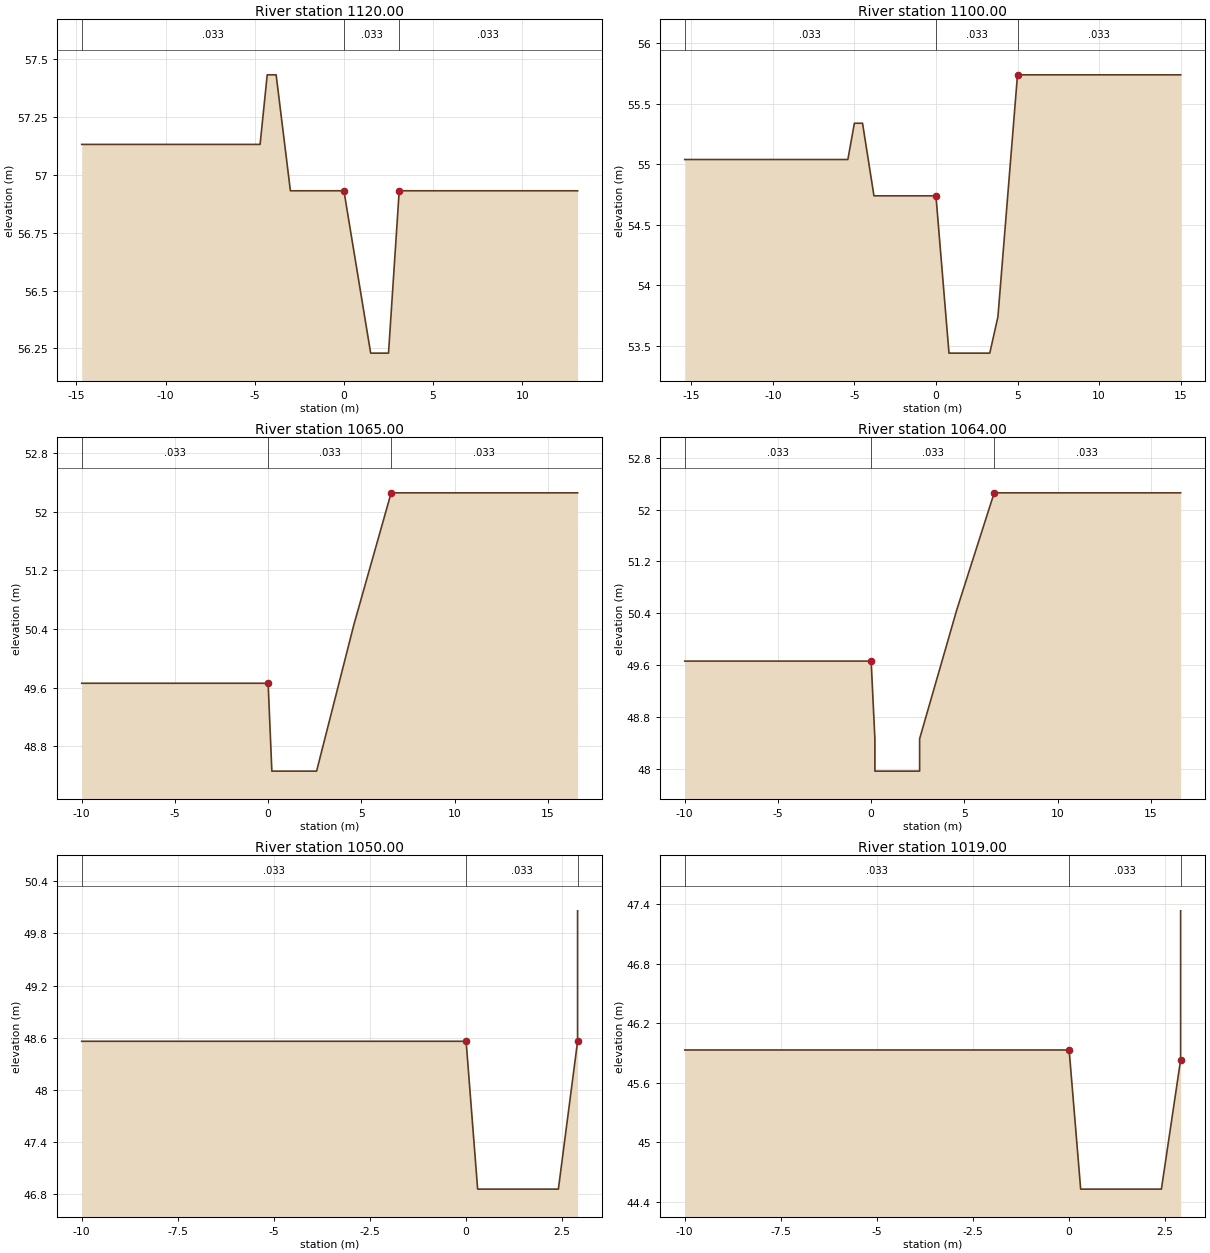
Type RM Length L Ch R = 1 ,1120.00 ,20,20,20
BEGIN DESCRIPTION:
22.02
END DESCRIPTION:
#Sta/Elev= 10
   -14.7   57.13    -4.7   57.13    -4.3   57.43    -3.8   57.43      -3   56.93
       0   56.93     1.5   56.23     2.5   56.23     3.1   56.93    13.1   56.93
#Mann= 3 , 0 , 0
   -14.7    .033       0       0    .033       0     3.1    .033       0
#XS Ineff= 2 , 0
               0   56.93     3.1           56.93
Permanent Ineff=
       F       F
Bank Sta=0,3.1
XS Rating Curve= 0
Exp/Cntr=.3,.1

Type RM Length L Ch R = 1 ,1100.00 ,35,35,35
BEGIN DESCRIPTION:
22
END DESCRIPTION:
#Sta/Elev= 12
   -15.4   55.04    -5.4   55.04      -5   55.34    -4.5   55.34    -3.8   54.74
     -.8   54.74       0   54.74      .8   53.44     3.3   53.44     3.8   53.74
       5   55.74      15   55.74
#Mann= 3 , 0 , 0
   -15.4    .033       0       0    .033       0       5    .033       0
#XS Ineff= 2 , 0
               0   54.74       5           55.74
Permanent Ineff=
       F       F
Bank Sta=0,5
XS Rating Curve= 0
Exp/Cntr=.3,.1

Type RM Length L Ch R = 1 ,1065.00 ,1,1,1
BEGIN DESCRIPTION:
21.015
END DESCRIPTION:
#Sta/Elev= 7
     -10   49.66       0   49.66      .2   48.46     2.6   48.46     4.6   50.46
     6.6   52.26    16.6   52.26
#Mann= 3 , 0 , 0
     -10    .033       0       0    .033       0     6.6    .033       0
#XS Ineff= 2 , 0
               0   49.66     6.6           52.26
Permanent Ineff=
       F       F
Bank Sta=0,6.6
XS Rating Curve= 0
Exp/Cntr=.3,.1

Type RM Length L Ch R = 1 ,1064.00 ,14,14,14
BEGIN DESCRIPTION:
21.014
END DESCRIPTION:
#Sta/Elev= 9
     -10   49.66       0   49.66      .2   48.46      .2   47.96     2.6   47.96
     2.6   48.46     4.6   50.46     6.6   52.26    16.6   52.26
#Mann= 3 , 0 , 0
     -10    .033       0       0    .033       0     6.6    .033       0
#XS Ineff= 2 , 0
               0   49.66     6.6           52.26
Permanent Ineff=
       F       F
Bank Sta=0,6.6
XS Rating Curve= 0
Exp/Cntr=.3,.1

Type RM Length L Ch R = 1 ,1050.00 ,31,31,31
BEGIN DESCRIPTION:
21
END DESCRIPTION:
#Sta/Elev= 6
     -10   48.56       0   48.56      .3   46.86     2.4   46.86     2.9   48.56
     2.9   50.06
#Mann= 3 , 0 , 0
     -10    .033       0       0    .033       0     2.9    .033       0
#XS Ineff= 2 , 0
               0   48.56     2.9           50.06
Permanent Ineff=
       F       F
Bank Sta=0,2.9
XS Rating Curve= 0
Exp/Cntr=.3,.1

Type RM Length L Ch R = 1 ,1019.00 ,19,19,19
BEGIN DESCRIPTION:
20.019
END DESCRIPTION:
#Sta/Elev= 6
     -10   45.93       0   45.93      .3   44.53     2.4   44.53     2.9   45.83
     2.9   47.33
#Mann= 3 , 0 , 0
     -10    .033       0       0    .033       0     2.9    .033       0
#XS Ineff= 2 , 0
               0   45.93     2.9           47.33
Permanent Ineff=
       F       F
Bank Sta=0,2.9
XS Rating Curve= 0
Exp/Cntr=.3,.1

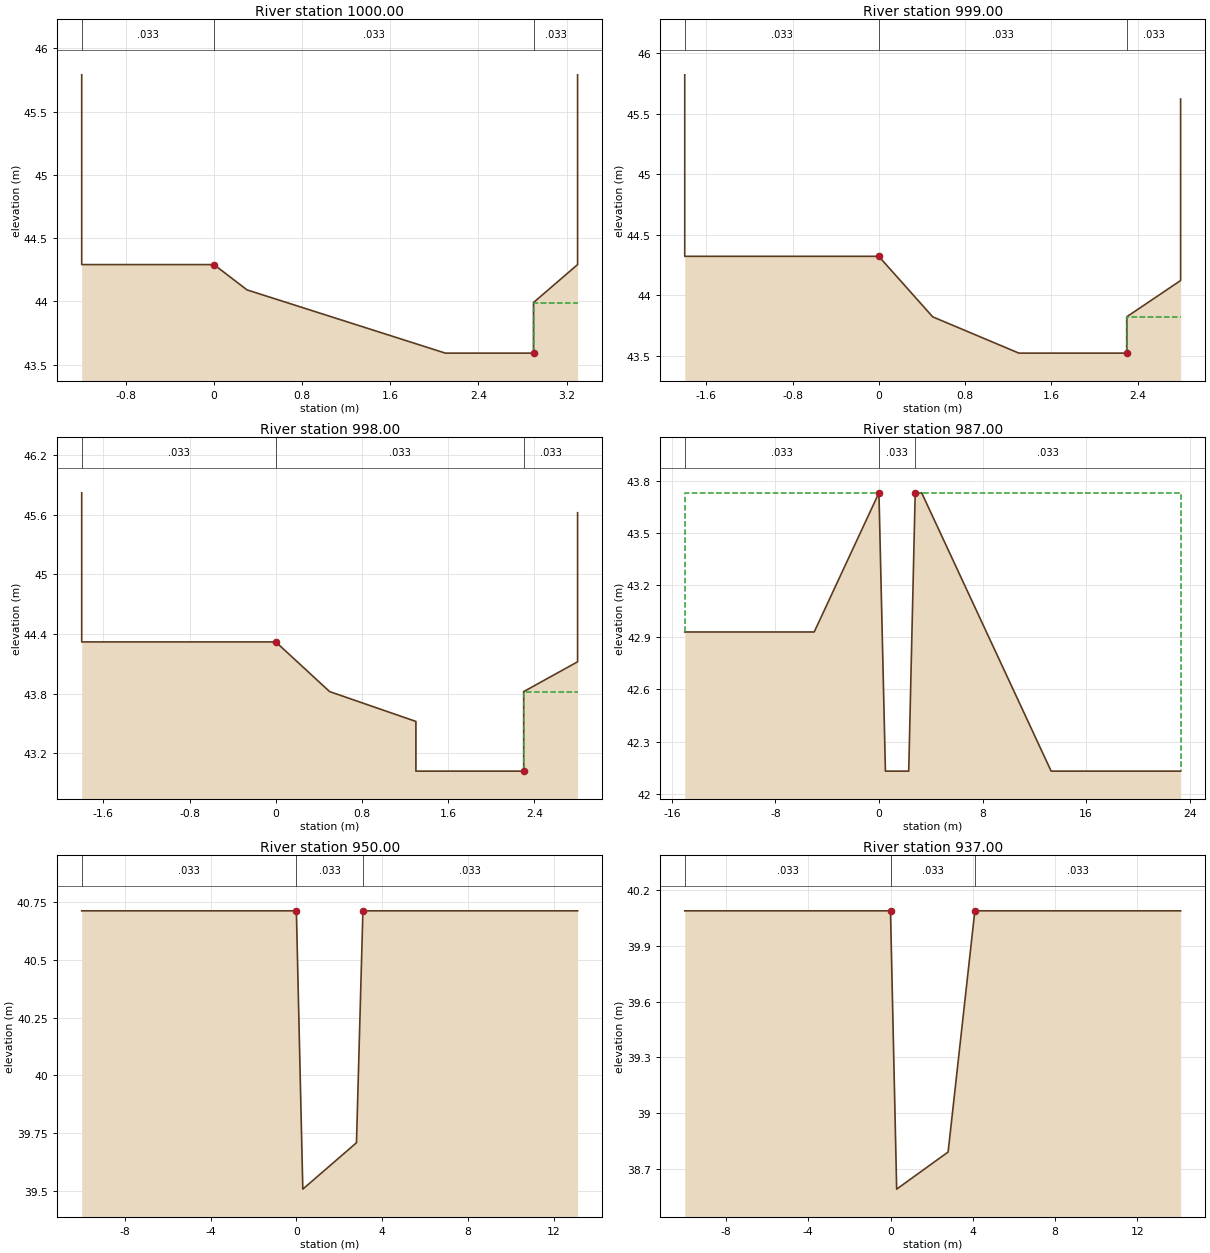
Type RM Length L Ch R = 1 ,1000.00 ,1,1,1
BEGIN DESCRIPTION:
20
END DESCRIPTION:
#Sta/Elev= 9
    -1.2   45.79    -1.2   44.29       0   44.29      .3   44.09     2.1   43.59
     2.9   43.59     2.9   43.99     3.3   44.29     3.3   45.79
#Mann= 3 , 0 , 0
    -1.2    .033       0       0    .033       0     2.9    .033       0
#XS Ineff= 2 , 0
               0   44.29     2.9           43.99
Permanent Ineff=
       F       F
Bank Sta=0,2.9
XS Rating Curve= 0
Exp/Cntr=.3,.1

Type RM Length L Ch R = 1 ,999.00  ,1,1,1
BEGIN DESCRIPTION:
19.049
END DESCRIPTION:
#Sta/Elev= 9
    -1.8   45.82    -1.8   44.32       0   44.32      .5   43.82     1.3   43.52
     2.3   43.52     2.3   43.82     2.8   44.12     2.8   45.62
#Mann= 3 , 0 , 0
    -1.8    .033       0       0    .033       0     2.3    .033       0
#XS Ineff= 2 , 0
               0   44.32     2.3           43.82
Permanent Ineff=
       F       F
Bank Sta=0,2.3
XS Rating Curve= 0
Exp/Cntr=.3,.1

Type RM Length L Ch R = 1 ,998.00  ,11,11,11
BEGIN DESCRIPTION:
19.048
END DESCRIPTION:
#Sta/Elev= 11
    -1.8   45.82    -1.8   44.32       0   44.32      .5   43.82     1.3   43.52
     1.3   43.02     2.3   43.02     2.3   43.52     2.3   43.82     2.8   44.12
     2.8   45.62
#Mann= 3 , 0 , 0
    -1.8    .033       0       0    .033       0     2.3    .033       0
#XS Ineff= 2 , 0
               0   44.32     2.3           43.82
Permanent Ineff=
       F       F
Bank Sta=0,2.3
XS Rating Curve= 0
Exp/Cntr=.3,.1

Type RM Length L Ch R = 1 ,987.00  ,37,37,37
BEGIN DESCRIPTION:
19.037
END DESCRIPTION:
#Sta/Elev= 10
     -15   42.93      -5   42.93       0   43.73      .5   42.13     2.3   42.13
     2.8   43.73     3.3   43.73     8.3   42.93    13.3   42.13    23.3   42.13
#Mann= 3 , 0 , 0
     -15    .033       0       0    .033       0     2.8    .033       0
#XS Ineff= 2 , 0
               0   43.73     2.8           43.73
Permanent Ineff=
       F       F
Bank Sta=0,2.8
XS Rating Curve= 0
Exp/Cntr=.3,.1

Type RM Length L Ch R = 1 ,950.00  ,13,13,13
BEGIN DESCRIPTION:
19
END DESCRIPTION:
#Sta/Elev= 6
     -10   40.71       0   40.71      .3   39.51     2.8   39.71     3.1   40.71
    13.1   40.71
#Mann= 3 , 0 , 0
     -10    .033       0       0    .033       0     3.1    .033       0
#XS Ineff= 2 , 0
               0   40.71     3.1           40.71
Permanent Ineff=
       F       F
Bank Sta=0,3.1
XS Rating Curve= 0
Exp/Cntr=.3,.1

Type RM Length L Ch R = 1 ,937.00  ,37,37,37
BEGIN DESCRIPTION:
18.037
END DESCRIPTION:
#Sta/Elev= 6
     -10   40.09       0   40.09      .3   38.59     2.8   38.79     4.1   40.09
    14.1   40.09
#Mann= 3 , 0 , 0
     -10    .033       0       0    .033       0     4.1    .033       0
#XS Ineff= 2 , 0
               0   40.09     4.1           40.09
Permanent Ineff=
       F       F
Bank Sta=0,4.1
XS Rating Curve= 0
Exp/Cntr=.3,.1

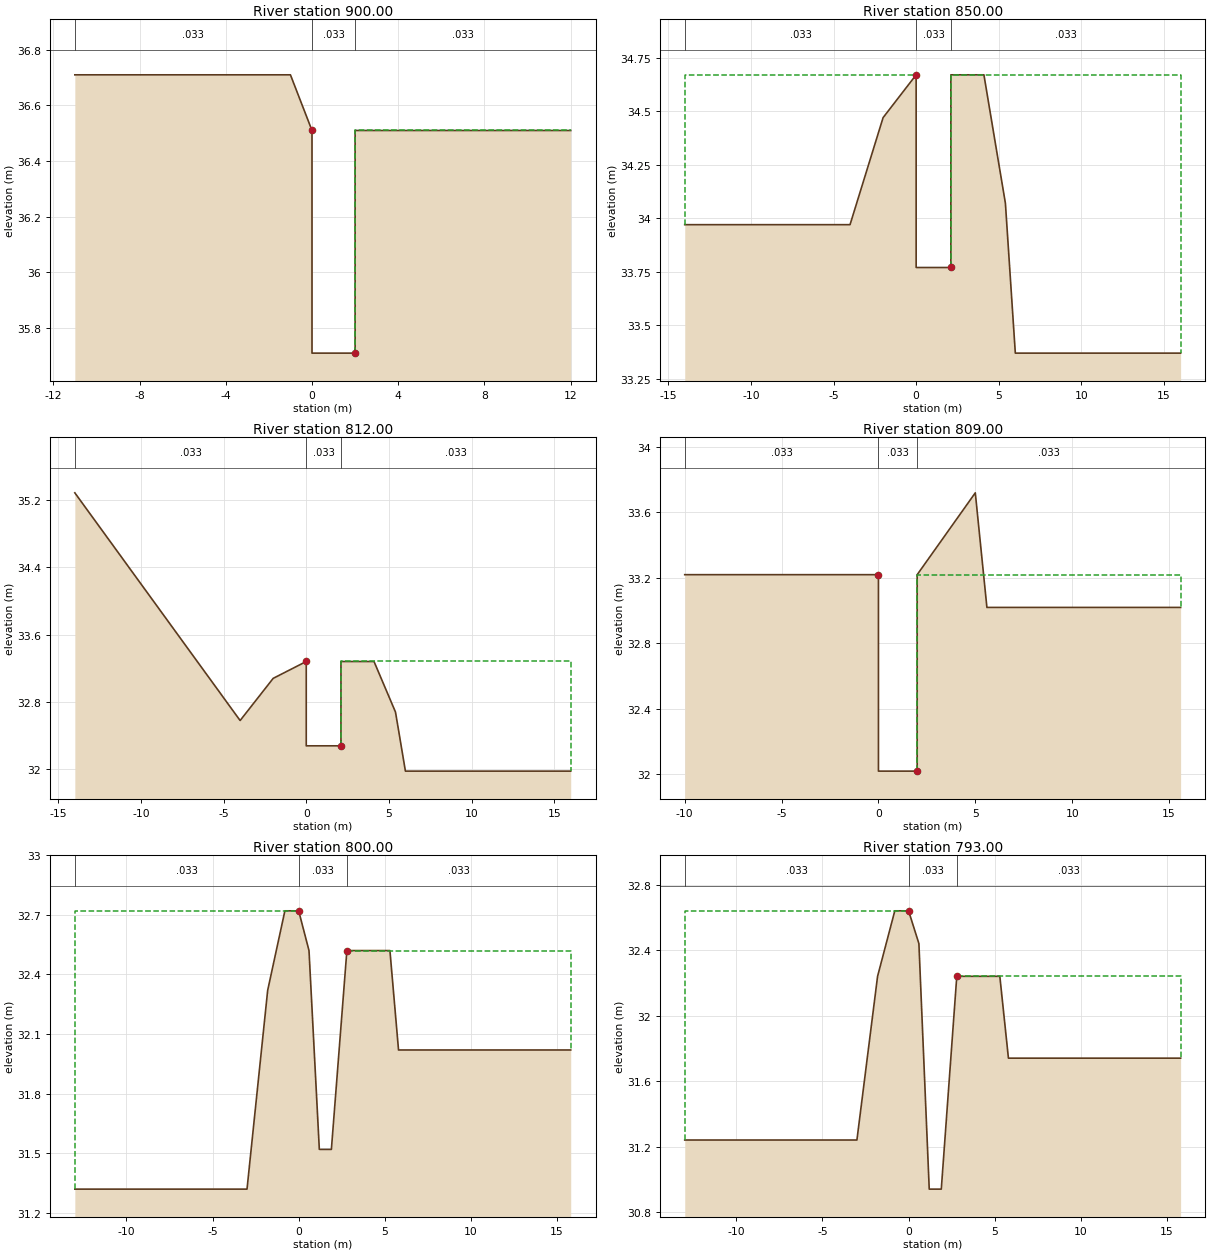
Type RM Length L Ch R = 1 ,900.00  ,50,50,50
BEGIN DESCRIPTION:
18
END DESCRIPTION:
#Sta/Elev= 7
     -11   36.71      -1   36.71       0   36.51       0   35.71       2   35.71
       2   36.51      12   36.51
#Mann= 3 , 0 , 0
     -11    .033       0       0    .033       0       2    .033       0
#XS Ineff= 2 , 0
               0   36.51       2           36.51
Permanent Ineff=
       F       F
Bank Sta=0,2
XS Rating Curve= 0
Exp/Cntr=.3,.1

Type RM Length L Ch R = 1 ,850.00  ,38,38,38
BEGIN DESCRIPTION:
17
END DESCRIPTION:
#Sta/Elev= 11
     -14   33.97      -4   33.97      -2   34.47       0   34.67       0   33.77
     2.1   33.77     2.1   34.67     4.1   34.67     5.4   34.07       6   33.37
      16   33.37
#Mann= 3 , 0 , 0
     -14    .033       0       0    .033       0     2.1    .033       0
#XS Ineff= 2 , 0
               0   34.67     2.1           34.67
Permanent Ineff=
       F       F
Bank Sta=0,2.1
XS Rating Curve= 0
Exp/Cntr=.3,.1

Type RM Length L Ch R = 1 ,812.00  ,3,3,3
BEGIN DESCRIPTION:
16.012
END DESCRIPTION:
#Sta/Elev= 11
     -14   35.28      -4   32.58      -2   33.08       0   33.28       0   32.28
     2.1   32.28     2.1   33.28     4.1   33.28     5.4   32.68       6   31.98
      16   31.98
#Mann= 3 , 0 , 0
     -14    .033       0       0    .033       0     2.1    .033       0
#XS Ineff= 2 , 0
               0   33.28     2.1           33.28
Permanent Ineff=
       F       F
Bank Sta=0,2.1
XS Rating Curve= 0
Exp/Cntr=.3,.1

Type RM Length L Ch R = 1 ,809.00  ,9,9,9
BEGIN DESCRIPTION:
16.009
END DESCRIPTION:
#Sta/Elev= 8
     -10   33.22       0   33.22       0   32.02       2   32.02       2   33.22
       5   33.72     5.6   33.02    15.6   33.02
#Mann= 3 , 0 , 0
     -10    .033       0       0    .033       0       2    .033       0
#XS Ineff= 2 , 0
               0   33.22       2           33.22
Permanent Ineff=
       F       F
Bank Sta=0,2
XS Rating Curve= 0
Exp/Cntr=.3,.1

Type RM Length L Ch R = 1 ,800.00  ,7,7,7
BEGIN DESCRIPTION:
16
END DESCRIPTION:
#Sta/Elev= 12
     -13   31.32      -3   31.32    -1.8   32.32     -.8   32.72       0   32.72
      .6   32.52     1.2   31.52     1.9   31.52     2.8   32.52     5.3   32.52
     5.8   32.02    15.8   32.02
#Mann= 3 , 0 , 0
     -13    .033       0       0    .033       0     2.8    .033       0
#XS Ineff= 2 , 0
               0   32.72     2.8           32.52
Permanent Ineff=
       F       F
Bank Sta=0,2.8
XS Rating Curve= 0
Exp/Cntr=.3,.1

Type RM Length L Ch R = 1 ,793.00  ,43,43,43
BEGIN DESCRIPTION:
15.043
END DESCRIPTION:
#Sta/Elev= 12
     -13   31.24      -3   31.24    -1.8   32.24     -.8   32.64       0   32.64
      .6   32.44     1.2   30.94     1.9   30.94     2.8   32.24     5.3   32.24
     5.8   31.74    15.8   31.74
#Mann= 3 , 0 , 0
     -13    .033       0       0    .033       0     2.8    .033       0
#XS Ineff= 2 , 0
               0   32.64     2.8           32.24
Permanent Ineff=
       F       F
Bank Sta=0,2.8
XS Rating Curve= 0
Exp/Cntr=.3,.1

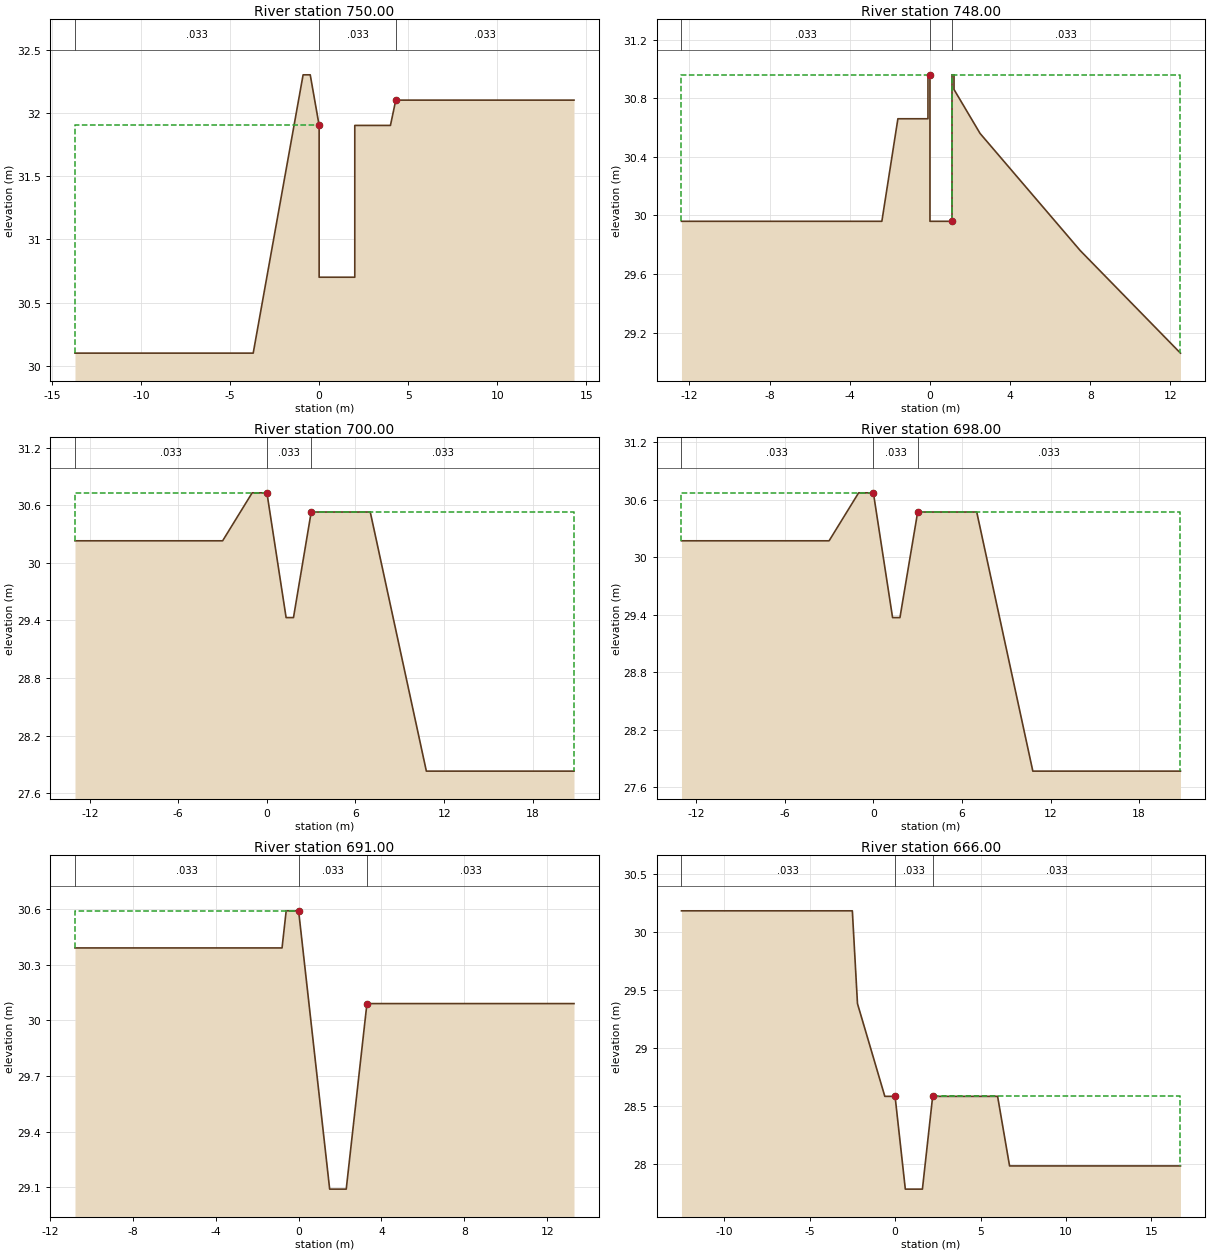
Type RM Length L Ch R = 1 ,750.00  ,2,2,2
BEGIN DESCRIPTION:
15
END DESCRIPTION:
#Sta/Elev= 11
   -13.7    30.1    -3.7    30.1     -.9    32.3     -.5    32.3       0    31.9
       0    30.7       2    30.7       2    31.9       4    31.9     4.3    32.1
    14.3    32.1
#Mann= 3 , 0 , 0
   -13.7    .033       0       0    .033       0     4.3    .033       0
#XS Ineff= 2 , 0
               0    31.9     4.3            32.1
Permanent Ineff=
       F       F
Bank Sta=0,4.3
XS Rating Curve= 0
Exp/Cntr=.3,.1

Type RM Length L Ch R = 1 ,748.00  ,48,48,48
BEGIN DESCRIPTION:
14.048
END DESCRIPTION:
#Sta/Elev= 14
   -12.4   29.96    -2.4   29.96    -1.6   30.66     -.1   30.66     -.1   30.96
       0   30.96       0   29.96     1.1   29.96     1.1   30.96     1.2   30.96
     1.2   30.86     2.5   30.56     7.5   29.76    12.5   29.06
#Mann= 3 , 0 , 0
   -12.4    .033       0       0    .033       0     1.1    .033       0
#XS Ineff= 2 , 0
               0   30.96     1.1           30.96
Permanent Ineff=
       F       F
Bank Sta=0,1.1
XS Rating Curve= 0
Exp/Cntr=.3,.1

Type RM Length L Ch R = 1 ,700.00  ,2,2,2
BEGIN DESCRIPTION:
14
END DESCRIPTION:
#Sta/Elev= 10
     -13   30.23      -3   30.23      -1   30.73       0   30.73     1.3   29.43
     1.8   29.43       3   30.53       7   30.53    10.8   27.83    20.8   27.83
#Mann= 3 , 0 , 0
     -13    .033       0       0    .033       0       3    .033       0
#XS Ineff= 2 , 0
               0   30.73       3           30.53
Permanent Ineff=
       F       F
Bank Sta=0,3
XS Rating Curve= 0
Exp/Cntr=.3,.1

Type RM Length L Ch R = 1 ,698.00  ,7,7,7
BEGIN DESCRIPTION:
13.048
END DESCRIPTION:
#Sta/Elev= 10
     -13   30.17      -3   30.17      -1   30.67       0   30.67     1.3   29.37
     1.8   29.37       3   30.47       7   30.47    10.8   27.77    20.8   27.77
#Mann= 3 , 0 , 0
     -13    .033       0       0    .033       0       3    .033       0
#XS Ineff= 2 , 0
               0   30.67       3           30.47
Permanent Ineff=
       F       F
Bank Sta=0,3
XS Rating Curve= 0
Exp/Cntr=.3,.1

Type RM Length L Ch R = 1 ,691.00  ,25,25,25
BEGIN DESCRIPTION:
13.041
END DESCRIPTION:
#Sta/Elev= 8
   -10.8   30.39     -.8   30.39     -.6   30.59       0   30.59     1.5   29.09
     2.3   29.09     3.3   30.09    13.3   30.09
#Mann= 3 , 0 , 0
   -10.8    .033       0       0    .033       0     3.3    .033       0
#XS Ineff= 2 , 0
               0   30.59     3.3           30.09
Permanent Ineff=
       F       F
Bank Sta=0,3.3
XS Rating Curve= 0
Exp/Cntr=.3,.1

Type RM Length L Ch R = 1 ,666.00  ,1,1,1
BEGIN DESCRIPTION:
13.016
END DESCRIPTION:
#Sta/Elev= 12
   -12.5   30.18    -2.5   30.18    -2.2   29.38     -.6   28.58       0   28.58
      .6   27.78     1.6   27.78     2.2   28.58     2.8   28.58       6   28.58
     6.7   27.98    16.7   27.98
#Mann= 3 , 0 , 0
   -12.5    .033       0       0    .033       0     2.2    .033       0
#XS Ineff= 2 , 0
               0   28.58     2.2           28.58
Permanent Ineff=
       F       F
Bank Sta=0,2.2
XS Rating Curve= 0
Exp/Cntr=.3,.1

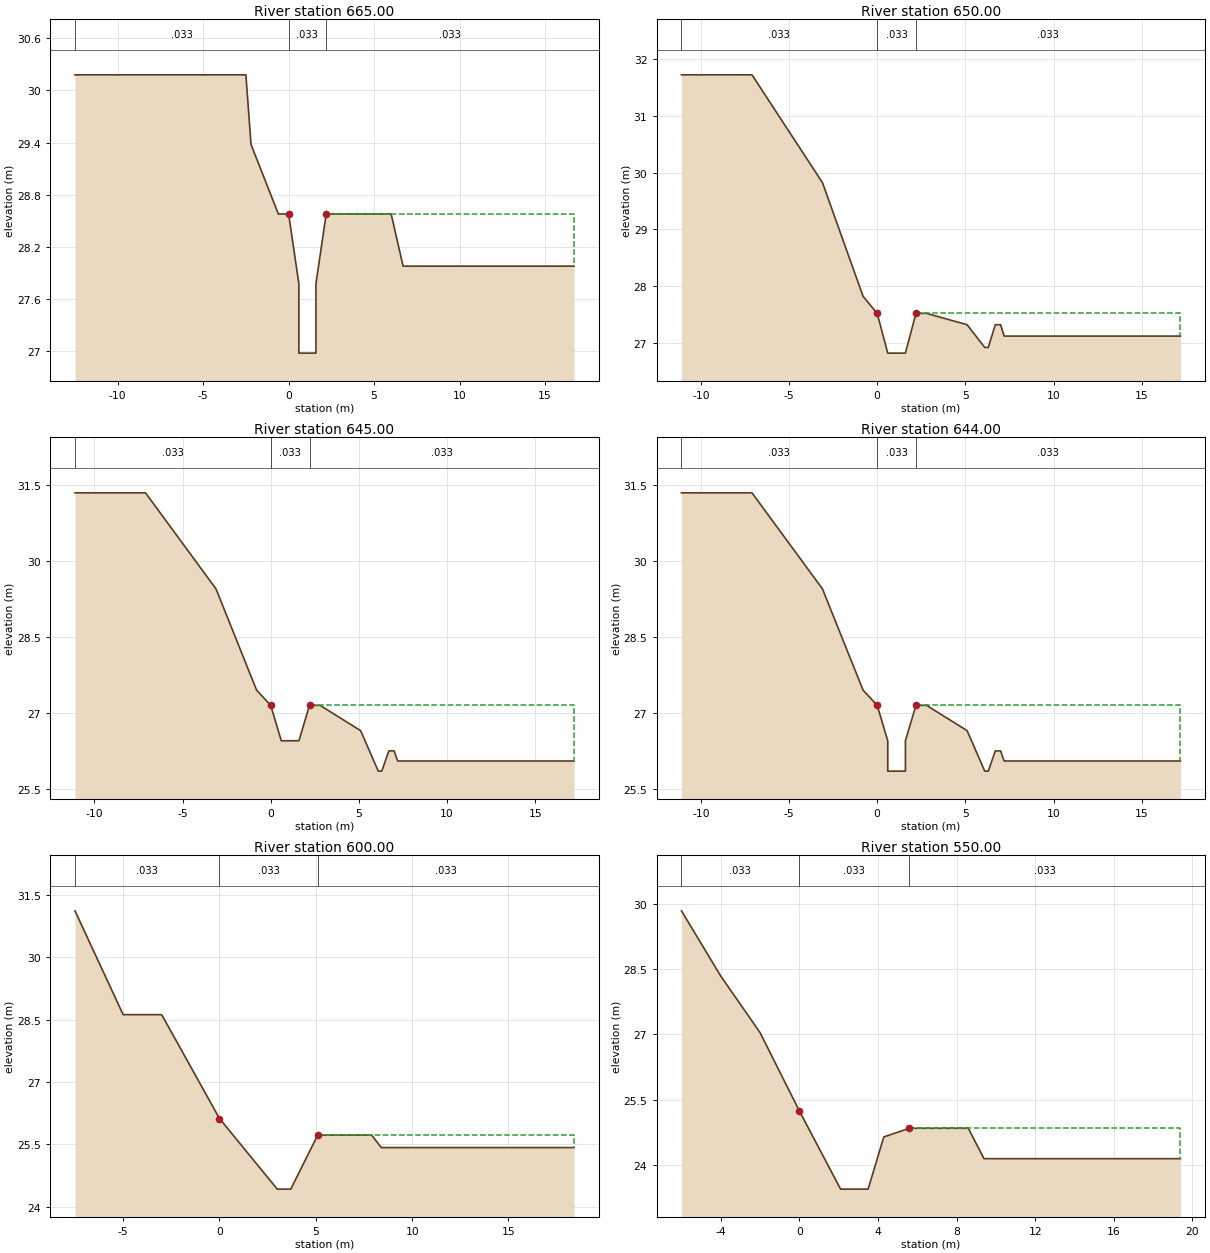
Type RM Length L Ch R = 1 ,665.00  ,15,15,15
BEGIN DESCRIPTION:
13.015
END DESCRIPTION:
#Sta/Elev= 14
   -12.5   30.18    -2.5   30.18    -2.2   29.38     -.6   28.58       0   28.58
      .6   27.78      .6   26.98     1.6   26.98     1.6   27.78     2.2   28.58
     2.8   28.58       6   28.58     6.7   27.98    16.7   27.98
#Mann= 3 , 0 , 0
   -12.5    .033       0       0    .033       0     2.2    .033       0
#XS Ineff= 2 , 0
               0   28.58     2.2           28.58
Permanent Ineff=
       F       F
Bank Sta=0,2.2
XS Rating Curve= 0
Exp/Cntr=.3,.1

Type RM Length L Ch R = 1 ,650.00  ,5,5,5
BEGIN DESCRIPTION:
13
END DESCRIPTION:
#Sta/Elev= 16
   -11.1   31.72    -7.1   31.72    -3.1   29.82     -.8   27.82       0   27.52
      .6   26.82     1.6   26.82     2.2   27.52     2.8   27.52     5.1   27.32
     6.1   26.92     6.3   26.92     6.7   27.32       7   27.32     7.2   27.12
    17.2   27.12
#Mann= 3 , 0 , 0
   -11.1    .033       0       0    .033       0     2.2    .033       0
#XS Ineff= 2 , 0
               0   27.52     2.2           27.52
Permanent Ineff=
       F       F
Bank Sta=0,2.2
XS Rating Curve= 0
Exp/Cntr=.3,.1

Type RM Length L Ch R = 1 ,645.00  ,1,1,1
BEGIN DESCRIPTION:
12.045
END DESCRIPTION:
#Sta/Elev= 16
   -11.1   31.35    -7.1   31.35    -3.1   29.45     -.8   27.45       0   27.15
      .6   26.45     1.6   26.45     2.2   27.15     2.8   27.15     5.1   26.65
     6.1   25.85     6.3   25.85     6.7   26.25       7   26.25     7.2   26.05
    17.2   26.05
#Mann= 3 , 0 , 0
   -11.1    .033       0       0    .033       0     2.2    .033       0
#XS Ineff= 2 , 0
               0   27.15     2.2           27.15
Permanent Ineff=
       F       F
Bank Sta=0,2.2
XS Rating Curve= 0
Exp/Cntr=.3,.1

Type RM Length L Ch R = 1 ,644.00  ,44,44,44
BEGIN DESCRIPTION:
12.044
END DESCRIPTION:
#Sta/Elev= 18
   -11.1   31.35    -7.1   31.35    -3.1   29.45     -.8   27.45       0   27.15
      .6   26.45      .6   25.85     1.6   25.85     1.6   26.45     2.2   27.15
     2.8   27.15     5.1   26.65     6.1   25.85     6.3   25.85     6.7   26.25
       7   26.25     7.2   26.05    17.2   26.05
#Mann= 3 , 0 , 0
   -11.1    .033       0       0    .033       0     2.2    .033       0
#XS Ineff= 2 , 0
               0   27.15     2.2           27.15
Permanent Ineff=
       F       F
Bank Sta=0,2.2
XS Rating Curve= 0
Exp/Cntr=.3,.1

Type RM Length L Ch R = 1 ,600.00  ,50,50,50
BEGIN DESCRIPTION:
12
END DESCRIPTION:
#Sta/Elev= 10
    -7.5   31.12      -5   28.62      -3   28.62       0   26.12       3   24.42
     3.7   24.42     5.1   25.72     7.9   25.72     8.4   25.42    18.4   25.42
#Mann= 3 , 0 , 0
    -7.5    .033       0       0    .033       0     5.1    .033       0
#XS Ineff= 2 , 0
               0   26.12     5.1           25.72
Permanent Ineff=
       F       F
Bank Sta=0,5.1
XS Rating Curve= 0
Exp/Cntr=.3,.1

Type RM Length L Ch R = 1 ,550.00  ,19,19,19
BEGIN DESCRIPTION:
11
END DESCRIPTION:
#Sta/Elev= 11
      -6   29.84      -4   28.34      -2   27.04       0   25.24     2.1   23.44
     3.5   23.44     4.3   24.64     5.6   24.84     8.6   24.84     9.4   24.14
    19.4   24.14
#Mann= 3 , 0 , 0
      -6    .033       0       0    .033       0     5.6    .033       0
#XS Ineff= 2 , 0
               0   25.24     5.6           24.84
Permanent Ineff=
       F       F
Bank Sta=0,5.6
XS Rating Curve= 0
Exp/Cntr=.3,.1

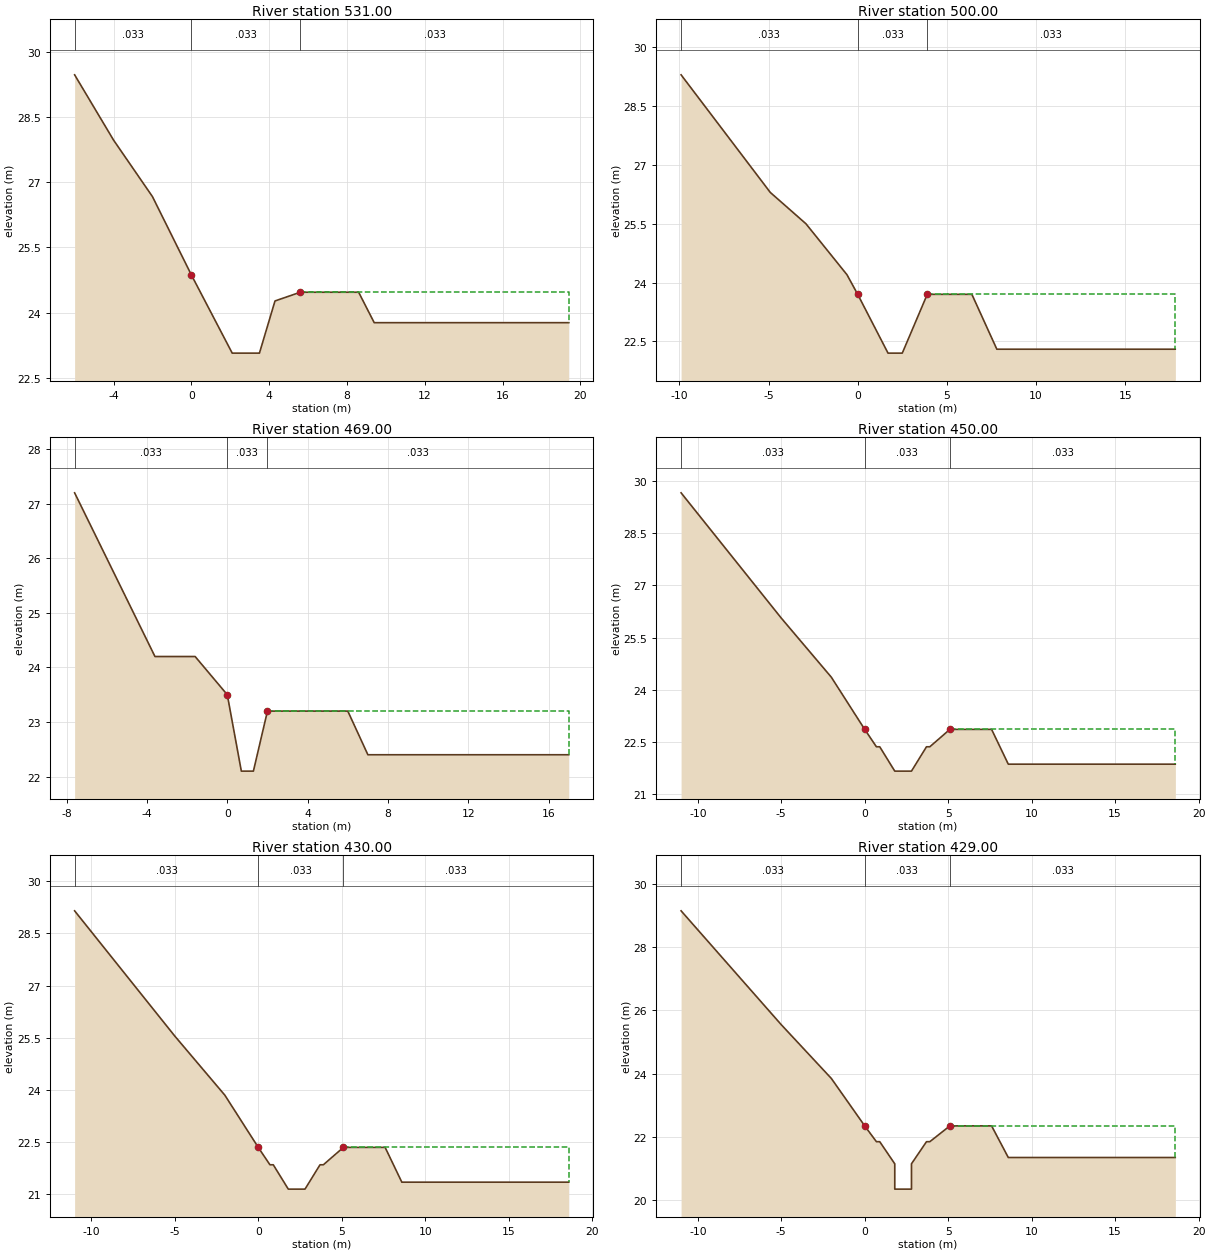
Type RM Length L Ch R = 1 ,531.00  ,31,31,31
BEGIN DESCRIPTION:
10.031
END DESCRIPTION:
#Sta/Elev= 11
      -6   29.47      -4   27.97      -2   26.67       0   24.87     2.1   23.07
     3.5   23.07     4.3   24.27     5.6   24.47     8.6   24.47     9.4   23.77
    19.4   23.77
#Mann= 3 , 0 , 0
      -6    .033       0       0    .033       0     5.6    .033       0
#XS Ineff= 2 , 0
               0   24.87     5.6           24.47
Permanent Ineff=
       F       F
Bank Sta=0,5.6
XS Rating Curve= 0
Exp/Cntr=.3,.1

Type RM Length L Ch R = 1 ,500.00  ,31,31,31
BEGIN DESCRIPTION:
10
END DESCRIPTION:
#Sta/Elev= 12
    -9.9    29.3    -7.4    27.8    -4.9    26.3    -2.9    25.5     -.6    24.2
       0    23.7     1.7    22.2     2.5    22.2     3.9    23.7     6.4    23.7
     7.8    22.3    17.8    22.3
#Mann= 3 , 0 , 0
    -9.9    .033       0       0    .033       0     3.9    .033       0
#XS Ineff= 2 , 0
               0    23.7     3.9            23.7
Permanent Ineff=
       F       F
Bank Sta=0,3.9
XS Rating Curve= 0
Exp/Cntr=.3,.1

Type RM Length L Ch R = 1 ,469.00  ,19,19,19
BEGIN DESCRIPTION:
9.019
END DESCRIPTION:
#Sta/Elev= 12
    -7.6    27.2    -5.6    25.7    -3.6    24.2    -1.6    24.2       0    23.5
      .7    22.1     1.3    22.1       2    23.2       3    23.2       6    23.2
       7    22.4      17    22.4
#Mann= 3 , 0 , 0
    -7.6    .033       0       0    .033       0       2    .033       0
#XS Ineff= 2 , 0
               0    23.5       2            23.2
Permanent Ineff=
       F       F
Bank Sta=0,2
XS Rating Curve= 0
Exp/Cntr=.3,.1

Type RM Length L Ch R = 1 ,450.00  ,20,20,20
BEGIN DESCRIPTION:
9
END DESCRIPTION:
#Sta/Elev= 15
     -11   29.66      -8   27.86      -5   26.06      -2   24.36       0   22.86
      .7   22.36      .9   22.36     1.8   21.66     2.8   21.66     3.7   22.36
     3.9   22.36     5.1   22.86     7.6   22.86     8.6   21.86    18.6   21.86
#Mann= 3 , 0 , 0
     -11    .033       0       0    .033       0     5.1    .033       0
#XS Ineff= 2 , 0
               0   22.86     5.1           22.86
Permanent Ineff=
       F       F
Bank Sta=0,5.1
XS Rating Curve= 0
Exp/Cntr=.3,.1

Type RM Length L Ch R = 1 ,430.00  ,1,1,1
BEGIN DESCRIPTION:
8.03
END DESCRIPTION:
#Sta/Elev= 15
     -11   29.15      -8   27.35      -5   25.55      -2   23.85       0   22.35
      .7   21.85      .9   21.85     1.8   21.15     2.8   21.15     3.7   21.85
     3.9   21.85     5.1   22.35     7.6   22.35     8.6   21.35    18.6   21.35
#Mann= 3 , 0 , 0
     -11    .033       0       0    .033       0     5.1    .033       0
#XS Ineff= 2 , 0
               0   22.35     5.1           22.35
Permanent Ineff=
       F       F
Bank Sta=0,5.1
XS Rating Curve= 0
Exp/Cntr=.3,.1

Type RM Length L Ch R = 1 ,429.00  ,29,29,29
BEGIN DESCRIPTION:
8.029
END DESCRIPTION:
#Sta/Elev= 17
     -11   29.15      -8   27.35      -5   25.55      -2   23.85       0   22.35
      .7   21.85      .9   21.85     1.8   21.15     1.8   20.35     2.8   20.35
     2.8   21.15     3.7   21.85     3.9   21.85     5.1   22.35     7.6   22.35
     8.6   21.35    18.6   21.35
#Mann= 3 , 0 , 0
     -11    .033       0       0    .033       0     5.1    .033       0
#XS Ineff= 2 , 0
               0   22.35     5.1           22.35
Permanent Ineff=
       F       F
Bank Sta=0,5.1
XS Rating Curve= 0
Exp/Cntr=.3,.1

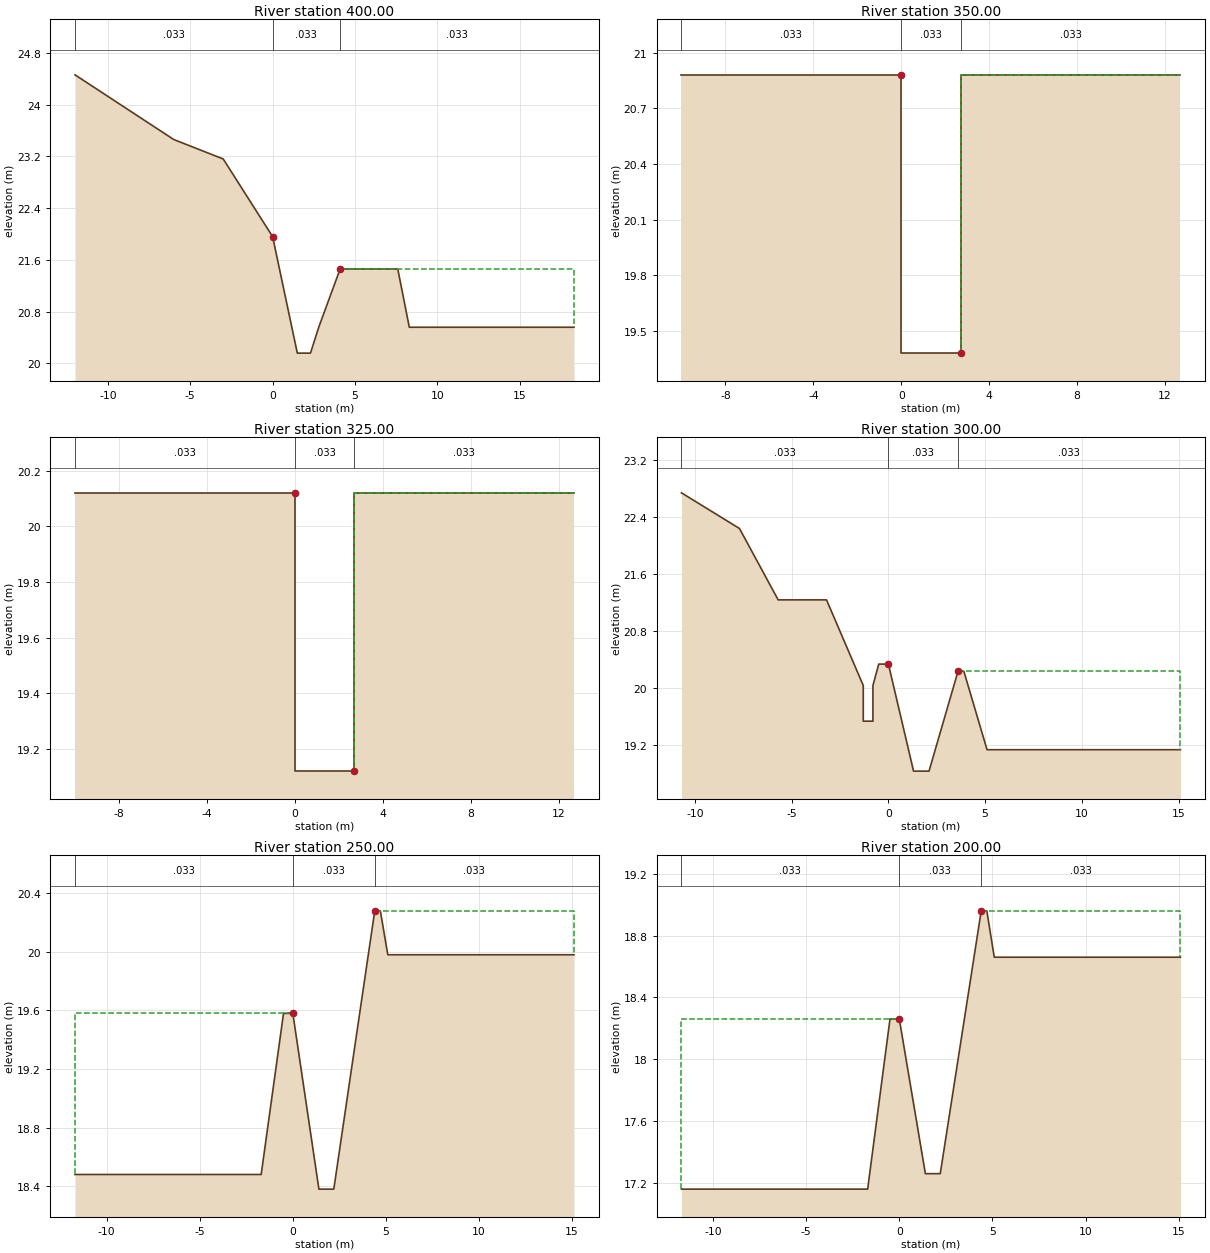
Type RM Length L Ch R = 1 ,400.00  ,50,50,50
BEGIN DESCRIPTION:
8
END DESCRIPTION:
#Sta/Elev= 12
     -12   24.46      -9   23.96      -6   23.46      -3   23.16       0   21.96
     1.5   20.16     2.3   20.16     2.8   20.56     4.1   21.46     7.6   21.46
     8.3   20.56    18.3   20.56
#Mann= 3 , 0 , 0
     -12    .033       0       0    .033       0     4.1    .033       0
#XS Ineff= 2 , 0
               0   21.96     4.1           21.46
Permanent Ineff=
       F       F
Bank Sta=0,4.1
XS Rating Curve= 0
Exp/Cntr=.3,.1

Type RM Length L Ch R = 1 ,350.00  ,25,25,25
BEGIN DESCRIPTION:
7
END DESCRIPTION:
#Sta/Elev= 6
     -10   20.88       0   20.88       0   19.38     2.7   19.38     2.7   20.88
    12.7   20.88
#Mann= 3 , 0 , 0
     -10    .033       0       0    .033       0     2.7    .033       0
#XS Ineff= 2 , 0
               0   20.88     2.7           20.88
Permanent Ineff=
       F       F
Bank Sta=0,2.7
XS Rating Curve= 0
Exp/Cntr=.3,.1

Type RM Length L Ch R = 1 ,325.00  ,25,25,25
BEGIN DESCRIPTION:
6.025
END DESCRIPTION:
#Sta/Elev= 6
     -10   20.12       0   20.12       0   19.12     2.7   19.12     2.7   20.12
    12.7   20.12
#Mann= 3 , 0 , 0
     -10    .033       0       0    .033       0     2.7    .033       0
#XS Ineff= 2 , 0
               0   20.12     2.7           20.12
Permanent Ineff=
       F       F
Bank Sta=0,2.7
XS Rating Curve= 0
Exp/Cntr=.3,.1

Type RM Length L Ch R = 1 ,300.00  ,50,50,50
BEGIN DESCRIPTION:
6
END DESCRIPTION:
#Sta/Elev= 16
   -10.7   22.74    -7.7   22.24    -5.7   21.24    -3.2   21.24    -1.3   20.04
    -1.3   19.54     -.8   19.54     -.8   20.04     -.5   20.34       0   20.34
     1.3   18.84     2.1   18.84     3.6   20.24     3.9   20.24     5.1   19.14
    15.1   19.14
#Mann= 3 , 0 , 0
   -10.7    .033       0       0    .033       0     3.6    .033       0
#XS Ineff= 2 , 0
               0   20.34     3.6           20.24
Permanent Ineff=
       F       F
Bank Sta=0,3.6
XS Rating Curve= 0
Exp/Cntr=.3,.1

Type RM Length L Ch R = 1 ,250.00  ,50,50,50
BEGIN DESCRIPTION:
5
END DESCRIPTION:
#Sta/Elev= 10
   -11.7   18.48    -1.7   18.48     -.5   19.58       0   19.58     1.4   18.38
     2.2   18.38     4.4   20.28     4.7   20.28     5.1   19.98    15.1   19.98
#Mann= 3 , 0 , 0
   -11.7    .033       0       0    .033       0     4.4    .033       0
#XS Ineff= 2 , 0
               0   19.58     4.4           20.28
Permanent Ineff=
       F       F
Bank Sta=0,4.4
XS Rating Curve= 0
Exp/Cntr=.3,.1

Type RM Length L Ch R = 1 ,200.00  ,50,50,50
BEGIN DESCRIPTION:
4
END DESCRIPTION:
#Sta/Elev= 10
   -11.7   17.16    -1.7   17.16     -.5   18.26       0   18.26     1.4   17.26
     2.2   17.26     4.4   18.96     4.7   18.96     5.1   18.66    15.1   18.66
#Mann= 3 , 0 , 0
   -11.7    .033       0       0    .033       0     4.4    .033       0
#XS Ineff= 2 , 0
               0   18.26     4.4           18.96
Permanent Ineff=
       F       F
Bank Sta=0,4.4
XS Rating Curve= 0
Exp/Cntr=.3,.1