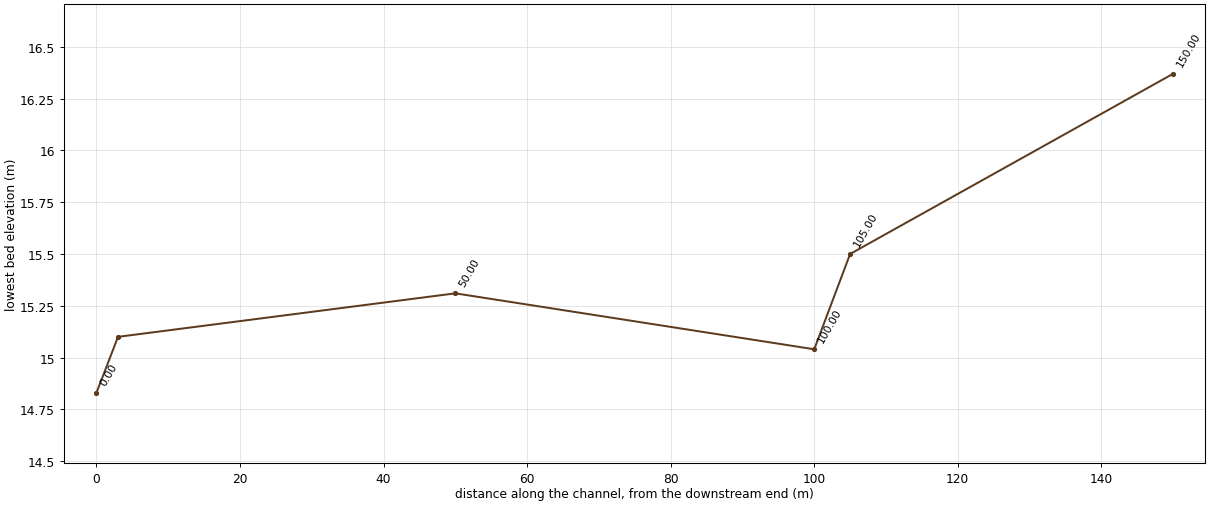
HEC-RAS study JJK.prj: JJK

--- JJK.g01 (geometry) --- (continued)

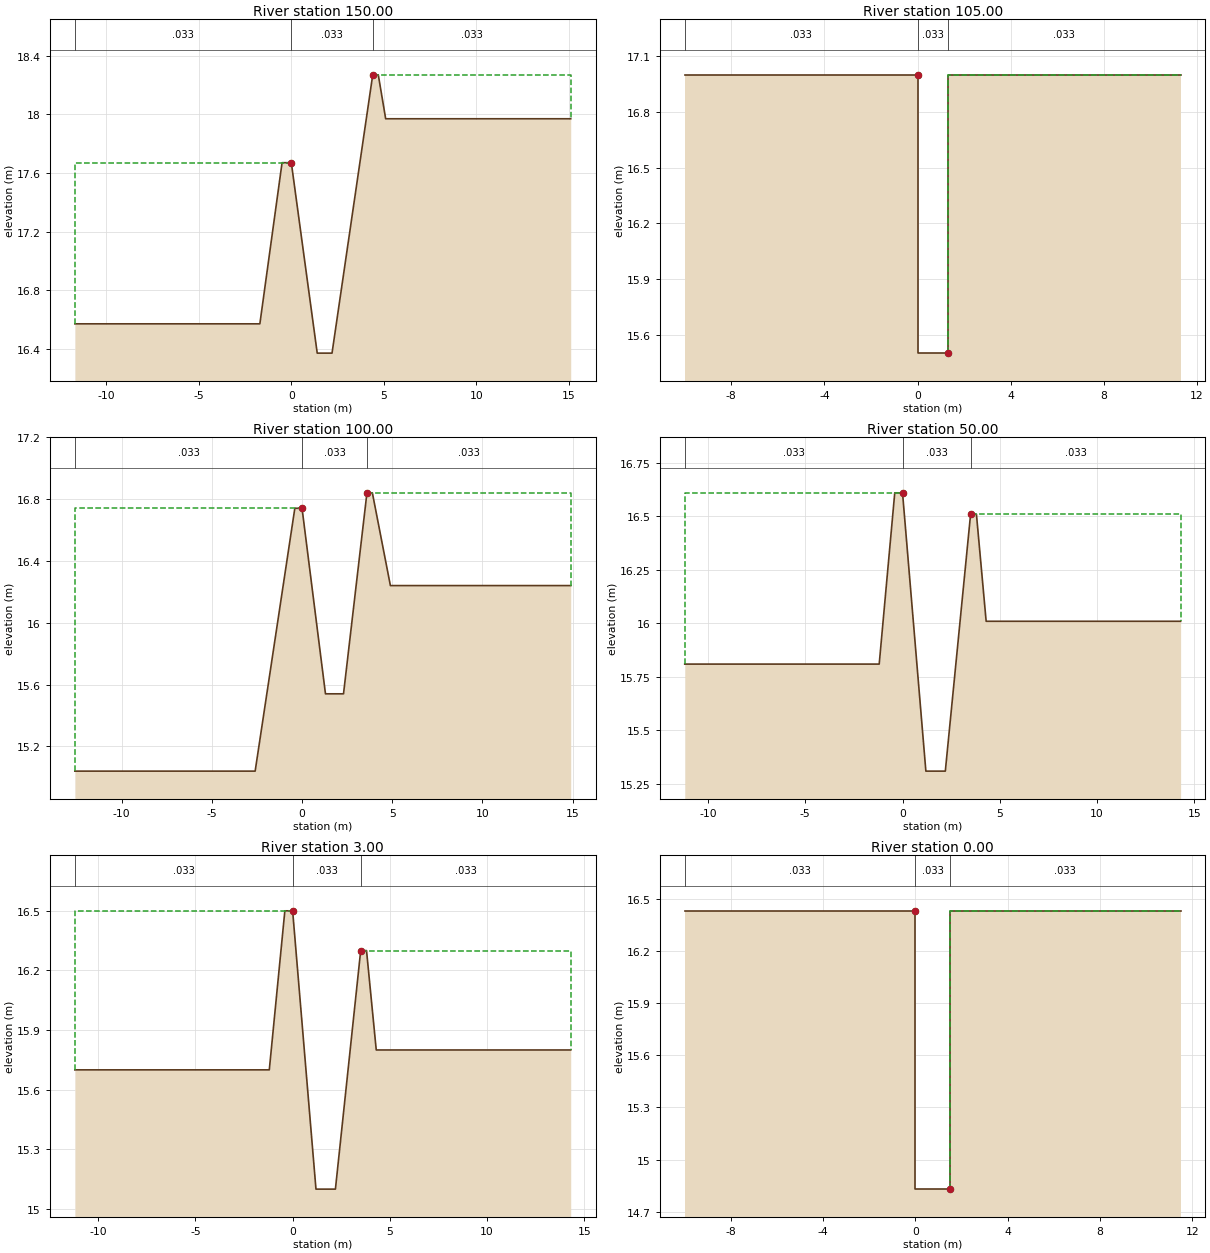
Type RM Length L Ch R = 1 ,150.00  ,45,45,45
BEGIN DESCRIPTION:
3
END DESCRIPTION:
#Sta/Elev= 10
   -11.7   16.57    -1.7   16.57     -.5   17.67       0   17.67     1.4   16.37
     2.2   16.37     4.4   18.27     4.7   18.27     5.1   17.97    15.1   17.97
#Mann= 3 , 0 , 0
   -11.7    .033       0       0    .033       0     4.4    .033       0
#XS Ineff= 2 , 0
               0   17.67     4.4           18.27
Permanent Ineff=
       F       F
Bank Sta=0,4.4
XS Rating Curve= 0
Exp/Cntr=.3,.1

Type RM Length L Ch R = 1 ,105.00  ,5,5,5
BEGIN DESCRIPTION:
2.005
END DESCRIPTION:
#Sta/Elev= 6
     -10      17       0      17       0    15.5     1.3    15.5     1.3      17
    11.3      17
#Mann= 3 , 0 , 0
     -10    .033       0       0    .033       0     1.3    .033       0
#XS Ineff= 2 , 0
               0      17     1.3              17
Permanent Ineff=
       F       F
Bank Sta=0,1.3
XS Rating Curve= 0
Exp/Cntr=.3,.1

Type RM Length L Ch R = 1 ,100.00  ,50,50,50
BEGIN DESCRIPTION:
2
END DESCRIPTION:
#Sta/Elev= 10
   -12.6   15.04    -2.6   15.04     -.4   16.74       0   16.74     1.3   15.54
     2.3   15.54     3.6   16.84     3.9   16.84     4.9   16.24    14.9   16.24
#Mann= 3 , 0 , 0
   -12.6    .033       0       0    .033       0     3.6    .033       0
#XS Ineff= 2 , 0
               0   16.74     3.6           16.84
Permanent Ineff=
       F       F
Bank Sta=0,3.6
XS Rating Curve= 0
Exp/Cntr=.3,.1

Type RM Length L Ch R = 1 ,50.00   ,47,47,47
BEGIN DESCRIPTION:
1
END DESCRIPTION:
#Sta/Elev= 10
   -11.2   15.81    -1.2   15.81     -.4   16.61       0   16.61     1.2   15.31
     2.2   15.31     3.5   16.51     3.8   16.51     4.3   16.01    14.3   16.01
#Mann= 3 , 0 , 0
   -11.2    .033       0       0    .033       0     3.5    .033       0
#XS Ineff= 2 , 0
               0   16.61     3.5           16.51
Permanent Ineff=
       F       F
Bank Sta=0,3.5
XS Rating Curve= 0
Exp/Cntr=.3,.1

Type RM Length L Ch R = 1 ,3.00    ,3,3,3
BEGIN DESCRIPTION:
0.003
END DESCRIPTION:
#Sta/Elev= 10
   -11.2    15.7    -1.2    15.7     -.4    16.5       0    16.5     1.2    15.1
     2.2    15.1     3.5    16.3     3.8    16.3     4.3    15.8    14.3    15.8
#Mann= 3 , 0 , 0
   -11.2    .033       0       0    .033       0     3.5    .033       0
#XS Ineff= 2 , 0
               0    16.5     3.5            16.3
Permanent Ineff=
       F       F
Bank Sta=0,3.5
XS Rating Curve= 0
Exp/Cntr=.3,.1

Type RM Length L Ch R = 1 ,0.00    ,0,0,0
BEGIN DESCRIPTION:
0
END DESCRIPTION:
#Sta/Elev= 6
     -10   16.43       0   16.43       0   14.83     1.5   14.83     1.5   16.43
    11.5   16.43
#Mann= 3 , 0 , 0
     -10    .033       0       0    .033       0     1.5    .033       0
#XS Ineff= 2 , 0
               0   16.43     1.5           16.43
Permanent Ineff=
       F       F
Bank Sta=0,1.5
XS Rating Curve= 0
Exp/Cntr=.3,.1

Chan Stop Cuts=-1