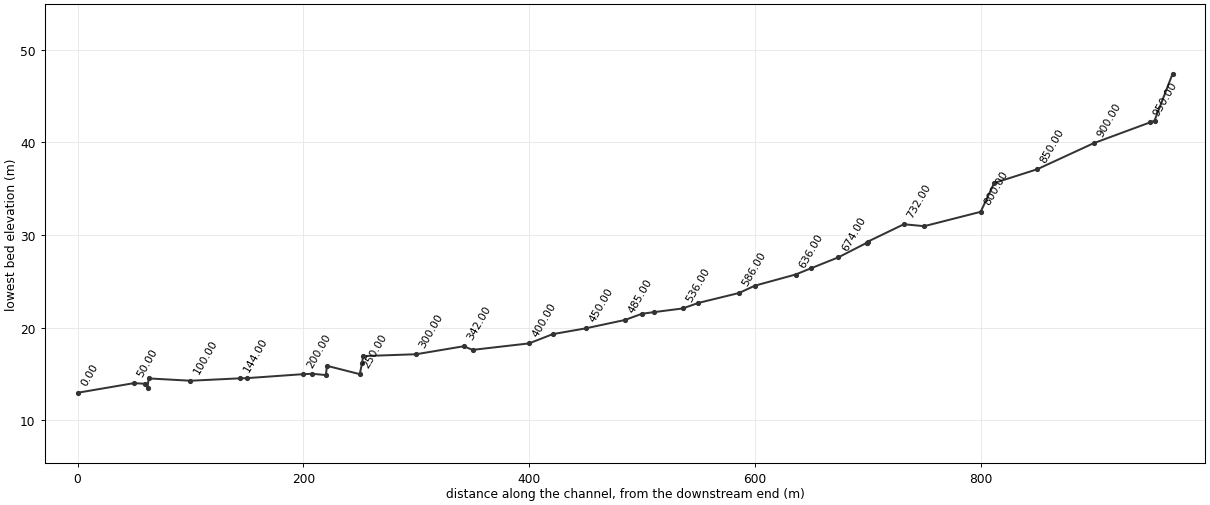
--- JANG.prj (project) ---

Proj Title=JANG
Current Plan=p01
Default Exp/Contr=.3,.1
SI Units
Geom File=g01
Flow File=f01
Plan File=p01
Y Axis Title=Elevation
X Axis Title(PF)=Main Channel Distance
X Axis Title(XS)=Station
BEGIN DESCRIPTION:
           BACK WATER COMPUTATION
      APPLICATION OF HEC-2 BY Samju Construction Engineering
      JANGDONG-STREEM : 30 YR
END DESCRIPTION:
DSS Export Rating Curves= 0
DSS Export Rating Curve Sorted= 0
DSS Export Volume Flow Curves= 0
DXF OffsetX= 0
DXF OffsetY= 0
DXF ScaleX= 1
DXF ScaleY= 10

--- JANG.p01 (plan) ---

Plan Title=Imported Plan 01
Version=Version 3.0.1  Mar 2001
Short Identifier=Imported Pla
Geom File=g01
Flow File=f01
Subcritical Flow
K Sum by GR= 0
Std Step Tol= 0.003
Critical Tol= 0.003
Num of Std Step Trials= 20
Max Error Tol= 0.1
Flow Tol Ratio= 0.001
Split Flow NTrial= 30
Split Flow Tol= 0.02
Split Flow Ratio= 0.02
Log Output Level= 0
Friction Slope Method= 1
Unsteady Friction Slope Method= 2
Parabolic Critical Depth
Global Vel Dist= 0 , 0 , 0
Global Log Level= 0
CheckData=True
Encroach Param=-1 ,0,0, 0
Computation Interval=1HOUR
Output Interval=1HOUR
Run HTab= 0
Run UNet= 0
Run PostProcess= 0
UNET Theta= 1
UNET ZTol= 0.02
UNET ZSATol= 0.1
UNET MxIter= 20
UNET MaxInSteps= 20
UNET DtIC= 0
UNET DtMin= 0
UNET MaxCRTS= 20
UNET WFStab= 2
UNET SFStab= 1
UNET WFX= 1
UNET SFX= 1
UNET Convert EG Bridges=-1
UNET Use Existing IB Tables=-1
Instantaneous Interval=1HOUR
Write IC File= 0
Write Velocity= 0
Write Detailed= 0

--- JANG.f01 (steady flow) ---

Flow Title=Imported Flow 01
Version=Version 3.0.1  Mar 2001
Number of Profiles= 5
Profile Names=10YR,20YR,30YR,50YR,80YR
River Rch & RM=RIVER-1,Reach-1         ,970.00
    8.61    9.49      10   10.64   11.24
Boundary for River Rch & Prof#=RIVER-1,Reach-1         , 1
Up Type= 0
Dn Type= 3
Dn Slope=.056
Boundary for River Rch & Prof#=RIVER-1,Reach-1         , 2
Up Type= 0
Dn Type= 3
Dn Slope=.056
Boundary for River Rch & Prof#=RIVER-1,Reach-1         , 3
Up Type= 0
Dn Type= 3
Dn Slope=.056
Boundary for River Rch & Prof#=RIVER-1,Reach-1         , 4
Up Type= 0
Dn Type= 3
Dn Slope=.056
Boundary for River Rch & Prof#=RIVER-1,Reach-1         , 5
Up Type= 0
Dn Type= 3
Dn Slope=.056
DSS Import GetInterval= 0
DSS Import GetPeak= 0
DSS Import FillOption= 0

--- JANG.g01 (geometry) ---

Geom Title=Imported Geom 01
Version=Version 3.0.1  Mar 2001

River Reach=RIVER-1         ,Reach-1
Reach XY= 2
              .5             .95              .5             .05

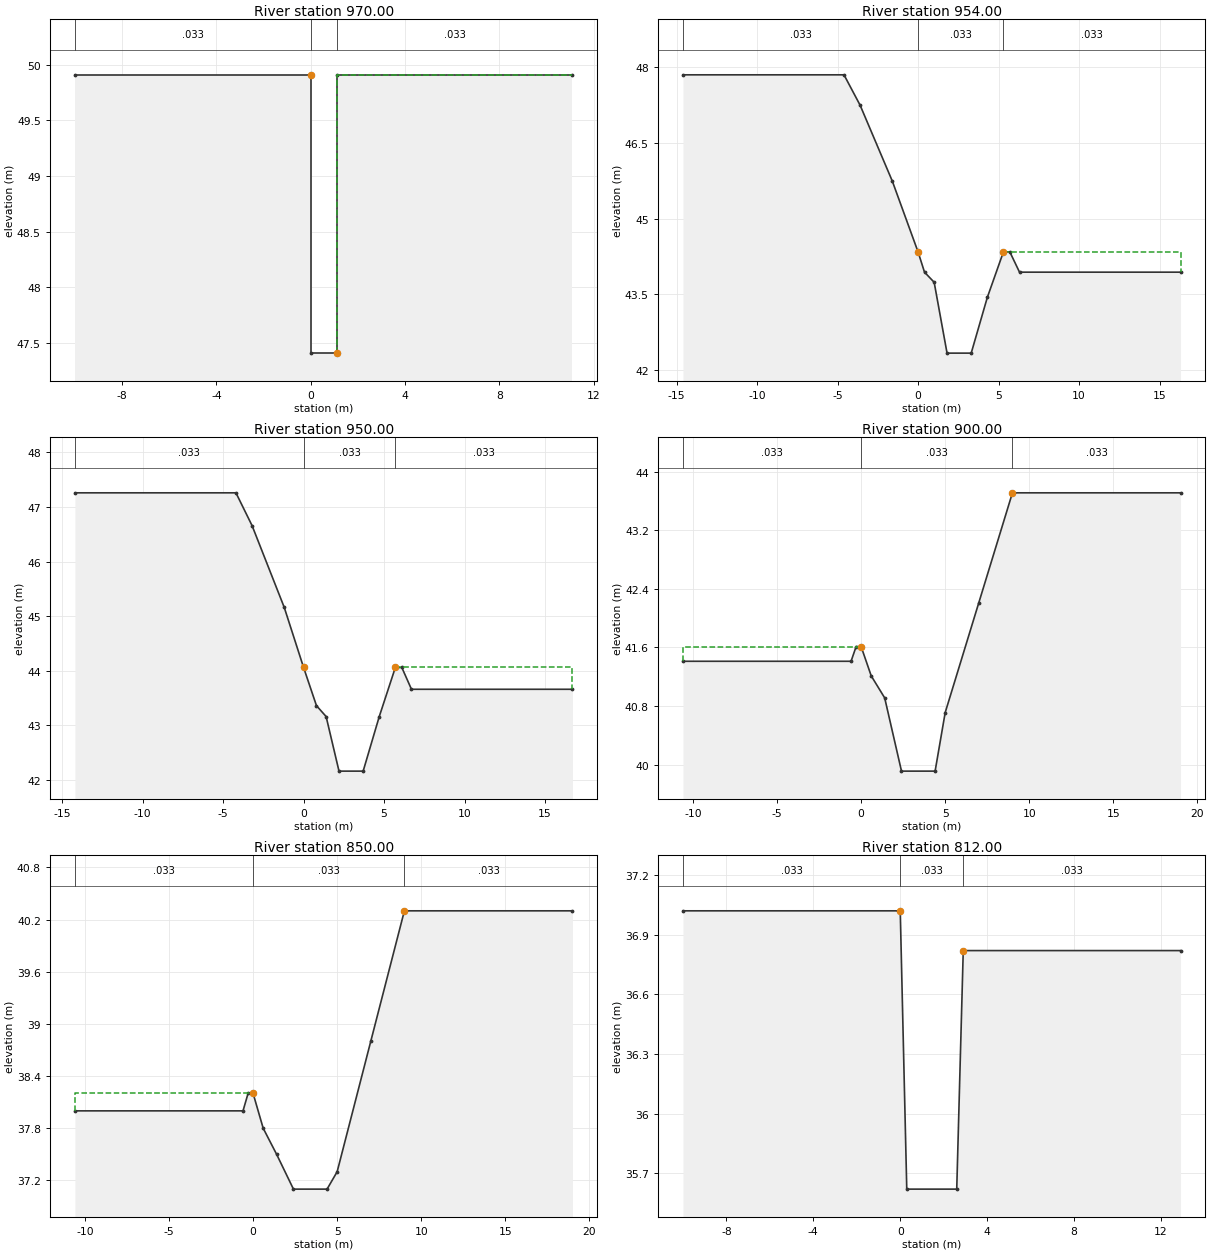
Type RM Length L Ch R = 1 ,970.00  ,16,16,16
BEGIN DESCRIPTION:
19.02
END DESCRIPTION:
#Sta/Elev= 6
     -10   49.91       0   49.91       0   47.41     1.1   47.41     1.1   49.91
    11.1   49.91
#Mann= 3 , 0 , 0
     -10    .033       0       0    .033       0     1.1    .033       0
#XS Ineff= 2 , 0
               0   49.91     1.1           49.91
Permanent Ineff=
       F       F
Bank Sta=0,1.1
XS Rating Curve= 0
Exp/Cntr=.3,.1

Type RM Length L Ch R = 1 ,954.00  ,4,4,4
BEGIN DESCRIPTION:
19.004
END DESCRIPTION:
#Sta/Elev= 14
   -14.6   47.84    -4.6   47.84    -3.6   47.24    -1.6   45.74       0   44.34
      .4   43.94       1   43.74     1.8   42.34     3.3   42.34     4.3   43.44
     5.3   44.34     5.7   44.34     6.3   43.94    16.3   43.94
#Mann= 3 , 0 , 0
   -14.6    .033       0       0    .033       0     5.3    .033       0
#XS Ineff= 2 , 0
               0   44.34     5.3           44.34
Permanent Ineff=
       F       F
Bank Sta=0,5.3
XS Rating Curve= 0
Exp/Cntr=.3,.1

Type RM Length L Ch R = 1 ,950.00  ,50,50,50
BEGIN DESCRIPTION:
19
END DESCRIPTION:
#Sta/Elev= 14
   -14.2   47.26    -4.2   47.26    -3.2   46.66    -1.2   45.16       0   44.06
      .8   43.36     1.4   43.16     2.2   42.16     3.7   42.16     4.7   43.16
     5.7   44.06     6.1   44.06     6.7   43.66    16.7   43.66
#Mann= 3 , 0 , 0
   -14.2    .033       0       0    .033       0     5.7    .033       0
#XS Ineff= 2 , 0
               0   44.06     5.7           44.06
Permanent Ineff=
       F       F
Bank Sta=0,5.7
XS Rating Curve= 0
Exp/Cntr=.3,.1

Type RM Length L Ch R = 1 ,900.00  ,50,50,50
BEGIN DESCRIPTION:
18
END DESCRIPTION:
#Sta/Elev= 12
   -10.6   41.41     -.6   41.41     -.3   41.61       0   41.61      .6   41.21
     1.4   40.91     2.4   39.91     4.4   39.91       5   40.71       7   42.21
       9   43.71      19   43.71
#Mann= 3 , 0 , 0
   -10.6    .033       0       0    .033       0       9    .033       0
#XS Ineff= 2 , 0
               0   41.61       9           43.71
Permanent Ineff=
       F       F
Bank Sta=0,9
XS Rating Curve= 0
Exp/Cntr=.3,.1

Type RM Length L Ch R = 1 ,850.00  ,38,38,38
BEGIN DESCRIPTION:
17
END DESCRIPTION:
#Sta/Elev= 12
   -10.6      38     -.6      38     -.3    38.2       0    38.2      .6    37.8
     1.4    37.5     2.4    37.1     4.4    37.1       5    37.3       7    38.8
       9    40.3      19    40.3
#Mann= 3 , 0 , 0
   -10.6    .033       0       0    .033       0       9    .033       0
#XS Ineff= 2 , 0
               0    38.2       9            40.3
Permanent Ineff=
       F       F
Bank Sta=0,9
XS Rating Curve= 0
Exp/Cntr=.3,.1

Type RM Length L Ch R = 1 ,812.00  ,12,12,12
BEGIN DESCRIPTION:
16.012
END DESCRIPTION:
#Sta/Elev= 6
     -10   37.02       0   37.02      .3   35.62     2.6   35.62     2.9   36.82
    12.9   36.82
#Mann= 3 , 0 , 0
     -10    .033       0       0    .033       0     2.9    .033       0
#XS Ineff= 2 , 0
               0   37.02     2.9           36.82
Permanent Ineff=
       F       F
Bank Sta=0,2.9
XS Rating Curve= 0
Exp/Cntr=.3,.1

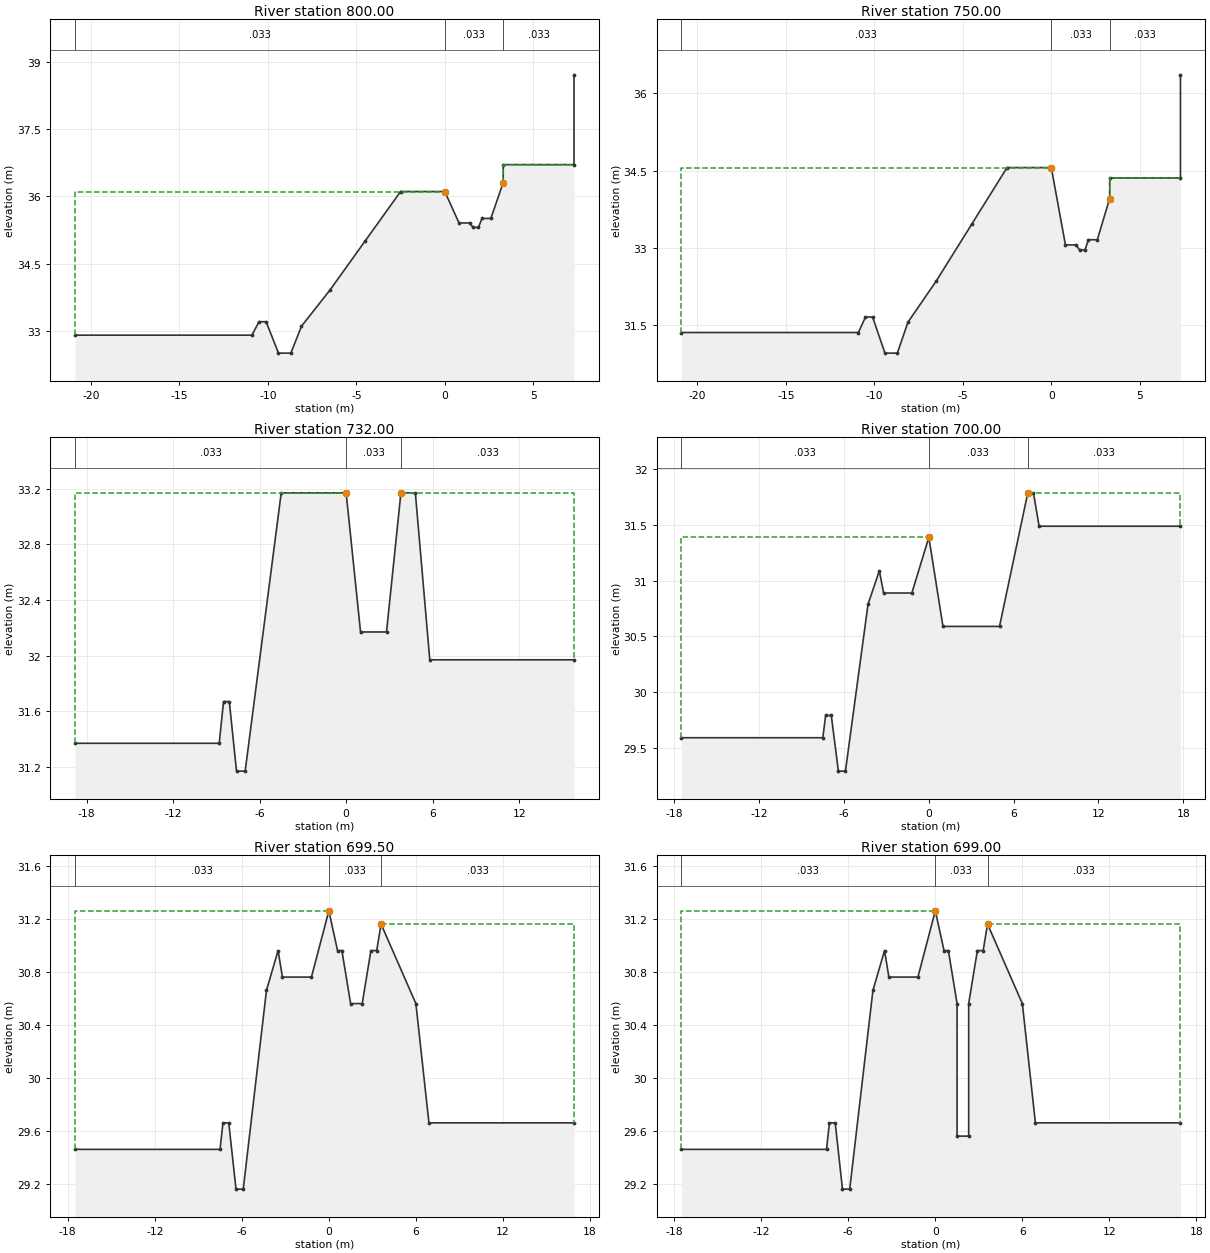
Type RM Length L Ch R = 1 ,800.00  ,50,50,50
BEGIN DESCRIPTION:
16
END DESCRIPTION:
#Sta/Elev= 21
   -20.9   32.91   -10.9   32.91   -10.5   33.21   -10.1   33.21    -9.4   32.51
    -8.7   32.51    -8.1   33.11    -6.5   33.91    -4.5   35.01    -2.5   36.11
       0   36.11      .8   35.41     1.4   35.41     1.6   35.31     1.9   35.31
     2.1   35.51     2.6   35.51     3.3   36.31     3.3   36.71     7.3   36.71
     7.3   38.71
#Mann= 3 , 0 , 0
   -20.9    .033       0       0    .033       0     3.3    .033       0
#XS Ineff= 2 , 0
               0   36.11     3.3           36.71
Permanent Ineff=
       F       F
Bank Sta=0,3.3
XS Rating Curve= 0
Exp/Cntr=.3,.1

Type RM Length L Ch R = 1 ,750.00  ,18,18,18
BEGIN DESCRIPTION:
15
END DESCRIPTION:
#Sta/Elev= 21
   -20.9   31.36   -10.9   31.36   -10.5   31.66   -10.1   31.66    -9.4   30.96
    -8.7   30.96    -8.1   31.56    -6.5   32.36    -4.5   33.46    -2.5   34.56
       0   34.56      .8   33.06     1.4   33.06     1.6   32.96     1.9   32.96
     2.1   33.16     2.6   33.16     3.3   33.96     3.3   34.36     7.3   34.36
     7.3   36.36
#Mann= 3 , 0 , 0
   -20.9    .033       0       0    .033       0     3.3    .033       0
#XS Ineff= 2 , 0
               0   34.56     3.3           34.36
Permanent Ineff=
       F       F
Bank Sta=0,3.3
XS Rating Curve= 0
Exp/Cntr=.3,.1

Type RM Length L Ch R = 1 ,732.00  ,32,32,32
BEGIN DESCRIPTION:
14.032
END DESCRIPTION:
#Sta/Elev= 14
   -18.8   31.37    -8.8   31.37    -8.5   31.67    -8.1   31.67    -7.6   31.17
      -7   31.17    -4.5   33.17       0   33.17       1   32.17     2.8   32.17
     3.8   33.17     4.8   33.17     5.8   31.97    15.8   31.97
#Mann= 3 , 0 , 0
   -18.8    .033       0       0    .033       0     3.8    .033       0
#XS Ineff= 2 , 0
               0   33.17     3.8           33.17
Permanent Ineff=
       F       F
Bank Sta=0,3.8
XS Rating Curve= 0
Exp/Cntr=.3,.1

Type RM Length L Ch R = 1 ,700.00  ,.5,.5,.5
BEGIN DESCRIPTION:
14
END DESCRIPTION:
#Sta/Elev= 17
   -17.5   29.59    -7.5   29.59    -7.3   29.79    -6.9   29.79    -6.4   29.29
    -5.9   29.29    -4.3   30.79    -3.5   31.09    -3.2   30.89    -1.2   30.89
       0   31.39       1   30.59       5   30.59       7   31.79     7.4   31.79
     7.8   31.49    17.8   31.49
#Mann= 3 , 0 , 0
   -17.5    .033       0       0    .033       0       7    .033       0
#XS Ineff= 2 , 0
               0   31.39       7           31.79
Permanent Ineff=
       F       F
Bank Sta=0,7
XS Rating Curve= 0
Exp/Cntr=.3,.1

Type RM Length L Ch R = 1 ,699.50  ,.5,.5,.5
BEGIN DESCRIPTION:
13.495
END DESCRIPTION:
#Sta/Elev= 21
   -17.5   29.46    -7.5   29.46    -7.3   29.66    -6.9   29.66    -6.4   29.16
    -5.9   29.16    -4.3   30.66    -3.5   30.96    -3.2   30.76    -1.2   30.76
       0   31.26      .6   30.96      .9   30.96     1.5   30.56     2.3   30.56
     2.9   30.96     3.3   30.96     3.6   31.16       6   30.56     6.9   29.66
    16.9   29.66
#Mann= 3 , 0 , 0
   -17.5    .033       0       0    .033       0     3.6    .033       0
#XS Ineff= 2 , 0
               0   31.26     3.6           31.16
Permanent Ineff=
       F       F
Bank Sta=0,3.6
XS Rating Curve= 0
Exp/Cntr=.3,.1

Type RM Length L Ch R = 1 ,699.00  ,25,25,25
BEGIN DESCRIPTION:
13.049
END DESCRIPTION:
#Sta/Elev= 23
   -17.5   29.46    -7.5   29.46    -7.3   29.66    -6.9   29.66    -6.4   29.16
    -5.9   29.16    -4.3   30.66    -3.5   30.96    -3.2   30.76    -1.2   30.76
       0   31.26      .6   30.96      .9   30.96     1.5   30.56     1.5   29.56
     2.3   29.56     2.3   30.56     2.9   30.96     3.3   30.96     3.6   31.16
       6   30.56     6.9   29.66    16.9   29.66
#Mann= 3 , 0 , 0
   -17.5    .033       0       0    .033       0     3.6    .033       0
#XS Ineff= 2 , 0
               0   31.26     3.6           31.16
Permanent Ineff=
       F       F
Bank Sta=0,3.6
XS Rating Curve= 0
Exp/Cntr=.3,.1

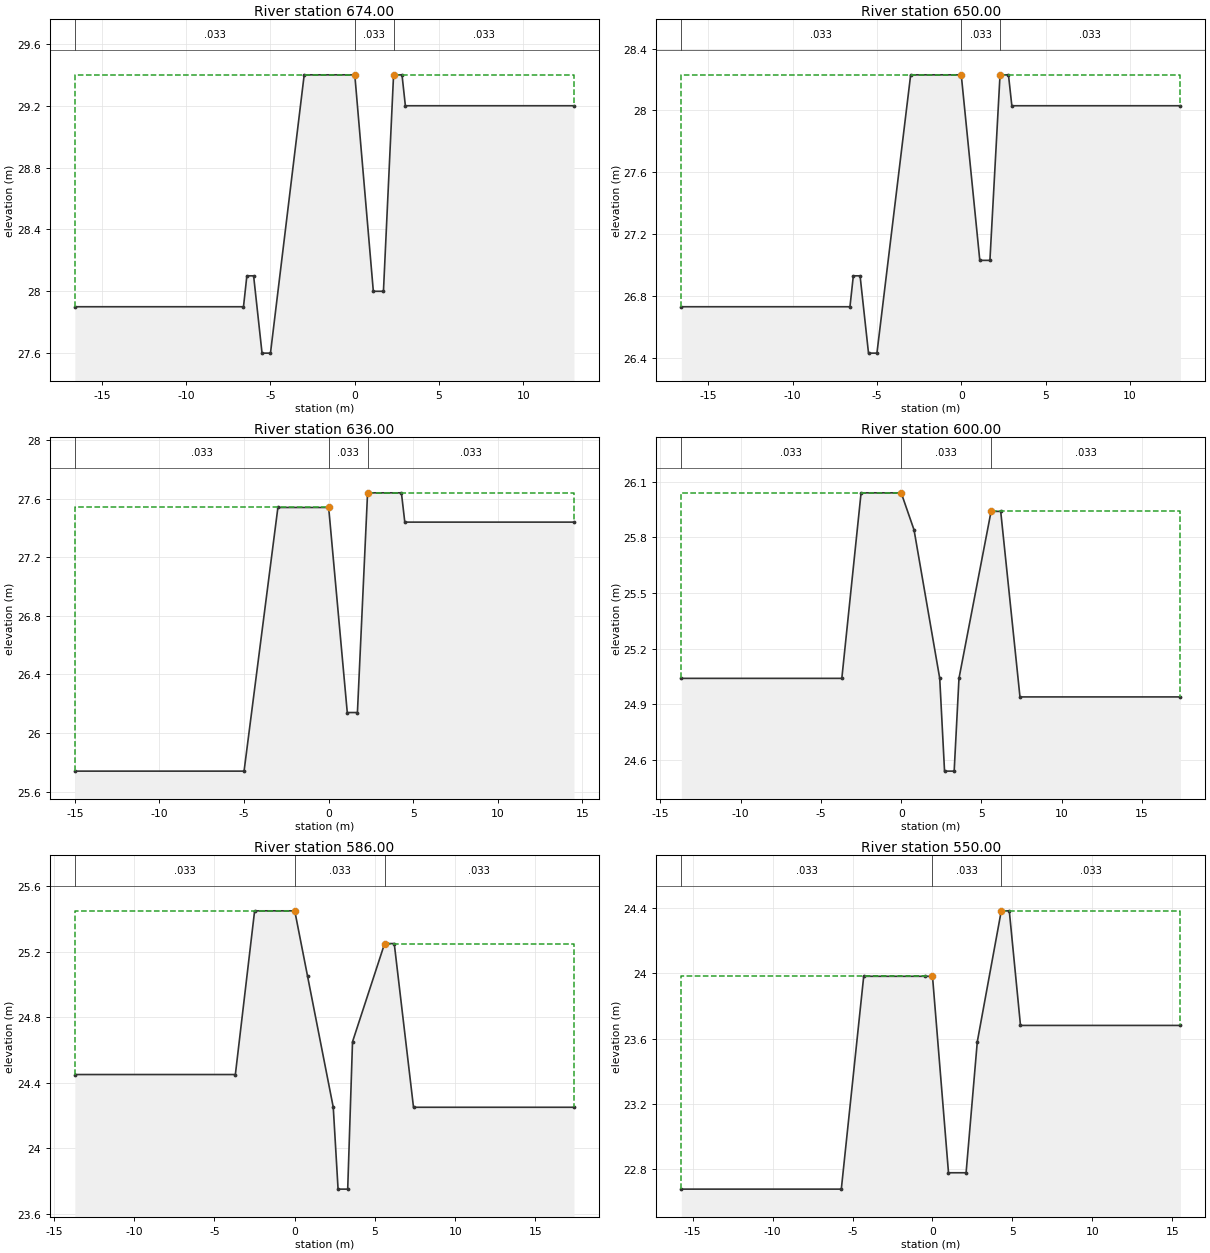
Type RM Length L Ch R = 1 ,674.00  ,24,24,24
BEGIN DESCRIPTION:
13.024
END DESCRIPTION:
#Sta/Elev= 14
   -16.6    27.9    -6.6    27.9    -6.4    28.1      -6    28.1    -5.5    27.6
      -5    27.6      -3    29.4       0    29.4     1.1      28     1.7      28
     2.3    29.4     2.8    29.4       3    29.2      13    29.2
#Mann= 3 , 0 , 0
   -16.6    .033       0       0    .033       0     2.3    .033       0
#XS Ineff= 2 , 0
               0    29.4     2.3            29.4
Permanent Ineff=
       F       F
Bank Sta=0,2.3
XS Rating Curve= 0
Exp/Cntr=.3,.1

Type RM Length L Ch R = 1 ,650.00  ,14,14,14
BEGIN DESCRIPTION:
13
END DESCRIPTION:
#Sta/Elev= 14
   -16.6   26.73    -6.6   26.73    -6.4   26.93      -6   26.93    -5.5   26.43
      -5   26.43      -3   28.23       0   28.23     1.1   27.03     1.7   27.03
     2.3   28.23     2.8   28.23       3   28.03      13   28.03
#Mann= 3 , 0 , 0
   -16.6    .033       0       0    .033       0     2.3    .033       0
#XS Ineff= 2 , 0
               0   28.23     2.3           28.23
Permanent Ineff=
       F       F
Bank Sta=0,2.3
XS Rating Curve= 0
Exp/Cntr=.3,.1

Type RM Length L Ch R = 1 ,636.00  ,36,36,36
BEGIN DESCRIPTION:
12.036
END DESCRIPTION:
#Sta/Elev= 10
     -15   25.74      -5   25.74      -3   27.54       0   27.54     1.1   26.14
     1.7   26.14     2.3   27.64     4.3   27.64     4.5   27.44    14.5   27.44
#Mann= 3 , 0 , 0
     -15    .033       0       0    .033       0     2.3    .033       0
#XS Ineff= 2 , 0
               0   27.54     2.3           27.64
Permanent Ineff=
       F       F
Bank Sta=0,2.3
XS Rating Curve= 0
Exp/Cntr=.3,.1

Type RM Length L Ch R = 1 ,600.00  ,14,14,14
BEGIN DESCRIPTION:
12
END DESCRIPTION:
#Sta/Elev= 13
   -13.7   25.04    -3.7   25.04    -2.5   26.04       0   26.04      .8   25.84
     2.4   25.04     2.7   24.54     3.3   24.54     3.6   25.04     5.6   25.94
     6.2   25.94     7.4   24.94    17.4   24.94
#Mann= 3 , 0 , 0
   -13.7    .033       0       0    .033       0     5.6    .033       0
#XS Ineff= 2 , 0
               0   26.04     5.6           25.94
Permanent Ineff=
       F       F
Bank Sta=0,5.6
XS Rating Curve= 0
Exp/Cntr=.3,.1

Type RM Length L Ch R = 1 ,586.00  ,36,36,36
BEGIN DESCRIPTION:
11.036
END DESCRIPTION:
#Sta/Elev= 13
   -13.7   24.45    -3.7   24.45    -2.5   25.45       0   25.45      .8   25.05
     2.4   24.25     2.7   23.75     3.3   23.75     3.6   24.65     5.6   25.25
     6.2   25.25     7.4   24.25    17.4   24.25
#Mann= 3 , 0 , 0
   -13.7    .033       0       0    .033       0     5.6    .033       0
#XS Ineff= 2 , 0
               0   25.45     5.6           25.25
Permanent Ineff=
       F       F
Bank Sta=0,5.6
XS Rating Curve= 0
Exp/Cntr=.3,.1

Type RM Length L Ch R = 1 ,550.00  ,14,14,14
BEGIN DESCRIPTION:
11
END DESCRIPTION:
#Sta/Elev= 12
   -15.7   22.68    -5.7   22.68    -4.3   23.98     -.5   23.98       0   23.98
       1   22.78     2.1   22.78     2.8   23.58     4.3   24.38     4.8   24.38
     5.5   23.68    15.5   23.68
#Mann= 3 , 0 , 0
   -15.7    .033       0       0    .033       0     4.3    .033       0
#XS Ineff= 2 , 0
               0   23.98     4.3           24.38
Permanent Ineff=
       F       F
Bank Sta=0,4.3
XS Rating Curve= 0
Exp/Cntr=.3,.1

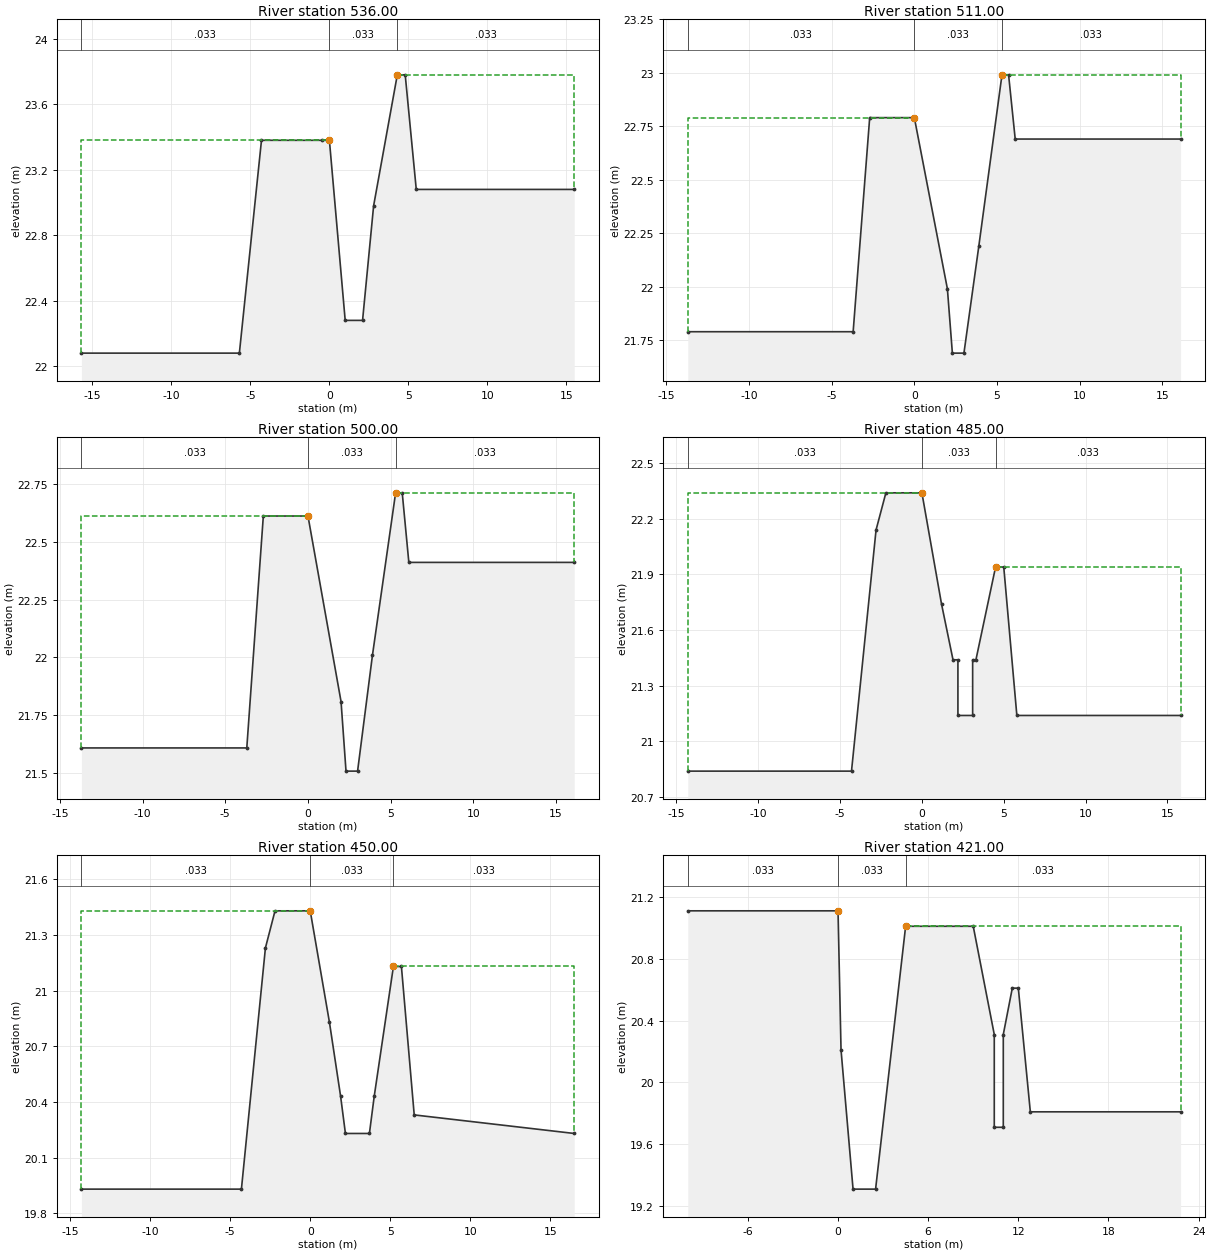
Type RM Length L Ch R = 1 ,536.00  ,25,25,25
BEGIN DESCRIPTION:
10.036
END DESCRIPTION:
#Sta/Elev= 12
   -15.7   22.08    -5.7   22.08    -4.3   23.38     -.5   23.38       0   23.38
       1   22.28     2.1   22.28     2.8   22.98     4.3   23.78     4.8   23.78
     5.5   23.08    15.5   23.08
#Mann= 3 , 0 , 0
   -15.7    .033       0       0    .033       0     4.3    .033       0
#XS Ineff= 2 , 0
               0   23.38     4.3           23.78
Permanent Ineff=
       F       F
Bank Sta=0,4.3
XS Rating Curve= 0
Exp/Cntr=.3,.1

Type RM Length L Ch R = 1 ,511.00  ,11,11,11
BEGIN DESCRIPTION:
10.011
END DESCRIPTION:
#Sta/Elev= 12
   -13.7   21.79    -3.7   21.79    -2.7   22.79       0   22.79       2   21.99
     2.3   21.69       3   21.69     3.9   22.19     5.3   22.99     5.7   22.99
     6.1   22.69    16.1   22.69
#Mann= 3 , 0 , 0
   -13.7    .033       0       0    .033       0     5.3    .033       0
#XS Ineff= 2 , 0
               0   22.79     5.3           22.99
Permanent Ineff=
       F       F
Bank Sta=0,5.3
XS Rating Curve= 0
Exp/Cntr=.3,.1

Type RM Length L Ch R = 1 ,500.00  ,15,15,15
BEGIN DESCRIPTION:
10
END DESCRIPTION:
#Sta/Elev= 12
   -13.7   21.61    -3.7   21.61    -2.7   22.61       0   22.61       2   21.81
     2.3   21.51       3   21.51     3.9   22.01     5.3   22.71     5.7   22.71
     6.1   22.41    16.1   22.41
#Mann= 3 , 0 , 0
   -13.7    .033       0       0    .033       0     5.3    .033       0
#XS Ineff= 2 , 0
               0   22.61     5.3           22.71
Permanent Ineff=
       F       F
Bank Sta=0,5.3
XS Rating Curve= 0
Exp/Cntr=.3,.1

Type RM Length L Ch R = 1 ,485.00  ,35,35,35
BEGIN DESCRIPTION:
9.035
END DESCRIPTION:
#Sta/Elev= 16
   -14.3   20.84    -4.3   20.84    -2.8   22.14    -2.2   22.34       0   22.34
     1.2   21.74     1.9   21.44     2.2   21.44     2.2   21.14     3.1   21.14
     3.1   21.44     3.3   21.44     4.5   21.94       5   21.94     5.8   21.14
    15.8   21.14
#Mann= 3 , 0 , 0
   -14.3    .033       0       0    .033       0     4.5    .033       0
#XS Ineff= 2 , 0
               0   22.34     4.5           21.94
Permanent Ineff=
       F       F
Bank Sta=0,4.5
XS Rating Curve= 0
Exp/Cntr=.3,.1

Type RM Length L Ch R = 1 ,450.00  ,29,29,29
BEGIN DESCRIPTION:
9
END DESCRIPTION:
#Sta/Elev= 14
   -14.3   19.93    -4.3   19.93    -2.8   21.23    -2.2   21.43       0   21.43
     1.2   20.83     1.9   20.43     2.2   20.23     3.7   20.23       4   20.43
     5.2   21.13     5.7   21.13     6.5   20.33    16.5   20.23
#Mann= 3 , 0 , 0
   -14.3    .033       0       0    .033       0     5.2    .033       0
#XS Ineff= 2 , 0
               0   21.43     5.2           21.13
Permanent Ineff=
       F       F
Bank Sta=0,5.2
XS Rating Curve= 0
Exp/Cntr=.3,.1

Type RM Length L Ch R = 1 ,421.00  ,21,21,21
BEGIN DESCRIPTION:
8.021
END DESCRIPTION:
#Sta/Elev= 15
     -10   21.11       0   21.11      .2   20.21       1   19.31     2.5   19.31
     4.5   21.01       9   21.01    10.4   20.31    10.4   19.71      11   19.71
      11   20.31    11.6   20.61      12   20.61    12.8   19.81    22.8   19.81
#Mann= 3 , 0 , 0
     -10    .033       0       0    .033       0     4.5    .033       0
#XS Ineff= 2 , 0
               0   21.11     4.5           21.01
Permanent Ineff=
       F       F
Bank Sta=0,4.5
XS Rating Curve= 0
Exp/Cntr=.3,.1

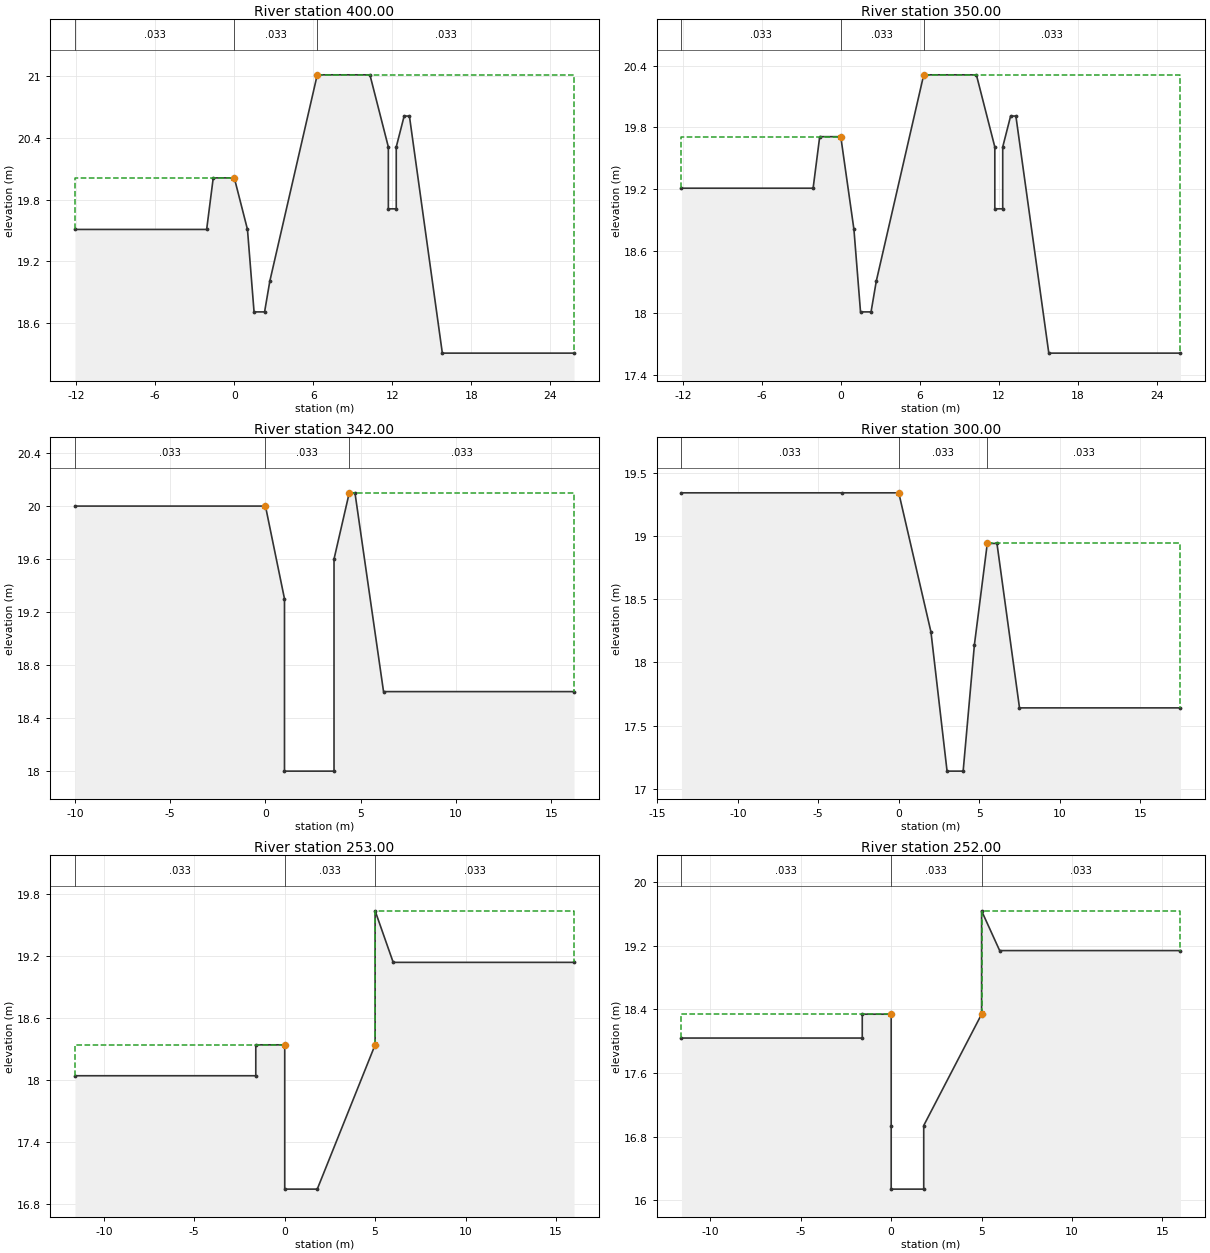
Type RM Length L Ch R = 1 ,400.00  ,50,50,50
BEGIN DESCRIPTION:
8
END DESCRIPTION:
#Sta/Elev= 18
   -12.1   19.51    -2.1   19.51    -1.6   20.01       0   20.01       1   19.51
     1.5   18.71     2.3   18.71     2.7   19.01     6.3   21.01    10.3   21.01
    11.7   20.31    11.7   19.71    12.3   19.71    12.3   20.31    12.9   20.61
    13.3   20.61    15.8   18.31    25.8   18.31
#Mann= 3 , 0 , 0
   -12.1    .033       0       0    .033       0     6.3    .033       0
#XS Ineff= 2 , 0
               0   20.01     6.3           21.01
Permanent Ineff=
       F       F
Bank Sta=0,6.3
XS Rating Curve= 0
Exp/Cntr=.3,.1

Type RM Length L Ch R = 1 ,350.00  ,8,8,8
BEGIN DESCRIPTION:
7
END DESCRIPTION:
#Sta/Elev= 18
   -12.1   19.21    -2.1   19.21    -1.6   19.71       0   19.71       1   18.81
     1.5   18.01     2.3   18.01     2.7   18.31     6.3   20.31    10.3   20.31
    11.7   19.61    11.7   19.01    12.3   19.01    12.3   19.61    12.9   19.91
    13.3   19.91    15.8   17.61    25.8   17.61
#Mann= 3 , 0 , 0
   -12.1    .033       0       0    .033       0     6.3    .033       0
#XS Ineff= 2 , 0
               0   19.71     6.3           20.31
Permanent Ineff=
       F       F
Bank Sta=0,6.3
XS Rating Curve= 0
Exp/Cntr=.3,.1

Type RM Length L Ch R = 1 ,342.00  ,42,42,42
BEGIN DESCRIPTION:
6.042
END DESCRIPTION:
#Sta/Elev= 10
     -10      20       0      20       1    19.3       1      18     3.6      18
     3.6    19.6     4.4    20.1     4.7    20.1     6.2    18.6    16.2    18.6
#Mann= 3 , 0 , 0
     -10    .033       0       0    .033       0     4.4    .033       0
#XS Ineff= 2 , 0
               0      20     4.4            20.1
Permanent Ineff=
       F       F
Bank Sta=0,4.4
XS Rating Curve= 0
Exp/Cntr=.3,.1

Type RM Length L Ch R = 1 ,300.00  ,47,47,47
BEGIN DESCRIPTION:
6
END DESCRIPTION:
#Sta/Elev= 11
   -13.5   19.34    -3.5   19.34       0   19.34       2   18.24       3   17.14
       4   17.14     4.7   18.14     5.5   18.94     6.1   18.94     7.5   17.64
    17.5   17.64
#Mann= 3 , 0 , 0
   -13.5    .033       0       0    .033       0     5.5    .033       0
#XS Ineff= 2 , 0
               0   19.34     5.5           18.94
Permanent Ineff=
       F       F
Bank Sta=0,5.5
XS Rating Curve= 0
Exp/Cntr=.3,.1

Type RM Length L Ch R = 1 ,253.00  ,1,1,1
BEGIN DESCRIPTION:
5.003
END DESCRIPTION:
#Sta/Elev= 10
   -11.6   18.04    -1.6   18.04    -1.6   18.34       0   18.34       0   16.94
     1.8   16.94       5   18.34       5   19.64       6   19.14      16   19.14
#Mann= 3 , 0 , 0
   -11.6    .033       0       0    .033       0       5    .033       0
#XS Ineff= 2 , 0
               0   18.34       5           19.64
Permanent Ineff=
       F       F
Bank Sta=0,5
XS Rating Curve= 0
Exp/Cntr=.3,.1

Type RM Length L Ch R = 1 ,252.00  ,2,2,2
BEGIN DESCRIPTION:
5.002
END DESCRIPTION:
#Sta/Elev= 12
   -11.6   18.04    -1.6   18.04    -1.6   18.34       0   18.34       0   16.94
       0   16.14     1.8   16.14     1.8   16.94       5   18.34       5   19.64
       6   19.14      16   19.14
#Mann= 3 , 0 , 0
   -11.6    .033       0       0    .033       0       5    .033       0
#XS Ineff= 2 , 0
               0   18.34       5           19.64
Permanent Ineff=
       F       F
Bank Sta=0,5
XS Rating Curve= 0
Exp/Cntr=.3,.1

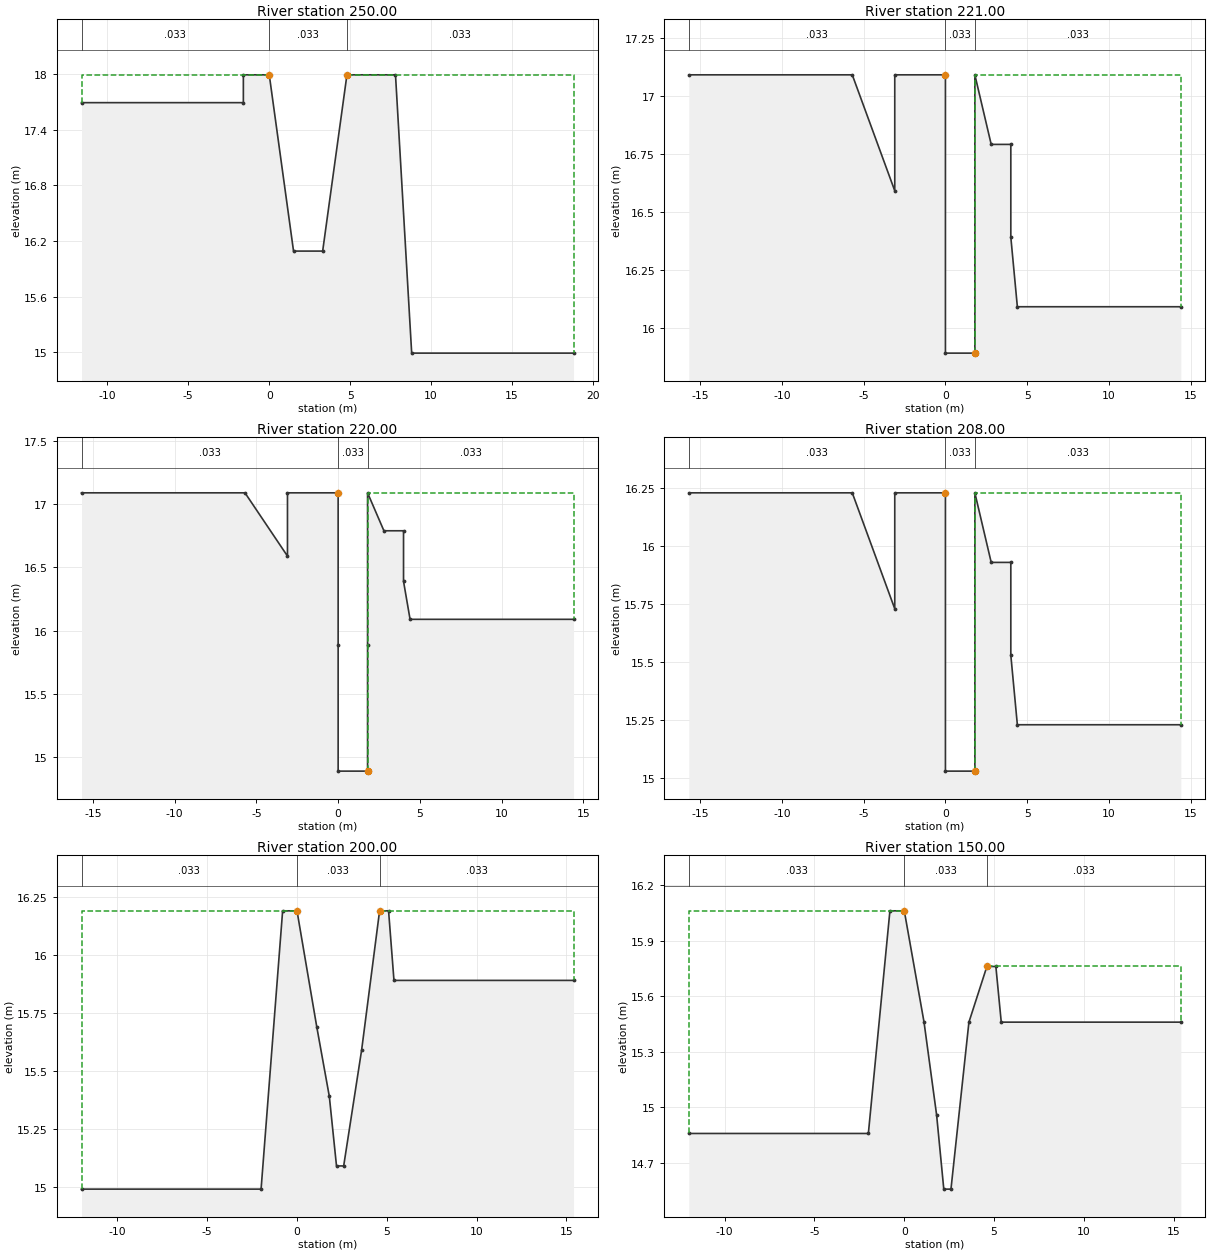
Type RM Length L Ch R = 1 ,250.00  ,29,29,29
BEGIN DESCRIPTION:
5
END DESCRIPTION:
#Sta/Elev= 10
   -11.6   17.69    -1.6   17.69    -1.6   17.99       0   17.99     1.5   16.09
     3.3   16.09     4.8   17.99     7.8   17.99     8.8   14.99    18.8   14.99
#Mann= 3 , 0 , 0
   -11.6    .033       0       0    .033       0     4.8    .033       0
#XS Ineff= 2 , 0
               0   17.99     4.8           17.99
Permanent Ineff=
       F       F
Bank Sta=0,4.8
XS Rating Curve= 0
Exp/Cntr=.3,.1

Type RM Length L Ch R = 1 ,221.00  ,1,1,1
BEGIN DESCRIPTION:
4.021
END DESCRIPTION:
#Sta/Elev= 13
   -15.7   17.09    -5.7   17.09    -3.1   16.59    -3.1   17.09       0   17.09
       0   15.89     1.8   15.89     1.8   17.09     2.8   16.79       4   16.79
       4   16.39     4.4   16.09    14.4   16.09
#Mann= 3 , 0 , 0
   -15.7    .033       0       0    .033       0     1.8    .033       0
#XS Ineff= 2 , 0
               0   17.09     1.8           17.09
Permanent Ineff=
       F       F
Bank Sta=0,1.8
XS Rating Curve= 0
Exp/Cntr=.3,.1

Type RM Length L Ch R = 1 ,220.00  ,12,12,12
BEGIN DESCRIPTION:
4.02
END DESCRIPTION:
#Sta/Elev= 15
   -15.7   17.09    -5.7   17.09    -3.1   16.59    -3.1   17.09       0   17.09
       0   15.89       0   14.89     1.8   14.89     1.8   15.89     1.8   17.09
     2.8   16.79       4   16.79       4   16.39     4.4   16.09    14.4   16.09
#Mann= 3 , 0 , 0
   -15.7    .033       0       0    .033       0     1.8    .033       0
#XS Ineff= 2 , 0
               0   17.09     1.8           17.09
Permanent Ineff=
       F       F
Bank Sta=0,1.8
XS Rating Curve= 0
Exp/Cntr=.3,.1

Type RM Length L Ch R = 1 ,208.00  ,8,8,8
BEGIN DESCRIPTION:
4.008
END DESCRIPTION:
#Sta/Elev= 13
   -15.7   16.23    -5.7   16.23    -3.1   15.73    -3.1   16.23       0   16.23
       0   15.03     1.8   15.03     1.8   16.23     2.8   15.93       4   15.93
       4   15.53     4.4   15.23    14.4   15.23
#Mann= 3 , 0 , 0
   -15.7    .033       0       0    .033       0     1.8    .033       0
#XS Ineff= 2 , 0
               0   16.23     1.8           16.23
Permanent Ineff=
       F       F
Bank Sta=0,1.8
XS Rating Curve= 0
Exp/Cntr=.3,.1

Type RM Length L Ch R = 1 ,200.00  ,50,50,50
BEGIN DESCRIPTION:
4
END DESCRIPTION:
#Sta/Elev= 13
     -12   14.99      -2   14.99     -.8   16.19       0   16.19     1.1   15.69
     1.8   15.39     2.2   15.09     2.6   15.09     3.6   15.59     4.6   16.19
     5.1   16.19     5.4   15.89    15.4   15.89
#Mann= 3 , 0 , 0
     -12    .033       0       0    .033       0     4.6    .033       0
#XS Ineff= 2 , 0
               0   16.19     4.6           16.19
Permanent Ineff=
       F       F
Bank Sta=0,4.6
XS Rating Curve= 0
Exp/Cntr=.3,.1

Type RM Length L Ch R = 1 ,150.00  ,6,6,6
BEGIN DESCRIPTION:
3
END DESCRIPTION:
#Sta/Elev= 13
     -12   14.86      -2   14.86     -.8   16.06       0   16.06     1.1   15.46
     1.8   14.96     2.2   14.56     2.6   14.56     3.6   15.46     4.6   15.76
     5.1   15.76     5.4   15.46    15.4   15.46
#Mann= 3 , 0 , 0
     -12    .033       0       0    .033       0     4.6    .033       0
#XS Ineff= 2 , 0
               0   16.06     4.6           15.76
Permanent Ineff=
       F       F
Bank Sta=0,4.6
XS Rating Curve= 0
Exp/Cntr=.3,.1

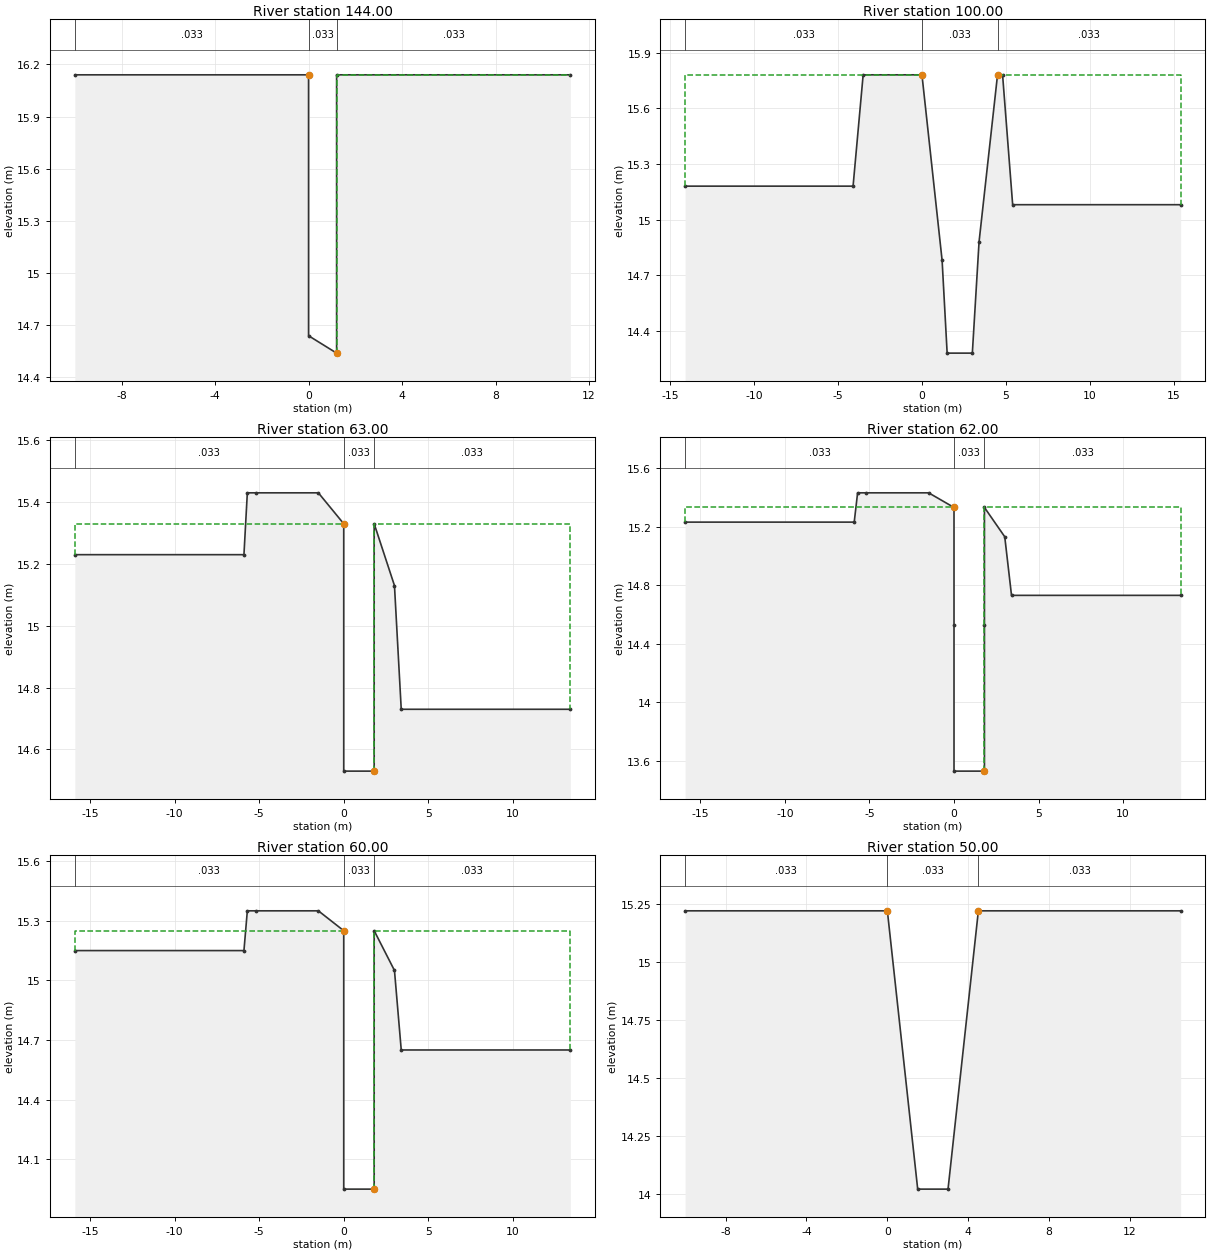
Type RM Length L Ch R = 1 ,144.00  ,44,44,44
BEGIN DESCRIPTION:
2.044
END DESCRIPTION:
#Sta/Elev= 6
     -10   16.14       0   16.14       0   14.64     1.2   14.54     1.2   16.14
    11.2   16.14
#Mann= 3 , 0 , 0
     -10    .033       0       0    .033       0     1.2    .033       0
#XS Ineff= 2 , 0
               0   16.14     1.2           16.14
Permanent Ineff=
       F       F
Bank Sta=0,1.2
XS Rating Curve= 0
Exp/Cntr=.3,.1

Type RM Length L Ch R = 1 ,100.00  ,37,37,37
BEGIN DESCRIPTION:
2
END DESCRIPTION:
#Sta/Elev= 12
   -14.1   15.18    -4.1   15.18    -3.5   15.78       0   15.78     1.2   14.78
     1.5   14.28       3   14.28     3.4   14.88     4.5   15.78     4.8   15.78
     5.4   15.08    15.4   15.08
#Mann= 3 , 0 , 0
   -14.1    .033       0       0    .033       0     4.5    .033       0
#XS Ineff= 2 , 0
               0   15.78     4.5           15.78
Permanent Ineff=
       F       F
Bank Sta=0,4.5
XS Rating Curve= 0
Exp/Cntr=.3,.1

Type RM Length L Ch R = 1 ,63.00   ,1,1,1
BEGIN DESCRIPTION:
1.013
END DESCRIPTION:
#Sta/Elev= 12
   -15.9   15.23    -5.9   15.23    -5.7   15.43    -5.2   15.43    -1.5   15.43
       0   15.33       0   14.53     1.8   14.53     1.8   15.33       3   15.13
     3.4   14.73    13.4   14.73
#Mann= 3 , 0 , 0
   -15.9    .033       0       0    .033       0     1.8    .033       0
#XS Ineff= 2 , 0
               0   15.33     1.8           15.33
Permanent Ineff=
       F       F
Bank Sta=0,1.8
XS Rating Curve= 0
Exp/Cntr=.3,.1

Type RM Length L Ch R = 1 ,62.00   ,2,2,2
BEGIN DESCRIPTION:
1.012
END DESCRIPTION:
#Sta/Elev= 14
   -15.9   15.23    -5.9   15.23    -5.7   15.43    -5.2   15.43    -1.5   15.43
       0   15.33       0   14.53       0   13.53     1.8   13.53     1.8   14.53
     1.8   15.33       3   15.13     3.4   14.73    13.4   14.73
#Mann= 3 , 0 , 0
   -15.9    .033       0       0    .033       0     1.8    .033       0
#XS Ineff= 2 , 0
               0   15.33     1.8           15.33
Permanent Ineff=
       F       F
Bank Sta=0,1.8
XS Rating Curve= 0
Exp/Cntr=.3,.1

Type RM Length L Ch R = 1 ,60.00   ,10,10,10
BEGIN DESCRIPTION:
1.01
END DESCRIPTION:
#Sta/Elev= 12
   -15.9   15.15    -5.9   15.15    -5.7   15.35    -5.2   15.35    -1.5   15.35
       0   15.25       0   13.95     1.8   13.95     1.8   15.25       3   15.05
     3.4   14.65    13.4   14.65
#Mann= 3 , 0 , 0
   -15.9    .033       0       0    .033       0     1.8    .033       0
#XS Ineff= 2 , 0
               0   15.25     1.8           15.25
Permanent Ineff=
       F       F
Bank Sta=0,1.8
XS Rating Curve= 0
Exp/Cntr=.3,.1

Type RM Length L Ch R = 1 ,50.00   ,50,50,50
BEGIN DESCRIPTION:
1
END DESCRIPTION:
#Sta/Elev= 6
     -10   15.22       0   15.22     1.5   14.02       3   14.02     4.5   15.22
    14.5   15.22
#Mann= 3 , 0 , 0
     -10    .033       0       0    .033       0     4.5    .033       0
#XS Ineff= 2 , 0
               0   15.22     4.5           15.22
Permanent Ineff=
       F       F
Bank Sta=0,4.5
XS Rating Curve= 0
Exp/Cntr=.3,.1

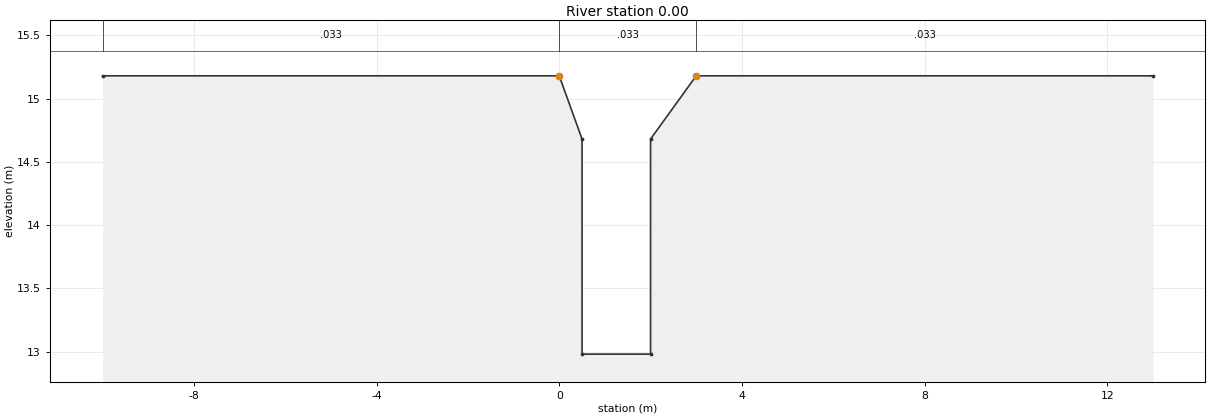
Type RM Length L Ch R = 1 ,0.00    ,0,0,0
BEGIN DESCRIPTION:
0
END DESCRIPTION:
#Sta/Elev= 8
     -10   15.18       0   15.18      .5   14.68      .5   12.98       2   12.98
       2   14.68       3   15.18      13   15.18
#Mann= 3 , 0 , 0
     -10    .033       0       0    .033       0       3    .033       0
#XS Ineff= 2 , 0
               0   15.18       3           15.18
Permanent Ineff=
       F       F
Bank Sta=0,3
XS Rating Curve= 0
Exp/Cntr=.3,.1

Chan Stop Cuts=-1