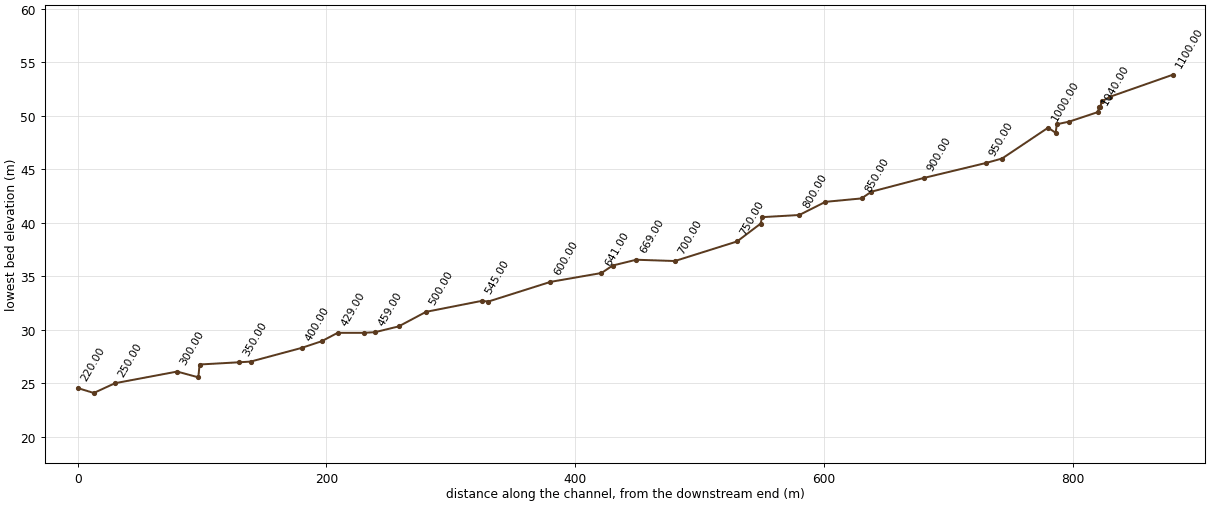
--- KU.prj (project) ---

Proj Title=KUSAN
Current Plan=p01
Default Exp/Contr=.3,.1
SI Units
Geom File=g01
Flow File=f01
Plan File=p01
Y Axis Title=Elevation
X Axis Title(PF)=Main Channel Distance
X Axis Title(XS)=Station
BEGIN DESCRIPTION:
           BACK WATER COMPUTATION
      APPLICATION OF HEC-2 BY Samju Construction Engineering
      KUSAN-STREEM : 30 YR
END DESCRIPTION:
DSS Export Rating Curves= 0
DSS Export Rating Curve Sorted= 0
DSS Export Volume Flow Curves= 0
DXF OffsetX= 0
DXF OffsetY= 0
DXF ScaleX= 1
DXF ScaleY= 10

--- KU.p01 (plan) ---

Plan Title=Imported Plan 01
Version=Version 3.0.1  Mar 2001
Short Identifier=Imported Pla
Geom File=g01
Flow File=f01
Subcritical Flow
K Sum by GR= 0
Std Step Tol= 0.003
Critical Tol= 0.003
Num of Std Step Trials= 20
Max Error Tol= 0.1
Flow Tol Ratio= 0.001
Split Flow NTrial= 30
Split Flow Tol= 0.02
Split Flow Ratio= 0.02
Log Output Level= 0
Friction Slope Method= 1
Unsteady Friction Slope Method= 2
Parabolic Critical Depth
Global Vel Dist= 0 , 0 , 0
Global Log Level= 0
CheckData=True
Encroach Param=-1 ,0,0, 0
Computation Interval=1HOUR
Output Interval=1HOUR
Run HTab= 0
Run UNet= 0
Run PostProcess= 0
UNET Theta= 1
UNET ZTol= 0.02
UNET ZSATol= 0.1
UNET MxIter= 20
UNET MaxInSteps= 20
UNET DtIC= 0
UNET DtMin= 0
UNET MaxCRTS= 20
UNET WFStab= 2
UNET SFStab= 1
UNET WFX= 1
UNET SFX= 1
UNET Convert EG Bridges=-1
UNET Use Existing IB Tables=-1
Instantaneous Interval=1HOUR
Write IC File= 0
Write Velocity= 0
Write Detailed= 0

--- KU.f01 (steady flow) ---

Flow Title=Imported Flow 01
Version=Version 3.0.1  Mar 2001
Number of Profiles= 5
Profile Names=10YR,20YR,30YR,50YR,80YR
River Rch & RM=RIVER-1,Reach-1         ,1100.00
    5.93    6.53    6.88    7.33    7.73
Boundary for River Rch & Prof#=RIVER-1,Reach-1         , 1
Up Type= 0
Dn Type= 3
Dn Slope=.034
Boundary for River Rch & Prof#=RIVER-1,Reach-1         , 2
Up Type= 0
Dn Type= 3
Dn Slope=.034
Boundary for River Rch & Prof#=RIVER-1,Reach-1         , 3
Up Type= 0
Dn Type= 3
Dn Slope=.034
Boundary for River Rch & Prof#=RIVER-1,Reach-1         , 4
Up Type= 0
Dn Type= 3
Dn Slope=.034
Boundary for River Rch & Prof#=RIVER-1,Reach-1         , 5
Up Type= 0
Dn Type= 3
Dn Slope=.034
DSS Import GetInterval= 0
DSS Import GetPeak= 0
DSS Import FillOption= 0

--- KU.g01 (geometry) ---

Geom Title=Imported Geom 01
Version=Version 3.0.1  Mar 2001

River Reach=RIVER-1         ,Reach-1
Reach XY= 2
              .5             .95              .5             .05

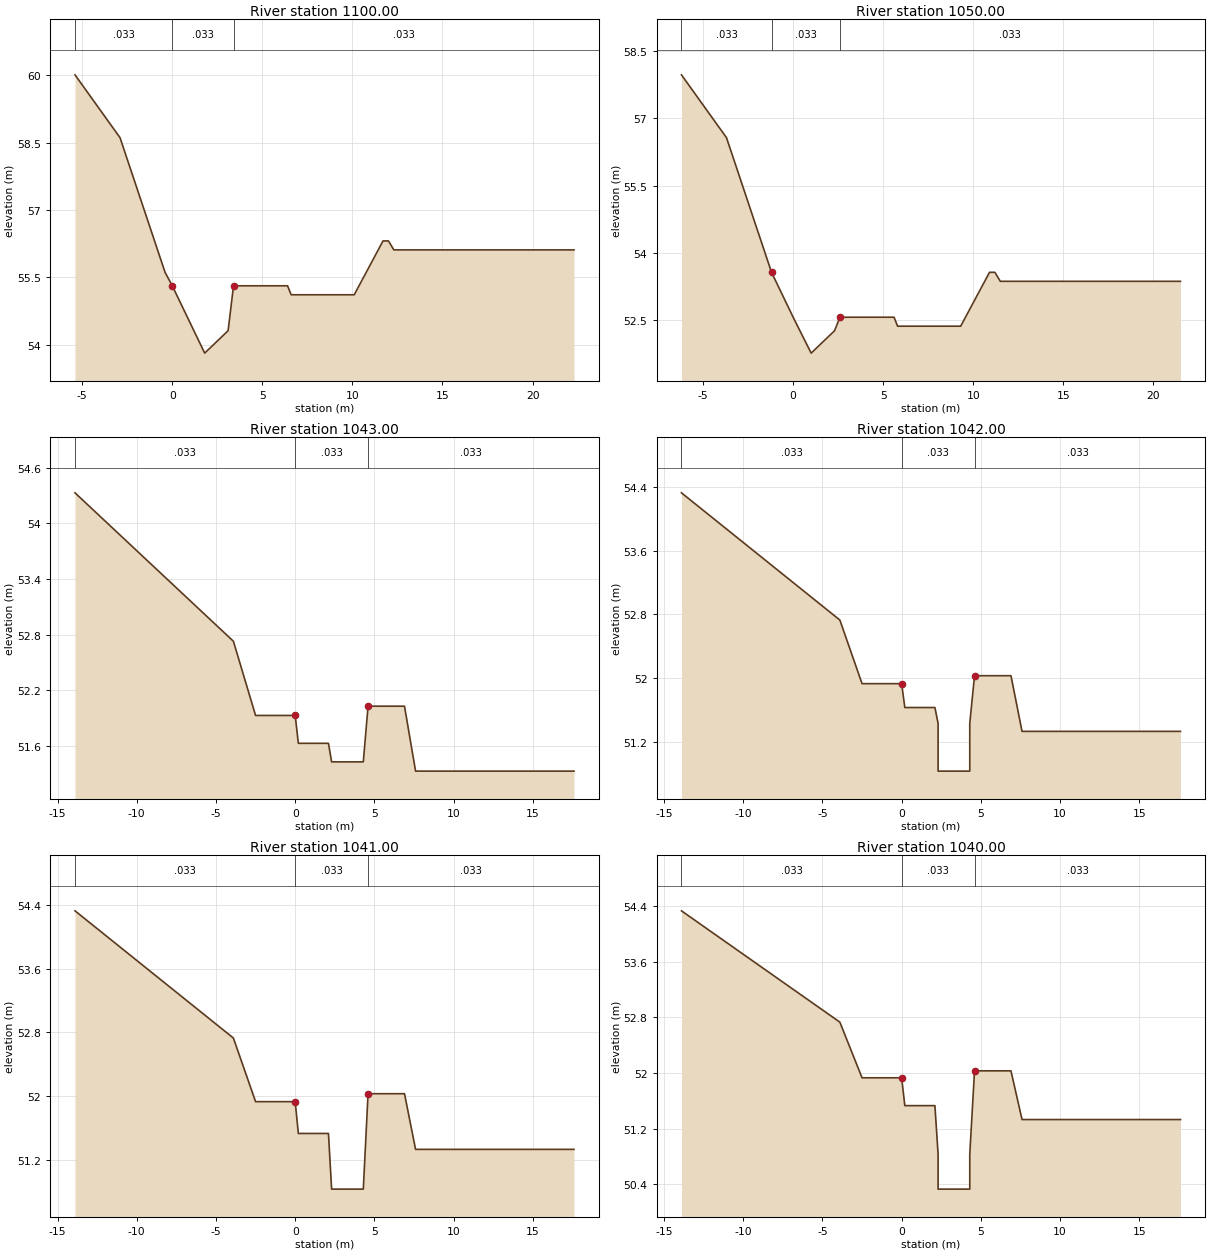
Type RM Length L Ch R = 1 ,1100.00 ,50,50,50
BEGIN DESCRIPTION:
22
END DESCRIPTION:
#Sta/Elev= 14
    -5.4   60.01    -2.9   58.61     -.4   55.61       0   55.31     1.8   53.81
     3.1   54.31     3.4   55.31     6.4   55.31     6.6   55.11    10.1   55.11
    11.7   56.31      12   56.31    12.3   56.11    22.3   56.11
#Mann= 3 , 0 , 0
    -5.4    .033       0       0    .033       0     3.4    .033       0
Bank Sta=0,3.4
XS Rating Curve= 0
Exp/Cntr=.3,.1

Type RM Length L Ch R = 1 ,1050.00 ,7,7,7
BEGIN DESCRIPTION:
21
END DESCRIPTION:
#Sta/Elev= 14
    -6.2   57.97    -3.7   56.57    -1.2   53.57       0   52.57       1   51.77
     2.3   52.27     2.6   52.57     5.6   52.57     5.8   52.37     9.3   52.37
    10.9   53.57    11.2   53.57    11.5   53.37    21.5   53.37
#Mann= 3 , 0 , 0
    -6.2    .033       0    -1.2    .033       0     2.6    .033       0
Bank Sta=-1.2,2.6
XS Rating Curve= 0
Exp/Cntr=.3,.1

Type RM Length L Ch R = 1 ,1043.00 ,1,1,1
BEGIN DESCRIPTION:
20.043
END DESCRIPTION:
#Sta/Elev= 13
   -13.9   54.33    -8.9   53.53    -3.9   52.73    -2.5   51.93       0   51.93
      .2   51.63     2.1   51.63     2.3   51.43     4.3   51.43     4.6   52.03
     6.9   52.03     7.6   51.33    17.6   51.33
#Mann= 3 , 0 , 0
   -13.9    .033       0       0    .033       0     4.6    .033       0
Bank Sta=0,4.6
XS Rating Curve= 0
Exp/Cntr=.3,.1

Type RM Length L Ch R = 1 ,1042.00 ,1,1,1
BEGIN DESCRIPTION:
20.042
END DESCRIPTION:
#Sta/Elev= 15
   -13.9   54.33    -8.9   53.53    -3.9   52.73    -2.5   51.93       0   51.93
      .2   51.63     2.1   51.63     2.3   51.43     2.3   50.83     4.3   50.83
     4.3   51.43     4.6   52.03     6.9   52.03     7.6   51.33    17.6   51.33
#Mann= 3 , 0 , 0
   -13.9    .033       0       0    .033       0     4.6    .033       0
Bank Sta=0,4.6
XS Rating Curve= 0
Exp/Cntr=.3,.1

Type RM Length L Ch R = 1 ,1041.00 ,1,1,1
BEGIN DESCRIPTION:
20.041
END DESCRIPTION:
#Sta/Elev= 13
   -13.9   54.33    -8.9   53.53    -3.9   52.73    -2.5   51.93       0   51.93
      .2   51.53     2.1   51.53     2.3   50.83     4.3   50.83     4.6   52.03
     6.9   52.03     7.6   51.33    17.6   51.33
#Mann= 3 , 0 , 0
   -13.9    .033       0       0    .033       0     4.6    .033       0
Bank Sta=0,4.6
XS Rating Curve= 0
Exp/Cntr=.3,.1

Type RM Length L Ch R = 1 ,1040.00 ,23,23,23
BEGIN DESCRIPTION:
20.04
END DESCRIPTION:
#Sta/Elev= 15
   -13.9   54.33    -8.9   53.53    -3.9   52.73    -2.5   51.93       0   51.93
      .2   51.53     2.1   51.53     2.3   50.83     2.3   50.33     4.3   50.33
     4.3   50.83     4.6   52.03     6.9   52.03     7.6   51.33    17.6   51.33
#Mann= 3 , 0 , 0
   -13.9    .033       0       0    .033       0     4.6    .033       0
Bank Sta=0,4.6
XS Rating Curve= 0
Exp/Cntr=.3,.1

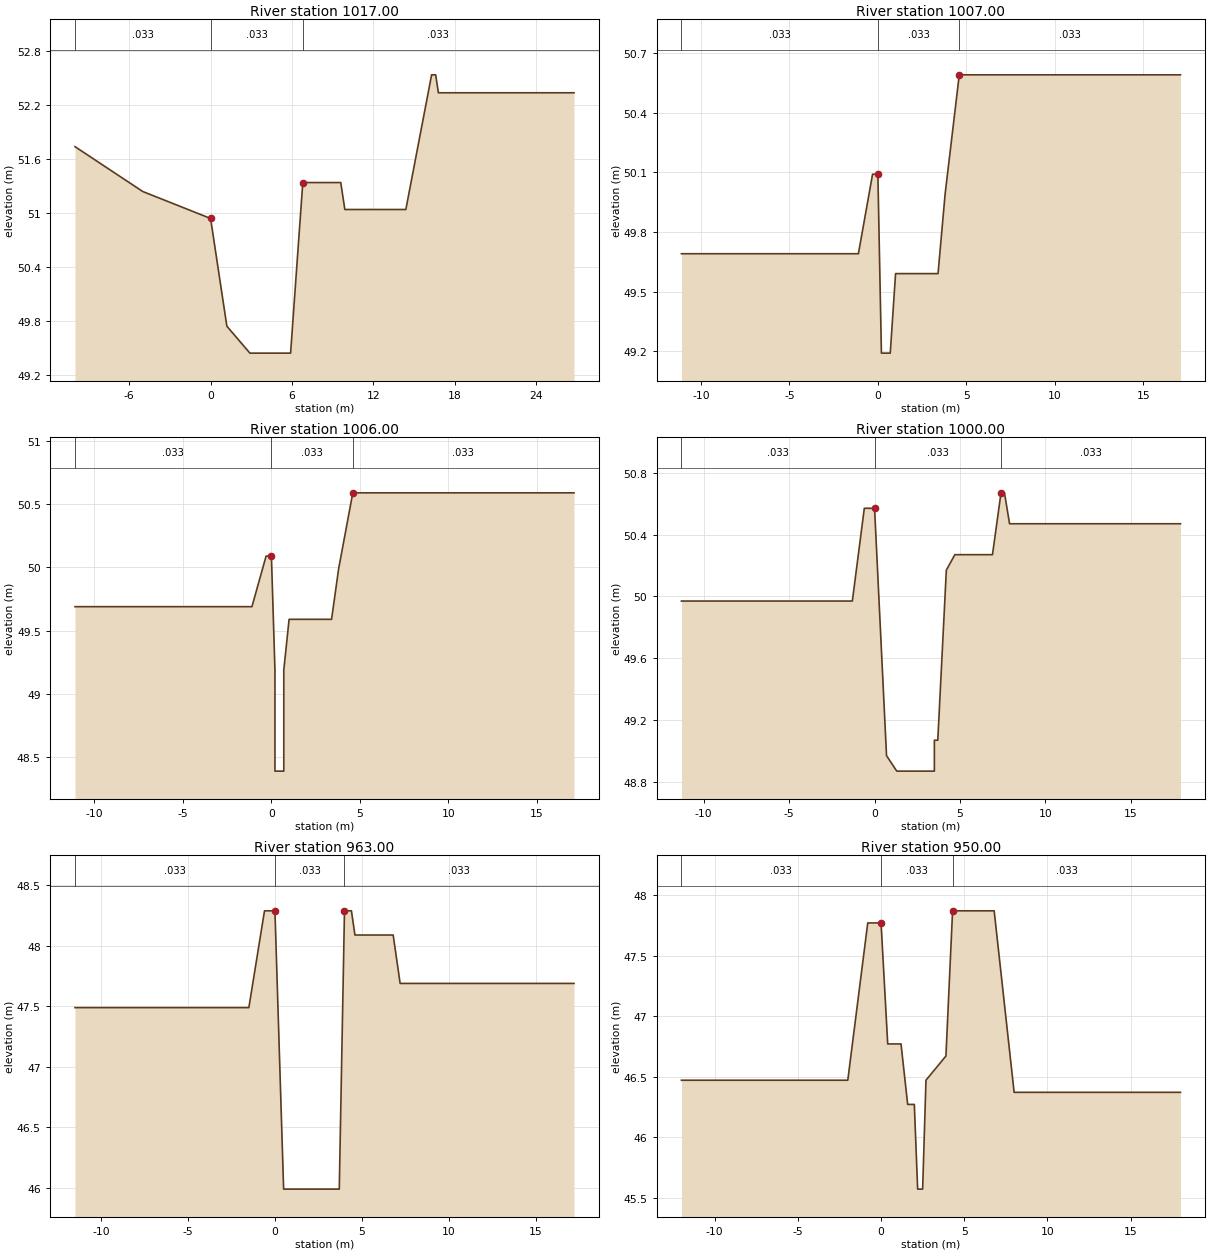
Type RM Length L Ch R = 1 ,1017.00 ,10,10,10
BEGIN DESCRIPTION:
20.017
END DESCRIPTION:
#Sta/Elev= 14
     -10   51.74      -5   51.24       0   50.94     1.2   49.74     2.9   49.44
     5.9   49.44     6.8   51.34     9.6   51.34     9.9   51.04    14.4   51.04
    16.3   52.54    16.6   52.54    16.8   52.34    26.8   52.34
#Mann= 3 , 0 , 0
     -10    .033       0       0    .033       0     6.8    .033       0
Bank Sta=0,6.8
XS Rating Curve= 0
Exp/Cntr=.3,.1

Type RM Length L Ch R = 1 ,1007.00 ,1,1,1
BEGIN DESCRIPTION:
20.007
END DESCRIPTION:
#Sta/Elev= 12
   -11.1   49.69    -1.1   49.69     -.3   50.09       0   50.09      .2   49.19
      .7   49.19       1   49.59     3.4   49.59     3.8   49.99     4.6   50.59
     7.1   50.59    17.1   50.59
#Mann= 3 , 0 , 0
   -11.1    .033       0       0    .033       0     4.6    .033       0
Bank Sta=0,4.6
XS Rating Curve= 0
Exp/Cntr=.3,.1

Type RM Length L Ch R = 1 ,1006.00 ,6,6,6
BEGIN DESCRIPTION:
20.006
END DESCRIPTION:
#Sta/Elev= 14
   -11.1   49.69    -1.1   49.69     -.3   50.09       0   50.09      .2   49.19
      .2   48.39      .7   48.39      .7   49.19       1   49.59     3.4   49.59
     3.8   49.99     4.6   50.59     7.1   50.59    17.1   50.59
#Mann= 3 , 0 , 0
   -11.1    .033       0       0    .033       0     4.6    .033       0
Bank Sta=0,4.6
XS Rating Curve= 0
Exp/Cntr=.3,.1

Type RM Length L Ch R = 1 ,1000.00 ,37,37,37
BEGIN DESCRIPTION:
20
END DESCRIPTION:
#Sta/Elev= 16
   -11.3   49.97    -1.3   49.97     -.6   50.57       0   50.57      .7   48.97
     1.3   48.87     3.5   48.87     3.5   49.07     3.7   49.07     4.2   50.17
     4.7   50.27     6.9   50.27     7.4   50.67     7.6   50.67     7.9   50.47
    17.9   50.47
#Mann= 3 , 0 , 0
   -11.3    .033       0       0    .033       0     7.4    .033       0
Bank Sta=0,7.4
XS Rating Curve= 0
Exp/Cntr=.3,.1

Type RM Length L Ch R = 1 ,963.00  ,13,13,13
BEGIN DESCRIPTION:
19.013
END DESCRIPTION:
#Sta/Elev= 12
   -11.5   47.49    -1.5   47.49     -.6   48.29       0   48.29      .5   45.99
     3.7   45.99       4   48.29     4.4   48.29     4.6   48.09     6.8   48.09
     7.2   47.69    17.2   47.69
#Mann= 3 , 0 , 0
   -11.5    .033       0       0    .033       0       4    .033       0
Bank Sta=0,4
XS Rating Curve= 0
Exp/Cntr=.3,.1

Type RM Length L Ch R = 1 ,950.00  ,50,50,50
BEGIN DESCRIPTION:
19
END DESCRIPTION:
#Sta/Elev= 16
     -12   46.47      -2   46.47     -.8   47.77       0   47.77      .4   46.77
     1.2   46.77     1.6   46.27       2   46.27     2.2   45.57     2.5   45.57
     2.7   46.47     3.9   46.67     4.3   47.87     6.8   47.87       8   46.37
      18   46.37
#Mann= 3 , 0 , 0
     -12    .033       0       0    .033       0     4.3    .033       0
Bank Sta=0,4.3
XS Rating Curve= 0
Exp/Cntr=.3,.1

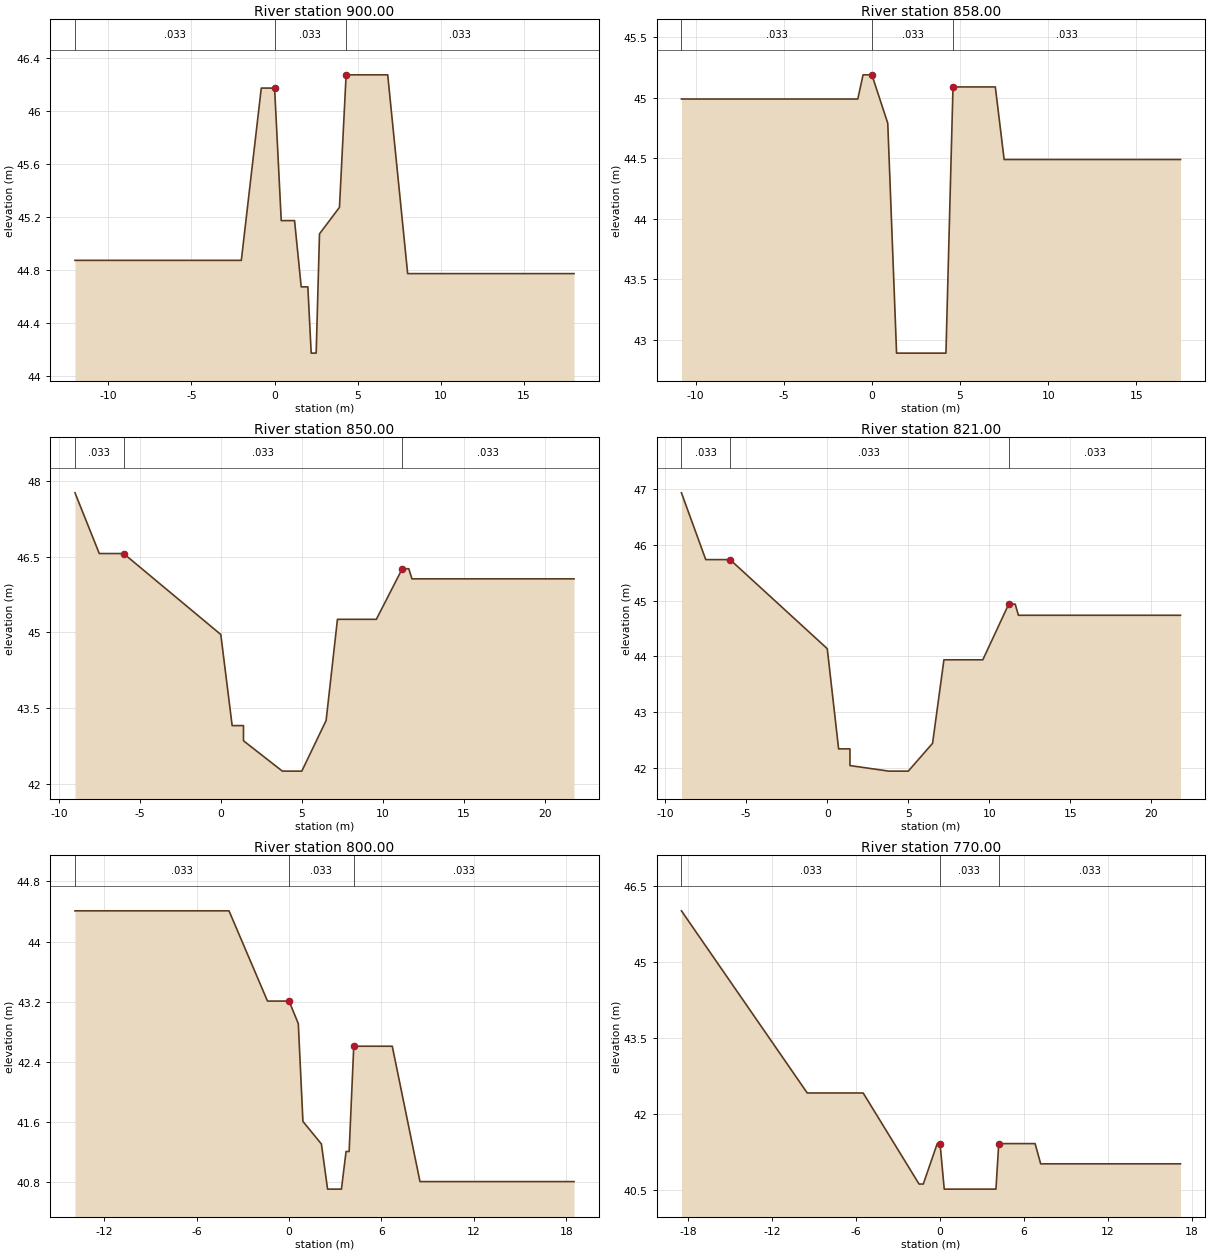
Type RM Length L Ch R = 1 ,900.00  ,42,42,42
BEGIN DESCRIPTION:
18
END DESCRIPTION:
#Sta/Elev= 16
     -12   44.87      -2   44.87     -.8   46.17       0   46.17      .4   45.17
     1.2   45.17     1.6   44.67       2   44.67     2.2   44.17     2.5   44.17
     2.7   45.07     3.9   45.27     4.3   46.27     6.8   46.27       8   44.77
      18   44.77
#Mann= 3 , 0 , 0
     -12    .033       0       0    .033       0     4.3    .033       0
Bank Sta=0,4.3
XS Rating Curve= 0
Exp/Cntr=.3,.1

Type RM Length L Ch R = 1 ,858.00  ,8,8,8
BEGIN DESCRIPTION:
17.008
END DESCRIPTION:
#Sta/Elev= 11
   -10.8   44.99     -.8   44.99     -.5   45.19       0   45.19      .9   44.79
     1.4   42.89     4.2   42.89     4.6   45.09       7   45.09     7.5   44.49
    17.5   44.49
#Mann= 3 , 0 , 0
   -10.8    .033       0       0    .033       0     4.6    .033       0
Bank Sta=0,4.6
XS Rating Curve= 0
Exp/Cntr=.3,.1

Type RM Length L Ch R = 1 ,850.00  ,29,29,29
BEGIN DESCRIPTION:
17
END DESCRIPTION:
#Sta/Elev= 17
      -9   47.76    -7.5   46.56      -6   46.56      -3   45.76       0   44.96
      .7   43.16     1.4   43.16     1.4   42.86     3.8   42.26       5   42.26
     6.5   43.26     7.2   45.26     9.6   45.26    11.2   46.26    11.6   46.26
    11.8   46.06    21.8   46.06
#Mann= 3 , 0 , 0
      -9    .033       0      -6    .033       0    11.2    .033       0
Bank Sta=-6,11.2
XS Rating Curve= 0
Exp/Cntr=.3,.1

Type RM Length L Ch R = 1 ,821.00  ,21,21,21
BEGIN DESCRIPTION:
16.021
END DESCRIPTION:
#Sta/Elev= 17
      -9   46.94    -7.5   45.74      -6   45.74      -3   44.94       0   44.14
      .7   42.34     1.4   42.34     1.4   42.04     3.8   41.94       5   41.94
     6.5   42.44     7.2   43.94     9.6   43.94    11.2   44.94    11.6   44.94
    11.8   44.74    21.8   44.74
#Mann= 3 , 0 , 0
      -9    .033       0      -6    .033       0    11.2    .033       0
Bank Sta=-6,11.2
XS Rating Curve= 0
Exp/Cntr=.3,.1

Type RM Length L Ch R = 1 ,800.00  ,30,30,30
BEGIN DESCRIPTION:
16
END DESCRIPTION:
#Sta/Elev= 15
   -13.9   44.41    -3.9   44.41    -1.4   43.21       0   43.21      .6   42.91
      .9   41.61     2.1   41.31     2.5   40.71     3.4   40.71     3.7   41.21
     3.9   41.21     4.2   42.61     6.7   42.61     8.5   40.81    18.5   40.81
#Mann= 3 , 0 , 0
   -13.9    .033       0       0    .033       0     4.2    .033       0
Bank Sta=0,4.2
XS Rating Curve= 0
Exp/Cntr=.3,.1

Type RM Length L Ch R = 1 ,770.00  ,1,1,1
BEGIN DESCRIPTION:
15.02
END DESCRIPTION:
#Sta/Elev= 16
   -18.5   46.01   -15.5   44.81   -12.5   43.61    -9.5   42.41    -7.5   42.41
    -5.5   42.41    -1.5   40.61    -1.2   40.61     -.2   41.41       0   41.41
      .3   40.51       4   40.51     4.2   41.41     6.8   41.41     7.2   41.01
    17.2   41.01
#Mann= 3 , 0 , 0
   -18.5    .033       0       0    .033       0     4.2    .033       0
Bank Sta=0,4.2
XS Rating Curve= 0
Exp/Cntr=.3,.1

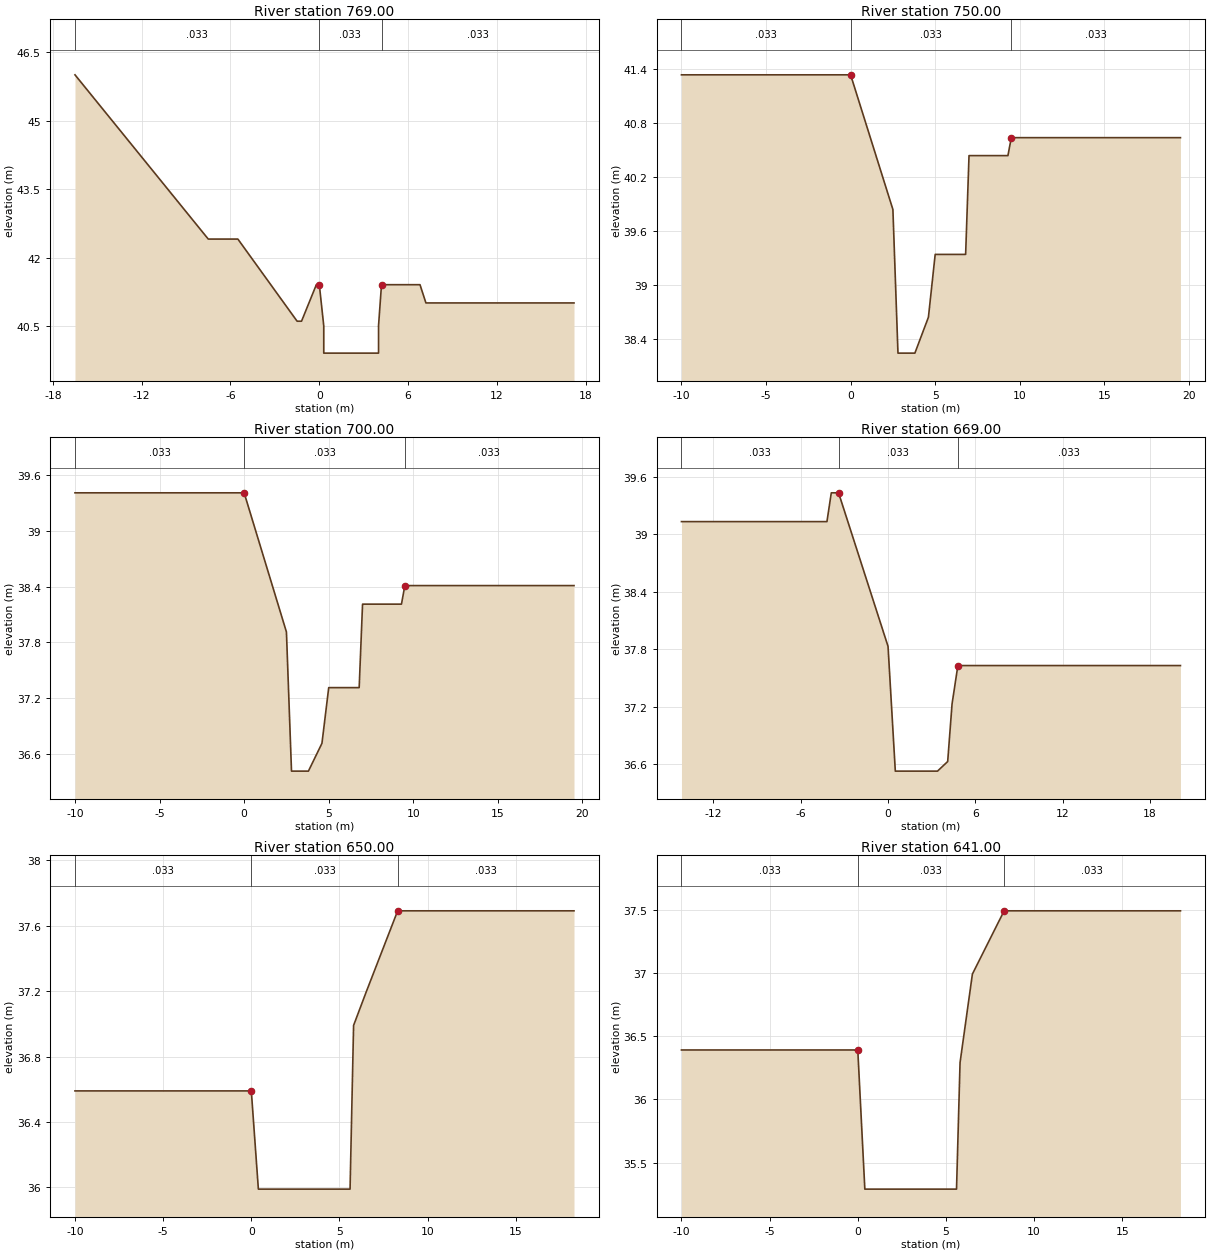
Type RM Length L Ch R = 1 ,769.00  ,19,19,19
BEGIN DESCRIPTION:
15.019
END DESCRIPTION:
#Sta/Elev= 17
   -16.5   46.01   -13.5   44.81   -10.5   43.61    -7.5   42.41    -5.5   42.41
    -1.5   40.61    -1.2   40.61     -.2   41.41       0   41.41      .3   40.51
      .3   39.91       4   39.91       4   40.51     4.2   41.41     6.8   41.41
     7.2   41.01    17.2   41.01
#Mann= 3 , 0 , 0
   -16.5    .033       0       0    .033       0     4.2    .033       0
Bank Sta=0,4.2
XS Rating Curve= 0
Exp/Cntr=.3,.1

Type RM Length L Ch R = 1 ,750.00  ,50,50,50
BEGIN DESCRIPTION:
15
END DESCRIPTION:
#Sta/Elev= 12
     -10   41.34       0   41.34     2.5   39.84     2.8   38.24     3.8   38.24
     4.6   38.64       5   39.34     6.8   39.34       7   40.44     9.3   40.44
     9.5   40.64    19.5   40.64
#Mann= 3 , 0 , 0
     -10    .033       0       0    .033       0     9.5    .033       0
Bank Sta=0,9.5
XS Rating Curve= 0
Exp/Cntr=.3,.1

Type RM Length L Ch R = 1 ,700.00  ,31,31,31
BEGIN DESCRIPTION:
14
END DESCRIPTION:
#Sta/Elev= 12
     -10   39.41       0   39.41     2.5   37.91     2.8   36.41     3.8   36.41
     4.6   36.71       5   37.31     6.8   37.31       7   38.21     9.3   38.21
     9.5   38.41    19.5   38.41
#Mann= 3 , 0 , 0
     -10    .033       0       0    .033       0     9.5    .033       0
Bank Sta=0,9.5
XS Rating Curve= 0
Exp/Cntr=.3,.1

Type RM Length L Ch R = 1 ,669.00  ,19,19,19
BEGIN DESCRIPTION:
13.019
END DESCRIPTION:
#Sta/Elev= 12
   -14.2   39.13    -4.2   39.13    -3.9   39.43    -3.4   39.43       0   37.83
      .5   36.53     3.4   36.53     4.1   36.63     4.4   37.23     4.8   37.63
    10.1   37.63    20.1   37.63
#Mann= 3 , 0 , 0
   -14.2    .033       0    -3.4    .033       0     4.8    .033       0
Bank Sta=-3.4,4.8
XS Rating Curve= 0
Exp/Cntr=.3,.1

Type RM Length L Ch R = 1 ,650.00  ,9,9,9
BEGIN DESCRIPTION:
13
END DESCRIPTION:
#Sta/Elev= 8
     -10   36.59       0   36.59      .4   35.99     5.6   35.99     5.8   36.99
     6.5   37.19     8.3   37.69    18.3   37.69
#Mann= 3 , 0 , 0
     -10    .033       0       0    .033       0     8.3    .033       0
Bank Sta=0,8.3
XS Rating Curve= 0
Exp/Cntr=.3,.1

Type RM Length L Ch R = 1 ,641.00  ,41,41,41
BEGIN DESCRIPTION:
12.041
END DESCRIPTION:
#Sta/Elev= 8
     -10   36.39       0   36.39      .4   35.29     5.6   35.29     5.8   36.29
     6.5   36.99     8.3   37.49    18.3   37.49
#Mann= 3 , 0 , 0
     -10    .033       0       0    .033       0     8.3    .033       0
Bank Sta=0,8.3
XS Rating Curve= 0
Exp/Cntr=.3,.1

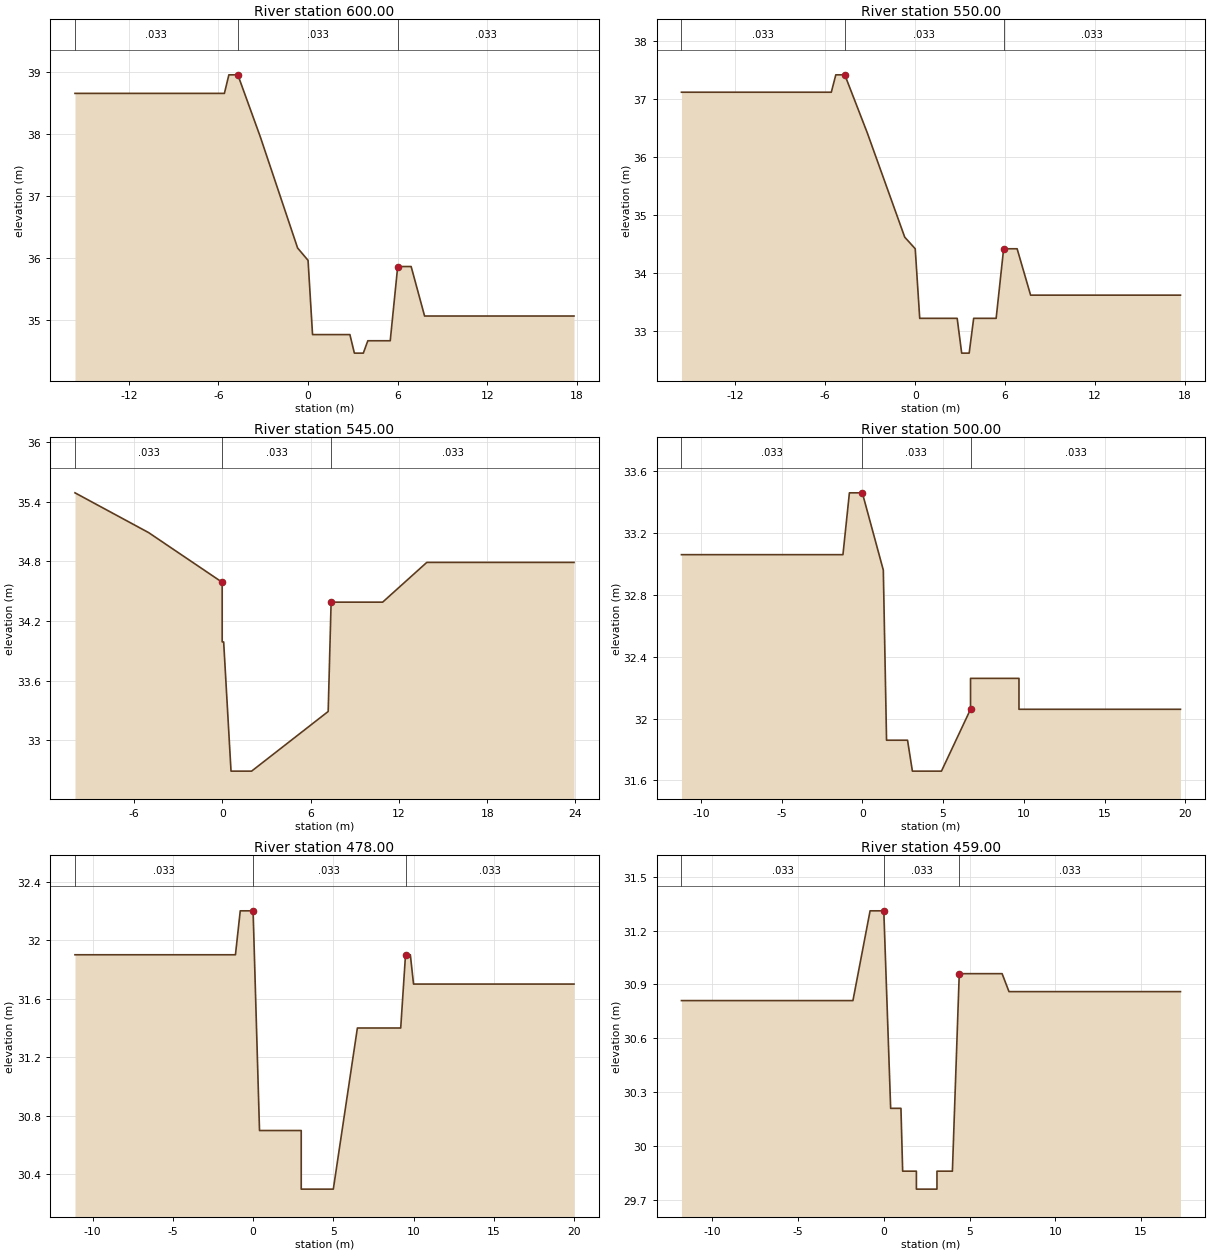
Type RM Length L Ch R = 1 ,600.00  ,50,50,50
BEGIN DESCRIPTION:
12
END DESCRIPTION:
#Sta/Elev= 17
   -15.6   38.66    -5.6   38.66    -5.3   38.96    -4.7   38.96    -3.2   37.96
     -.7   36.16       0   35.96      .3   34.76     2.8   34.76     3.1   34.46
     3.7   34.46       4   34.66     5.5   34.66       6   35.86     6.9   35.86
     7.8   35.06    17.8   35.06
#Mann= 3 , 0 , 0
   -15.6    .033       0    -4.7    .033       0       6    .033       0
Bank Sta=-4.7,6
XS Rating Curve= 0
Exp/Cntr=.3,.1

Type RM Length L Ch R = 1 ,550.00  ,5,5,5
BEGIN DESCRIPTION:
11
END DESCRIPTION:
#Sta/Elev= 17
   -15.6   37.12    -5.6   37.12    -5.3   37.42    -4.7   37.42    -3.2   36.42
     -.7   34.62       0   34.42      .3   33.22     2.8   33.22     3.1   32.62
     3.6   32.62     3.9   33.22     5.4   33.22     5.9   34.42     6.8   34.42
     7.7   33.62    17.7   33.62
#Mann= 3 , 0 , 0
   -15.6    .033       0    -4.7    .033       0     5.9    .033       0
Bank Sta=-4.7,5.9
XS Rating Curve= 0
Exp/Cntr=.3,.1

Type RM Length L Ch R = 1 ,545.00  ,45,45,45
BEGIN DESCRIPTION:
10.045
END DESCRIPTION:
#Sta/Elev= 12
     -10   35.49      -5   35.09       0   34.59       0   33.99      .1   33.99
      .6   32.69       2   32.69     7.2   33.29     7.4   34.39    10.9   34.39
    13.9   34.79    23.9   34.79
#Mann= 3 , 0 , 0
     -10    .033       0       0    .033       0     7.4    .033       0
Bank Sta=0,7.4
XS Rating Curve= 0
Exp/Cntr=.3,.1

Type RM Length L Ch R = 1 ,500.00  ,22,22,22
BEGIN DESCRIPTION:
10
END DESCRIPTION:
#Sta/Elev= 14
   -11.2   33.06    -1.2   33.06     -.8   33.46       0   33.46     1.3   32.96
     1.5   31.86     2.8   31.86     3.1   31.66     4.9   31.66     6.7   32.06
     6.7   32.26     9.7   32.26     9.7   32.06    19.7   32.06
#Mann= 3 , 0 , 0
   -11.2    .033       0       0    .033       0     6.7    .033       0
Bank Sta=0,6.7
XS Rating Curve= 0
Exp/Cntr=.3,.1

Type RM Length L Ch R = 1 ,478.00  ,19,19,19
BEGIN DESCRIPTION:
9.028
END DESCRIPTION:
#Sta/Elev= 15
   -11.1    31.9    -1.1    31.9     -.8    32.2       0    32.2      .4    30.7
       3    30.7       3    30.3       5    30.3     6.5    31.4       9    31.4
     9.2    31.4     9.5    31.9     9.8    31.9      10    31.7      20    31.7
#Mann= 3 , 0 , 0
   -11.1    .033       0       0    .033       0     9.5    .033       0
Bank Sta=0,9.5
XS Rating Curve= 0
Exp/Cntr=.3,.1

Type RM Length L Ch R = 1 ,459.00  ,9,9,9
BEGIN DESCRIPTION:
9.009
END DESCRIPTION:
#Sta/Elev= 16
   -11.8   30.81    -1.8   30.81     -.8   31.31       0   31.31      .4   30.21
       1   30.21     1.1   29.86     1.9   29.86     1.9   29.76     3.1   29.76
     3.1   29.86       4   29.86     4.4   30.96     6.9   30.96     7.3   30.86
    17.3   30.86
#Mann= 3 , 0 , 0
   -11.8    .033       0       0    .033       0     4.4    .033       0
Bank Sta=0,4.4
XS Rating Curve= 0
Exp/Cntr=.3,.1

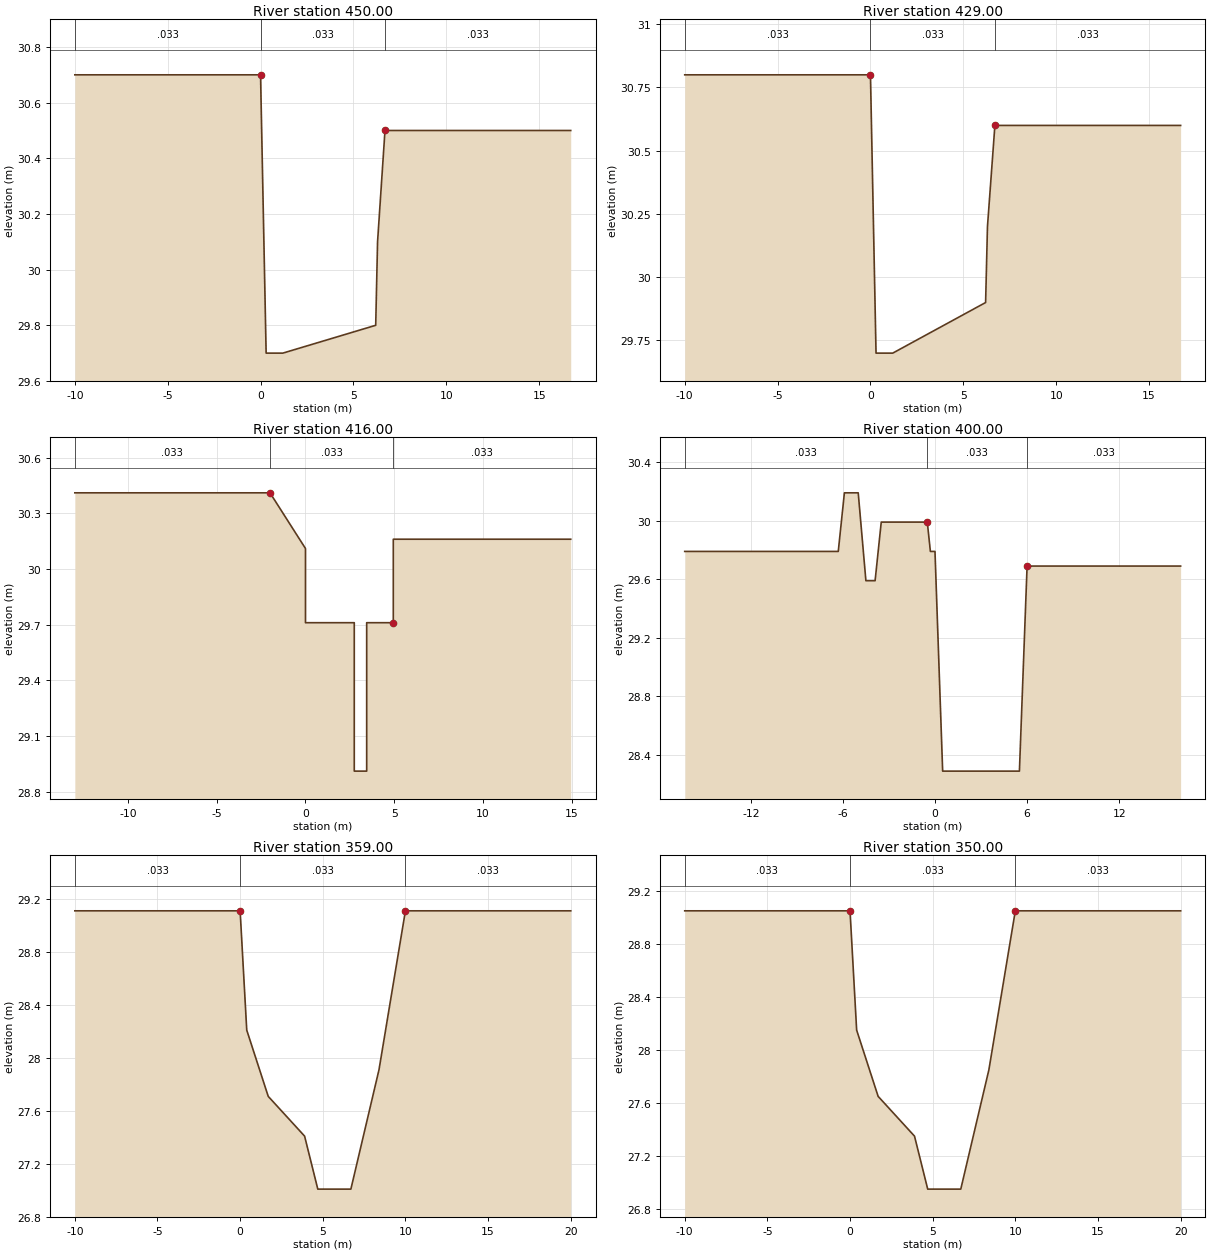
Type RM Length L Ch R = 1 ,450.00  ,21,21,21
BEGIN DESCRIPTION:
9
END DESCRIPTION:
#Sta/Elev= 8
     -10    30.7       0    30.7      .3    29.7     1.2    29.7     6.2    29.8
     6.3    30.1     6.7    30.5    16.7    30.5
#Mann= 3 , 0 , 0
     -10    .033       0       0    .033       0     6.7    .033       0
Bank Sta=0,6.7
XS Rating Curve= 0
Exp/Cntr=.3,.1

Type RM Length L Ch R = 1 ,429.00  ,13,13,13
BEGIN DESCRIPTION:
8.029
END DESCRIPTION:
#Sta/Elev= 8
     -10    30.8       0    30.8      .3    29.7     1.2    29.7     6.2    29.9
     6.3    30.2     6.7    30.6    16.7    30.6
#Mann= 3 , 0 , 0
     -10    .033       0       0    .033       0     6.7    .033       0
Bank Sta=0,6.7
XS Rating Curve= 0
Exp/Cntr=.3,.1

Type RM Length L Ch R = 1 ,416.00  ,16,16,16
BEGIN DESCRIPTION:
8.016
END DESCRIPTION:
#Sta/Elev= 12
     -13   30.41      -3   30.41      -2   30.41       0   30.11       0   29.71
    2.75   29.71    2.75   28.91    3.45   28.91    3.45   29.71    4.95   29.71
    4.95   30.16   14.95   30.16
#Mann= 3 , 0 , 0
     -13    .033       0      -2    .033       0    4.95    .033       0
Bank Sta=-2,4.95
XS Rating Curve= 0
Exp/Cntr=.3,.1

Type RM Length L Ch R = 1 ,400.00  ,41,41,41
BEGIN DESCRIPTION:
8
END DESCRIPTION:
#Sta/Elev= 14
   -16.3   29.79    -6.3   29.79    -5.9   30.19      -5   30.19    -4.5   29.59
    -3.9   29.59    -3.5   29.99     -.5   29.99     -.3   29.79       0   29.79
      .5   28.29     5.5   28.29       6   29.69      16   29.69
#Mann= 3 , 0 , 0
   -16.3    .033       0     -.5    .033       0       6    .033       0
Bank Sta=-.5,6
XS Rating Curve= 0
Exp/Cntr=.3,.1

Type RM Length L Ch R = 1 ,359.00  ,9,9,9
BEGIN DESCRIPTION:
7.009
END DESCRIPTION:
#Sta/Elev= 10
     -10   29.11       0   29.11      .4   28.21     1.7   27.71     3.9   27.41
     4.7   27.01     6.7   27.01     8.4   27.91      10   29.11      20   29.11
#Mann= 3 , 0 , 0
     -10    .033       0       0    .033       0      10    .033       0
Bank Sta=0,10
XS Rating Curve= 0
Exp/Cntr=.3,.1

Type RM Length L Ch R = 1 ,350.00  ,32,32,32
BEGIN DESCRIPTION:
7
END DESCRIPTION:
#Sta/Elev= 10
     -10   29.05       0   29.05      .4   28.15     1.7   27.65     3.9   27.35
     4.7   26.95     6.7   26.95     8.4   27.85      10   29.05      20   29.05
#Mann= 3 , 0 , 0
     -10    .033       0       0    .033       0      10    .033       0
Bank Sta=0,10
XS Rating Curve= 0
Exp/Cntr=.3,.1

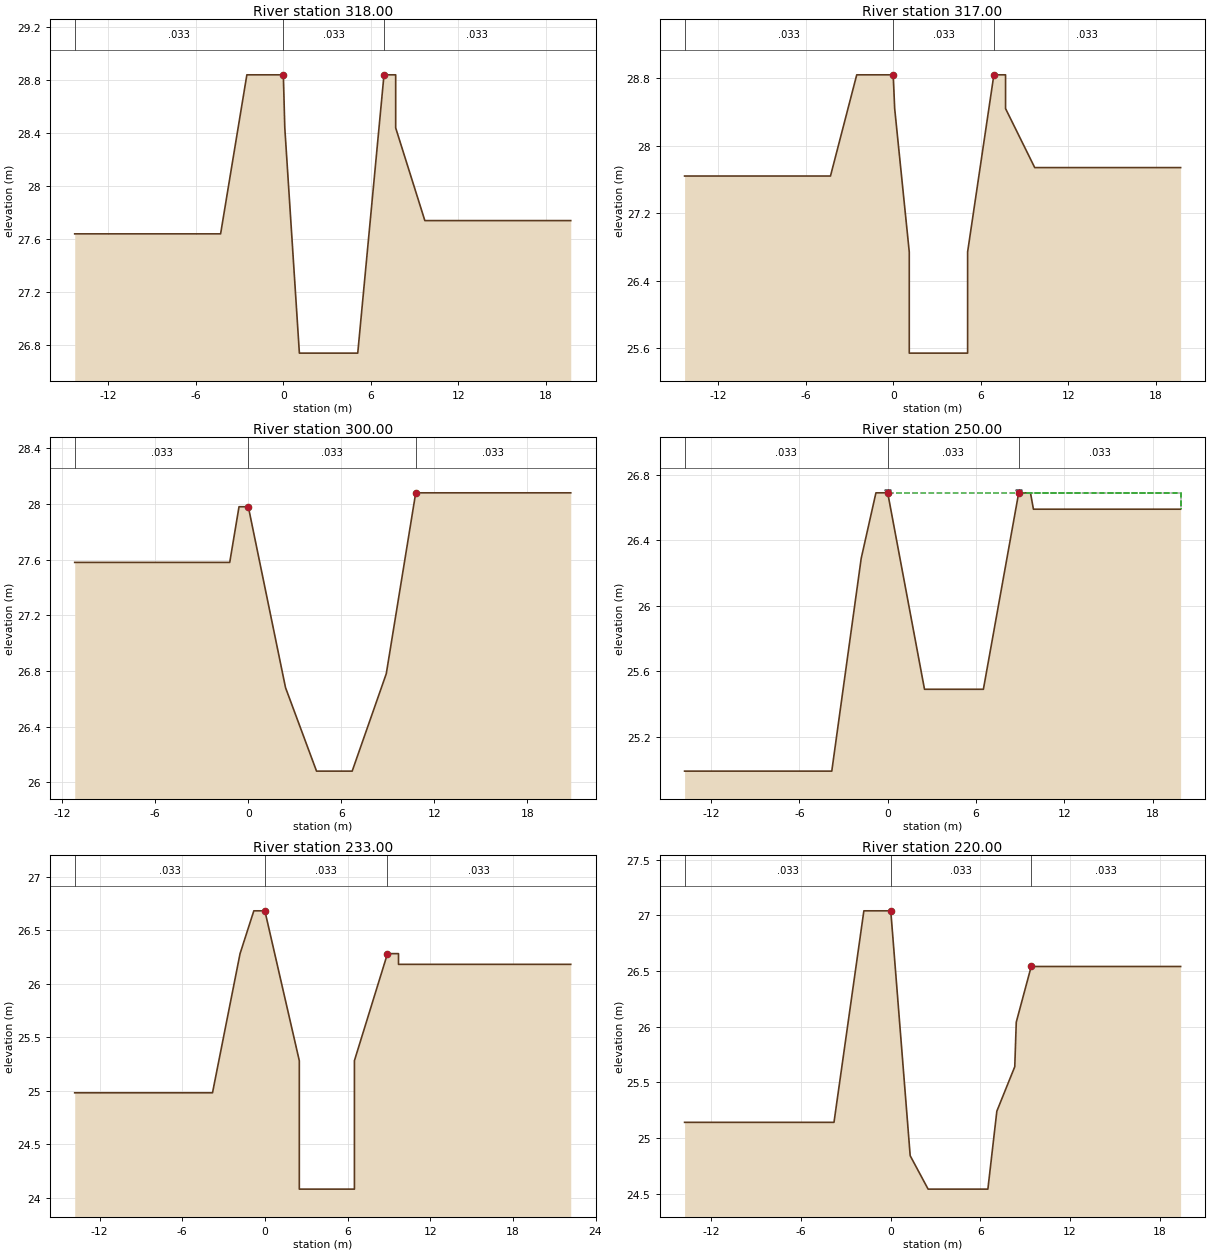
Type RM Length L Ch R = 1 ,318.00  ,1,1,1
BEGIN DESCRIPTION:
6.018
END DESCRIPTION:
#Sta/Elev= 12
   -14.3   27.64    -4.3   27.64    -2.5   28.84       0   28.84      .1   28.44
     1.1   26.74     5.1   26.74     6.9   28.84     7.7   28.84     7.7   28.44
     9.7   27.74    19.7   27.74
#Mann= 3 , 0 , 0
   -14.3    .033       0       0    .033       0     6.9    .033       0
Bank Sta=0,6.9
XS Rating Curve= 0
Exp/Cntr=.3,.1

Type RM Length L Ch R = 1 ,317.00  ,17,17,17
BEGIN DESCRIPTION:
6.017
END DESCRIPTION:
#Sta/Elev= 14
   -14.3   27.64    -4.3   27.64    -2.5   28.84       0   28.84      .1   28.44
     1.1   26.74     1.1   25.54     5.1   25.54     5.1   26.74     6.9   28.84
     7.7   28.84     7.7   28.44     9.7   27.74    19.7   27.74
#Mann= 3 , 0 , 0
   -14.3    .033       0       0    .033       0     6.9    .033       0
Bank Sta=0,6.9
XS Rating Curve= 0
Exp/Cntr=.3,.1

Type RM Length L Ch R = 1 ,300.00  ,50,50,50
BEGIN DESCRIPTION:
6
END DESCRIPTION:
#Sta/Elev= 10
   -11.2   27.58    -1.2   27.58     -.6   27.98       0   27.98     2.4   26.68
     4.4   26.08     6.7   26.08     8.9   26.78    10.8   28.08    20.8   28.08
#Mann= 3 , 0 , 0
   -11.2    .033       0       0    .033       0    10.8    .033       0
Bank Sta=0,10.8
XS Rating Curve= 0
Exp/Cntr=.3,.1

Type RM Length L Ch R = 1 ,250.00  ,17,17,17
BEGIN DESCRIPTION:
5
END DESCRIPTION:
#Sta/Elev= 11
   -13.8   24.99    -3.8   24.99    -1.8   26.29     -.8   26.69       0   26.69
     2.5   25.49     6.5   25.49     8.9   26.69     9.7   26.69     9.9   26.59
    19.9   26.59
#Mann= 3 , 0 , 0
   -13.8    .033       0       0    .033       0     8.9    .033       0
Levee=-1,0,26.69,-1,8.9,26.69,,
#XS Ineff= 2 , 0
       0       0   26.69     8.9       0   26.69
Permanent Ineff=
       F       F
Bank Sta=0,8.9
XS Rating Curve= 0
Exp/Cntr=.3,.1

Type RM Length L Ch R = 1 ,233.00  ,13,13,13
BEGIN DESCRIPTION:
4.033
END DESCRIPTION:
#Sta/Elev= 14
   -13.8   24.98    -3.8   24.98    -1.8   26.28     -.8   26.68       0   26.68
     2.5   25.28     2.5   24.08     6.5   24.08     6.5   25.28     8.9   26.28
     9.7   26.28     9.7   26.18    12.2   26.18    22.2   26.18
#Mann= 3 , 0 , 0
   -13.8    .033       0       0    .033       0     8.9    .033       0
Bank Sta=0,8.9
XS Rating Curve= 0
Exp/Cntr=.3,.1

Type RM Length L Ch R = 1 ,220.00  ,20,20,20
BEGIN DESCRIPTION:
4.02
END DESCRIPTION:
#Sta/Elev= 12
   -13.8   25.14    -3.8   25.14    -1.8   27.04       0   27.04     1.3   24.84
     2.5   24.54     6.5   24.54     7.1   25.24     8.3   25.64     8.4   26.04
     9.4   26.54    19.4   26.54
#Mann= 3 , 0 , 0
   -13.8    .033       0       0    .033       0     9.4    .033       0
Bank Sta=0,9.4
XS Rating Curve= 0
Exp/Cntr=.3,.1