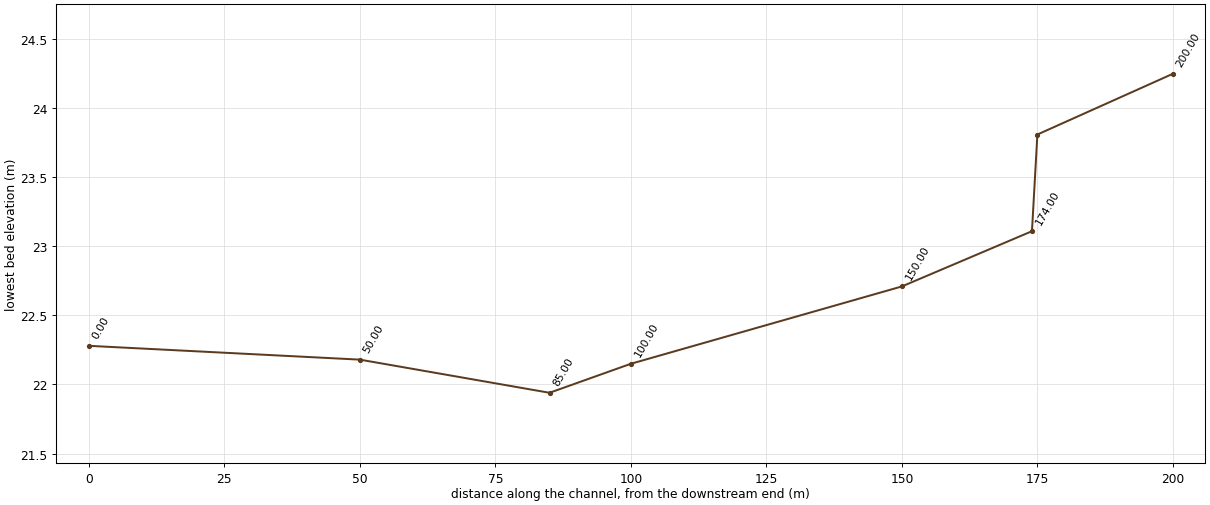
HEC-RAS study KU.prj: KUSAN

--- KU.g01 (geometry) --- (continued)

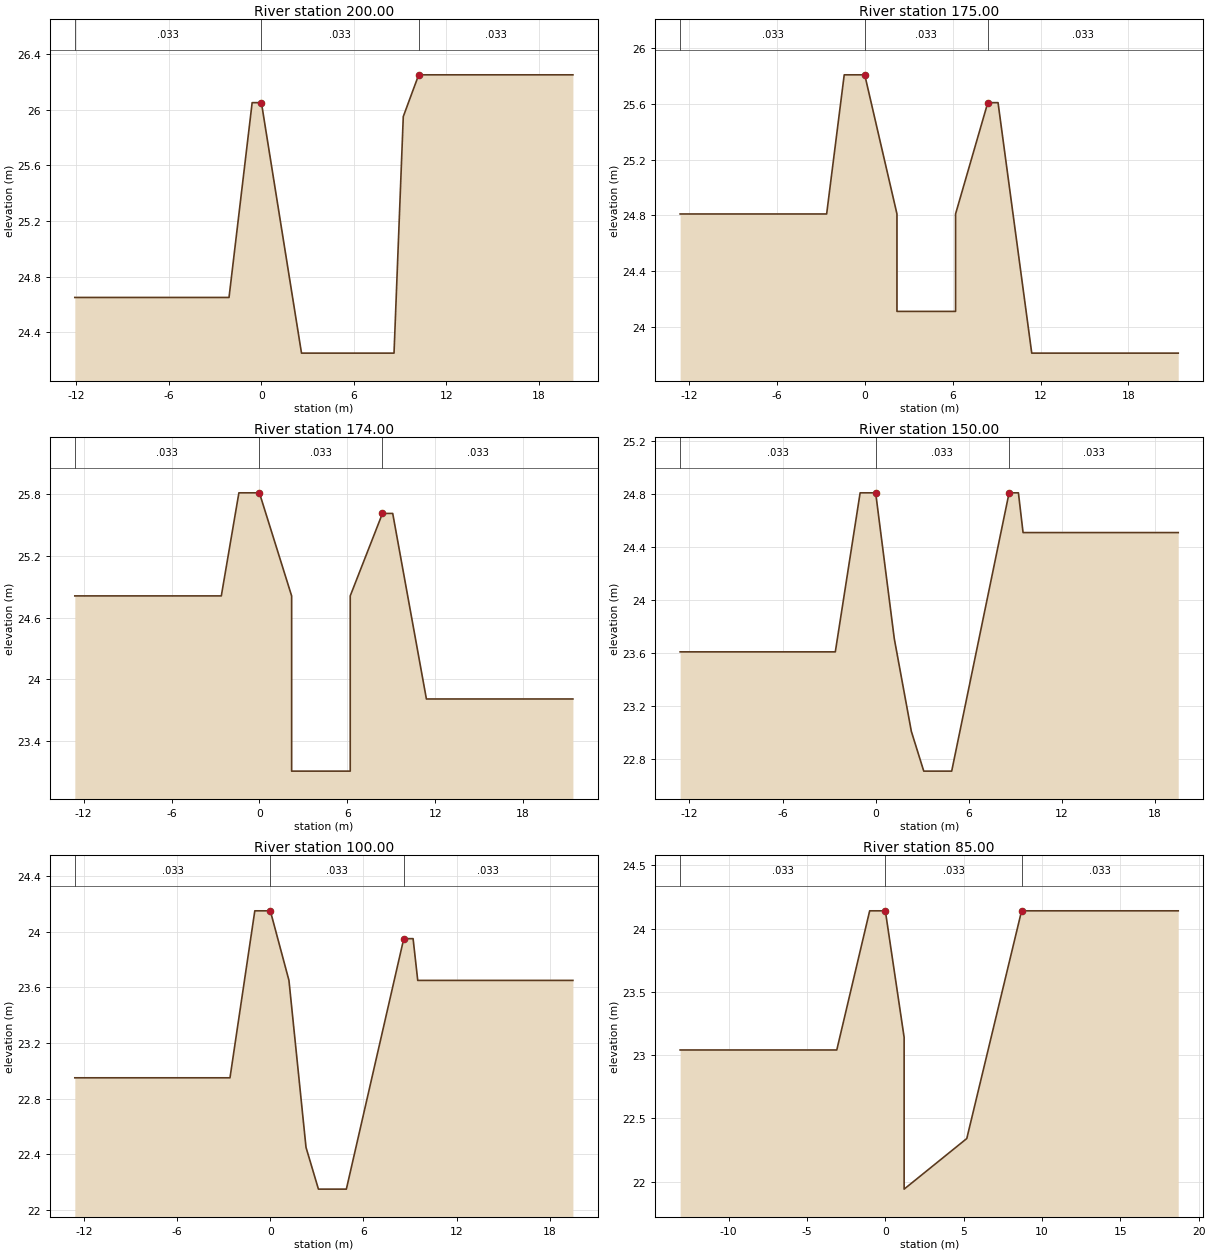
Type RM Length L Ch R = 1 ,200.00  ,25,25,25
BEGIN DESCRIPTION:
4
END DESCRIPTION:
#Sta/Elev= 9
   -12.1   24.65    -2.1   24.65     -.6   26.05       0   26.05     2.6   24.25
     8.6   24.25     9.2   25.95    10.2   26.25    20.2   26.25
#Mann= 3 , 0 , 0
   -12.1    .033       0       0    .033       0    10.2    .033       0
Bank Sta=0,10.2
XS Rating Curve= 0
Exp/Cntr=.3,.1

Type RM Length L Ch R = 1 ,175.00  ,1,1,1
BEGIN DESCRIPTION:
3.025
END DESCRIPTION:
#Sta/Elev= 12
   -12.6   24.81    -2.6   24.81    -1.4   25.81       0   25.81     2.2   24.81
     2.2   24.11     6.2   24.11     6.2   24.81     8.4   25.61     9.1   25.61
    11.4   23.81    21.4   23.81
#Mann= 3 , 0 , 0
   -12.6    .033       0       0    .033       0     8.4    .033       0
Bank Sta=0,8.4
XS Rating Curve= 0
Exp/Cntr=.3,.1

Type RM Length L Ch R = 1 ,174.00  ,24,24,24
BEGIN DESCRIPTION:
3.024
END DESCRIPTION:
#Sta/Elev= 14
   -12.6   24.81    -2.6   24.81    -1.4   25.81       0   25.81     2.2   24.81
     2.2   24.11     2.2   23.11     6.2   23.11     6.2   24.11     6.2   24.81
     8.4   25.61     9.1   25.61    11.4   23.81    21.4   23.81
#Mann= 3 , 0 , 0
   -12.6    .033       0       0    .033       0     8.4    .033       0
Bank Sta=0,8.4
XS Rating Curve= 0
Exp/Cntr=.3,.1

Type RM Length L Ch R = 1 ,150.00  ,50,50,50
BEGIN DESCRIPTION:
3
END DESCRIPTION:
#Sta/Elev= 12
   -12.6   23.61    -2.6   23.61      -1   24.81       0   24.81     1.2   23.71
     2.3   23.01     3.1   22.71     4.9   22.71     8.6   24.81     9.2   24.81
     9.5   24.51    19.5   24.51
#Mann= 3 , 0 , 0
   -12.6    .033       0       0    .033       0     8.6    .033       0
Bank Sta=0,8.6
XS Rating Curve= 0
Exp/Cntr=.3,.1

Type RM Length L Ch R = 1 ,100.00  ,15,15,15
BEGIN DESCRIPTION:
2
END DESCRIPTION:
#Sta/Elev= 12
   -12.6   22.95    -2.6   22.95      -1   24.15       0   24.15     1.2   23.65
     2.3   22.45     3.1   22.15     4.9   22.15     8.6   23.95     9.2   23.95
     9.5   23.65    19.5   23.65
#Mann= 3 , 0 , 0
   -12.6    .033       0       0    .033       0     8.6    .033       0
Bank Sta=0,8.6
XS Rating Curve= 0
Exp/Cntr=.3,.1

Type RM Length L Ch R = 1 ,85.00   ,35,35,35
BEGIN DESCRIPTION:
1.035
END DESCRIPTION:
#Sta/Elev= 10
   -13.1   23.04    -3.1   23.04      -1   24.14       0   24.14     1.2   23.14
     1.2   21.94     3.2   22.14     5.2   22.34     8.7   24.14    18.7   24.14
#Mann= 3 , 0 , 0
   -13.1    .033       0       0    .033       0     8.7    .033       0
Bank Sta=0,8.7
XS Rating Curve= 0
Exp/Cntr=.3,.1

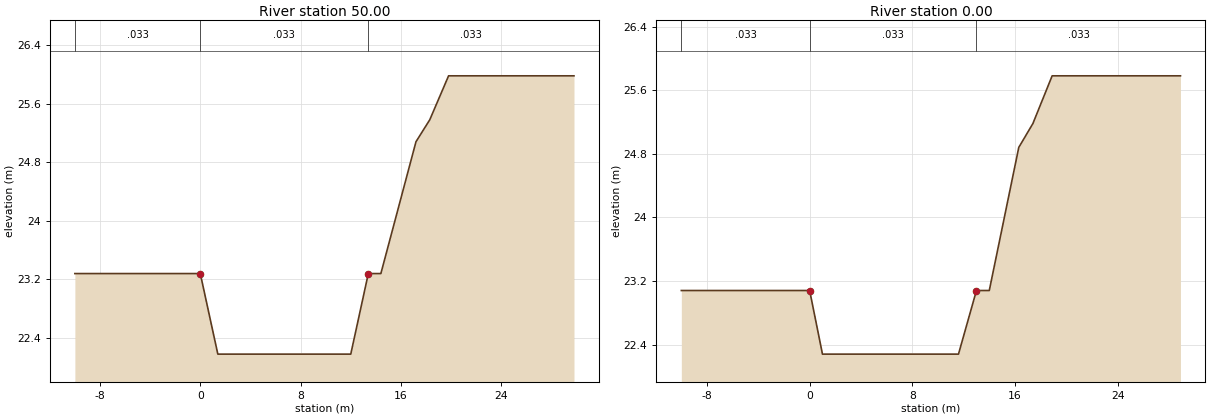
Type RM Length L Ch R = 1 ,50.00   ,50,50,50
BEGIN DESCRIPTION:
1
END DESCRIPTION:
#Sta/Elev= 10
     -10   23.28       0   23.28     1.4   22.18      12   22.18    13.4   23.28
    14.4   23.28    17.2   25.08    18.3   25.38    19.8   25.98    29.8   25.98
#Mann= 3 , 0 , 0
     -10    .033       0       0    .033       0    13.4    .033       0
Bank Sta=0,13.4
XS Rating Curve= 0
Exp/Cntr=.3,.1

Type RM Length L Ch R = 1 ,0.00    ,0,0,0
BEGIN DESCRIPTION:
0
END DESCRIPTION:
#Sta/Elev= 10
     -10   23.08       0   23.08       1   22.28    11.6   22.28      13   23.08
      14   23.08    16.3   24.88    17.4   25.18    18.9   25.78    28.9   25.78
#Mann= 3 , 0 , 0
     -10    .033       0       0    .033       0      13    .033       0
Bank Sta=0,13
XS Rating Curve= 0
Exp/Cntr=.3,.1

Chan Stop Cuts=-1