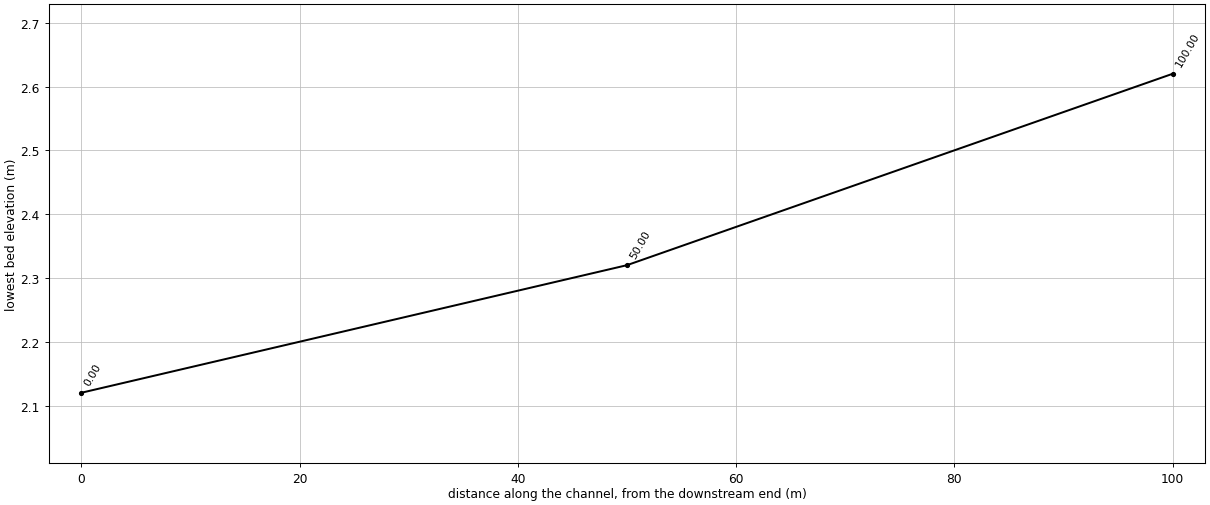
HEC-RAS study BUR.prj: BUR

--- BUR.g01 (geometry) --- (continued)

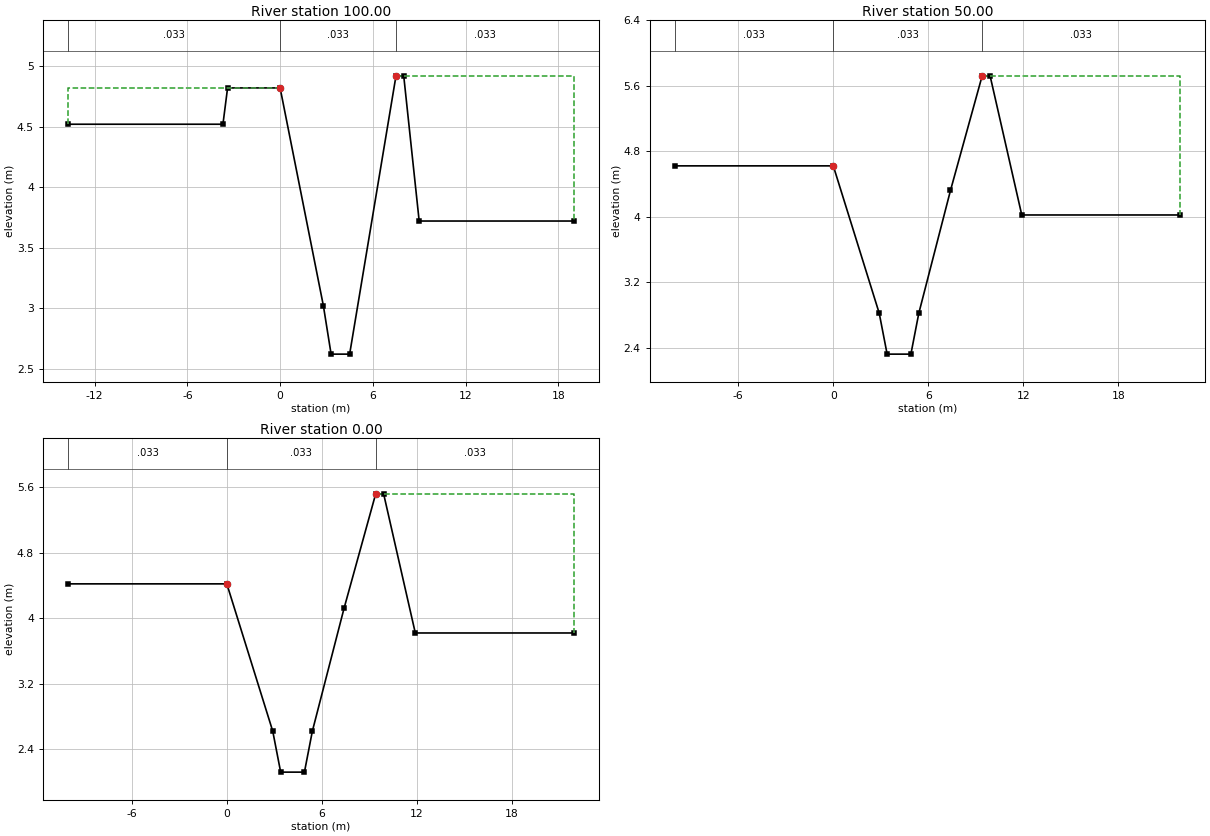
Type RM Length L Ch R = 1 ,100.00  ,50,50,50
BEGIN DESCRIPTION:
2
END DESCRIPTION:
#Sta/Elev= 11
   -13.7    4.52    -3.7    4.52    -3.4    4.82       0    4.82     2.8    3.02
     3.3    2.62     4.5    2.62     7.5    4.92       8    4.92       9    3.72
      19    3.72
#Mann= 3 , 0 , 0
   -13.7    .033       0       0    .033       0     7.5    .033       0
#XS Ineff= 2 , 0
               0    4.82     7.5            4.92
Permanent Ineff=
       F       F
Bank Sta=0,7.5
XS Rating Curve= 0
Exp/Cntr=.3,.1

Type RM Length L Ch R = 1 ,50.00   ,50,50,50
BEGIN DESCRIPTION:
1
END DESCRIPTION:
#Sta/Elev= 11
     -10    4.62       0    4.62     2.9    2.82     3.4    2.32     4.9    2.32
     5.4    2.82     7.4    4.32     9.4    5.72     9.9    5.72    11.9    4.02
    21.9    4.02
#Mann= 3 , 0 , 0
     -10    .033       0       0    .033       0     9.4    .033       0
#XS Ineff= 2 , 0
               0    4.62     9.4            5.72
Permanent Ineff=
       F       F
Bank Sta=0,9.4
XS Rating Curve= 0
Exp/Cntr=.3,.1

Type RM Length L Ch R = 1 ,0.00    ,0,0,0
BEGIN DESCRIPTION:
0
END DESCRIPTION:
#Sta/Elev= 11
     -10    4.42       0    4.42     2.9    2.62     3.4    2.12     4.9    2.12
     5.4    2.62     7.4    4.12     9.4    5.52     9.9    5.52    11.9    3.82
    21.9    3.82
#Mann= 3 , 0 , 0
     -10    .033       0       0    .033       0     9.4    .033       0
#XS Ineff= 2 , 0
               0    4.42     9.4            5.52
Permanent Ineff=
       F       F
Bank Sta=0,9.4
XS Rating Curve= 0
Exp/Cntr=.3,.1

Chan Stop Cuts=-1