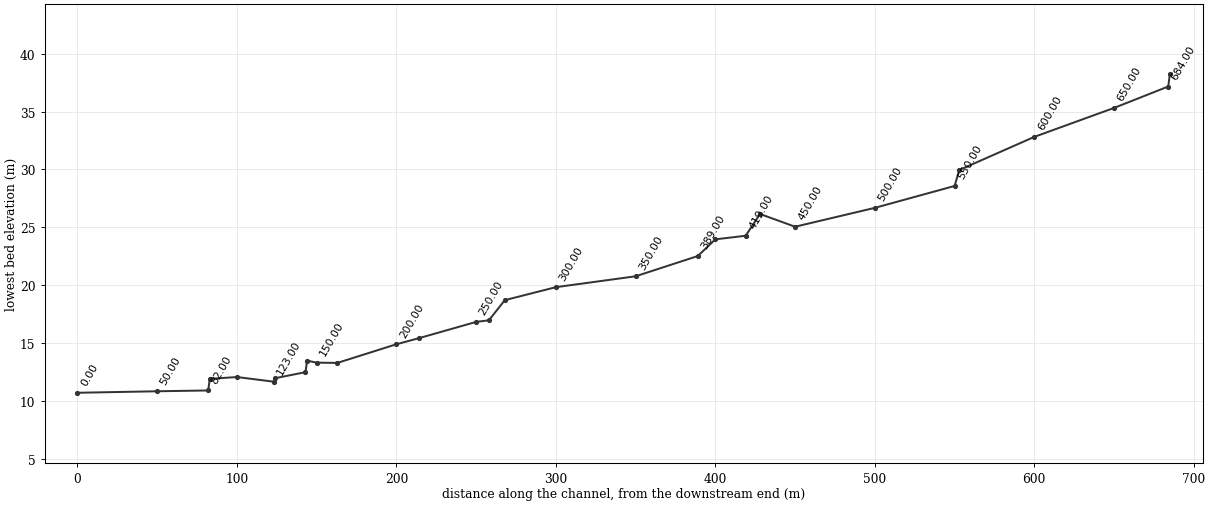
--- SAJAC.prj (project) ---

Proj Title=SAJAC
Current Plan=p01
Default Exp/Contr=.3,.1
SI Units
Geom File=g01
Flow File=f01
Plan File=p01
Y Axis Title=Elevation
X Axis Title(PF)=Main Channel Distance
X Axis Title(XS)=Station
BEGIN DESCRIPTION:
           BACK WATER COMPUTATION
      APPLICATION OF HEC-2 BY Samju Construction Engineering
      SAJAKGOL-STREEM : 30 YR
END DESCRIPTION:
DSS Export Rating Curves= 0
DSS Export Rating Curve Sorted= 0
DSS Export Volume Flow Curves= 0
DXF OffsetX= 0
DXF OffsetY= 0
DXF ScaleX= 1
DXF ScaleY= 10

--- SAJAC.p01 (plan) ---

Plan Title=Imported Plan 01
Version=Version 3.0.1  Mar 2001
Short Identifier=Imported Pla
Geom File=g01
Flow File=f01
Subcritical Flow
K Sum by GR= 0
Std Step Tol= 0.003
Critical Tol= 0.003
Num of Std Step Trials= 20
Max Error Tol= 0.1
Flow Tol Ratio= 0.001
Split Flow NTrial= 30
Split Flow Tol= 0.02
Split Flow Ratio= 0.02
Log Output Level= 0
Friction Slope Method= 1
Unsteady Friction Slope Method= 2
Parabolic Critical Depth
Global Vel Dist= 0 , 0 , 0
Global Log Level= 0
CheckData=True
Encroach Param=-1 ,0,0, 0
Computation Interval=1HOUR
Output Interval=1HOUR
Run HTab= 0
Run UNet= 0
Run PostProcess= 0
UNET Theta= 1
UNET ZTol= 0.02
UNET ZSATol= 0.1
UNET MxIter= 20
UNET MaxInSteps= 20
UNET DtIC= 0
UNET DtMin= 0
UNET MaxCRTS= 20
UNET WFStab= 2
UNET SFStab= 1
UNET WFX= 1
UNET SFX= 1
UNET Convert EG Bridges=-1
UNET Use Existing IB Tables=-1
Instantaneous Interval=1HOUR
Write IC File= 0
Write Velocity= 0
Write Detailed= 0

--- SAJAC.f01 (steady flow) ---

Flow Title=Imported Flow 01
Version=Version 3.0.1  Mar 2001
Number of Profiles= 5
Profile Names=10YR,20YR,30YR,50YR,80YR
River Rch & RM=RIVER-1,Reach-1         ,685.00
    1.65    1.82    1.92    2.04    2.16
Boundary for River Rch & Prof#=RIVER-1,Reach-1         , 1
Up Type= 0
Dn Type= 3
Dn Slope=.04
Boundary for River Rch & Prof#=RIVER-1,Reach-1         , 2
Up Type= 0
Dn Type= 3
Dn Slope=.04
Boundary for River Rch & Prof#=RIVER-1,Reach-1         , 3
Up Type= 0
Dn Type= 3
Dn Slope=.04
Boundary for River Rch & Prof#=RIVER-1,Reach-1         , 4
Up Type= 0
Dn Type= 3
Dn Slope=.04
Boundary for River Rch & Prof#=RIVER-1,Reach-1         , 5
Up Type= 0
Dn Type= 3
Dn Slope=.04
DSS Import GetInterval= 0
DSS Import GetPeak= 0
DSS Import FillOption= 0

--- SAJAC.g01 (geometry) ---

Geom Title=Imported Geom 01
Version=Version 3.0.1  Mar 2001

River Reach=RIVER-1         ,Reach-1
Reach XY= 2
              .5             .95              .5             .05

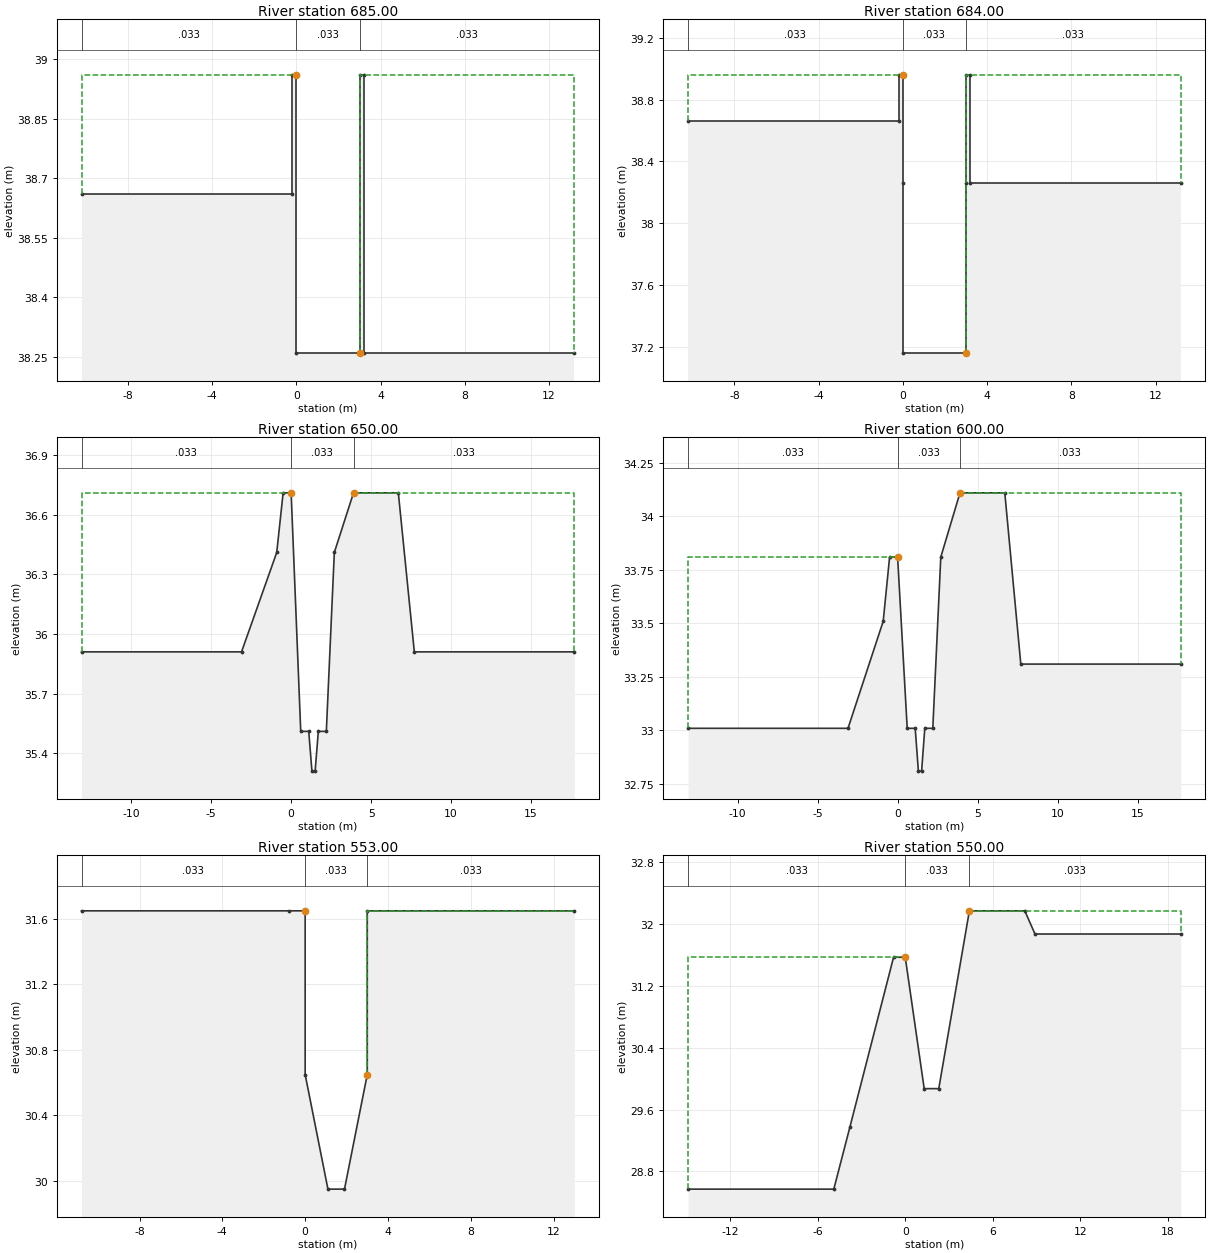
Type RM Length L Ch R = 1 ,685.00  ,1,1,1
BEGIN DESCRIPTION:
13.035
END DESCRIPTION:
#Sta/Elev= 10
   -10.2   38.66     -.2   38.66     -.2   38.96       0   38.96       0   38.26
       3   38.26       3   38.96     3.2   38.96     3.2   38.26    13.2   38.26
#Mann= 3 , 0 , 0
   -10.2    .033       0       0    .033       0       3    .033       0
#XS Ineff= 2 , 0
               0   38.96       3           38.96
Permanent Ineff=
       F       F
Bank Sta=0,3
XS Rating Curve= 0
Exp/Cntr=.3,.1

Type RM Length L Ch R = 1 ,684.00  ,34,34,34
BEGIN DESCRIPTION:
13.034
END DESCRIPTION:
#Sta/Elev= 12
   -10.2   38.66     -.2   38.66     -.2   38.96       0   38.96       0   38.26
       0   37.16       3   37.16       3   38.26       3   38.96     3.2   38.96
     3.2   38.26    13.2   38.26
#Mann= 3 , 0 , 0
   -10.2    .033       0       0    .033       0       3    .033       0
#XS Ineff= 2 , 0
               0   38.96       3           38.96
Permanent Ineff=
       F       F
Bank Sta=0,3
XS Rating Curve= 0
Exp/Cntr=.3,.1

Type RM Length L Ch R = 1 ,650.00  ,50,50,50
BEGIN DESCRIPTION:
13
END DESCRIPTION:
#Sta/Elev= 16
   -13.1   35.91    -3.1   35.91     -.9   36.41     -.5   36.71       0   36.71
      .6   35.51     1.1   35.51     1.3   35.31     1.5   35.31     1.7   35.51
     2.2   35.51     2.7   36.41     3.9   36.71     6.7   36.71     7.7   35.91
    17.7   35.91
#Mann= 3 , 0 , 0
   -13.1    .033       0       0    .033       0     3.9    .033       0
#XS Ineff= 2 , 0
               0   36.71     3.9           36.71
Permanent Ineff=
       F       F
Bank Sta=0,3.9
XS Rating Curve= 0
Exp/Cntr=.3,.1

Type RM Length L Ch R = 1 ,600.00  ,47,47,47
BEGIN DESCRIPTION:
12
END DESCRIPTION:
#Sta/Elev= 16
   -13.1   33.01    -3.1   33.01     -.9   33.51     -.5   33.81       0   33.81
      .6   33.01     1.1   33.01     1.3   32.81     1.5   32.81     1.7   33.01
     2.2   33.01     2.7   33.81     3.9   34.11     6.7   34.11     7.7   33.31
    17.7   33.31
#Mann= 3 , 0 , 0
   -13.1    .033       0       0    .033       0     3.9    .033       0
#XS Ineff= 2 , 0
               0   33.81     3.9           34.11
Permanent Ineff=
       F       F
Bank Sta=0,3.9
XS Rating Curve= 0
Exp/Cntr=.3,.1

Type RM Length L Ch R = 1 ,553.00  ,3,3,3
BEGIN DESCRIPTION:
11.003
END DESCRIPTION:
#Sta/Elev= 9
   -10.8   31.65     -.8   31.65       0   31.65       0   30.65     1.1   29.95
     1.9   29.95       3   30.65       3   31.65      13   31.65
#Mann= 3 , 0 , 0
   -10.8    .033       0       0    .033       0       3    .033       0
#XS Ineff= 2 , 0
               0   31.65       3           31.65
Permanent Ineff=
       F       F
Bank Sta=0,3
XS Rating Curve= 0
Exp/Cntr=.3,.1

Type RM Length L Ch R = 1 ,550.00  ,50,50,50
BEGIN DESCRIPTION:
11
END DESCRIPTION:
#Sta/Elev= 11
   -14.9   28.57    -4.9   28.57    -3.8   29.37     -.8   31.57       0   31.57
     1.3   29.87     2.3   29.87     4.4   32.17     8.2   32.17     8.9   31.87
    18.9   31.87
#Mann= 3 , 0 , 0
   -14.9    .033       0       0    .033       0     4.4    .033       0
#XS Ineff= 2 , 0
               0   31.57     4.4           32.17
Permanent Ineff=
       F       F
Bank Sta=0,4.4
XS Rating Curve= 0
Exp/Cntr=.3,.1

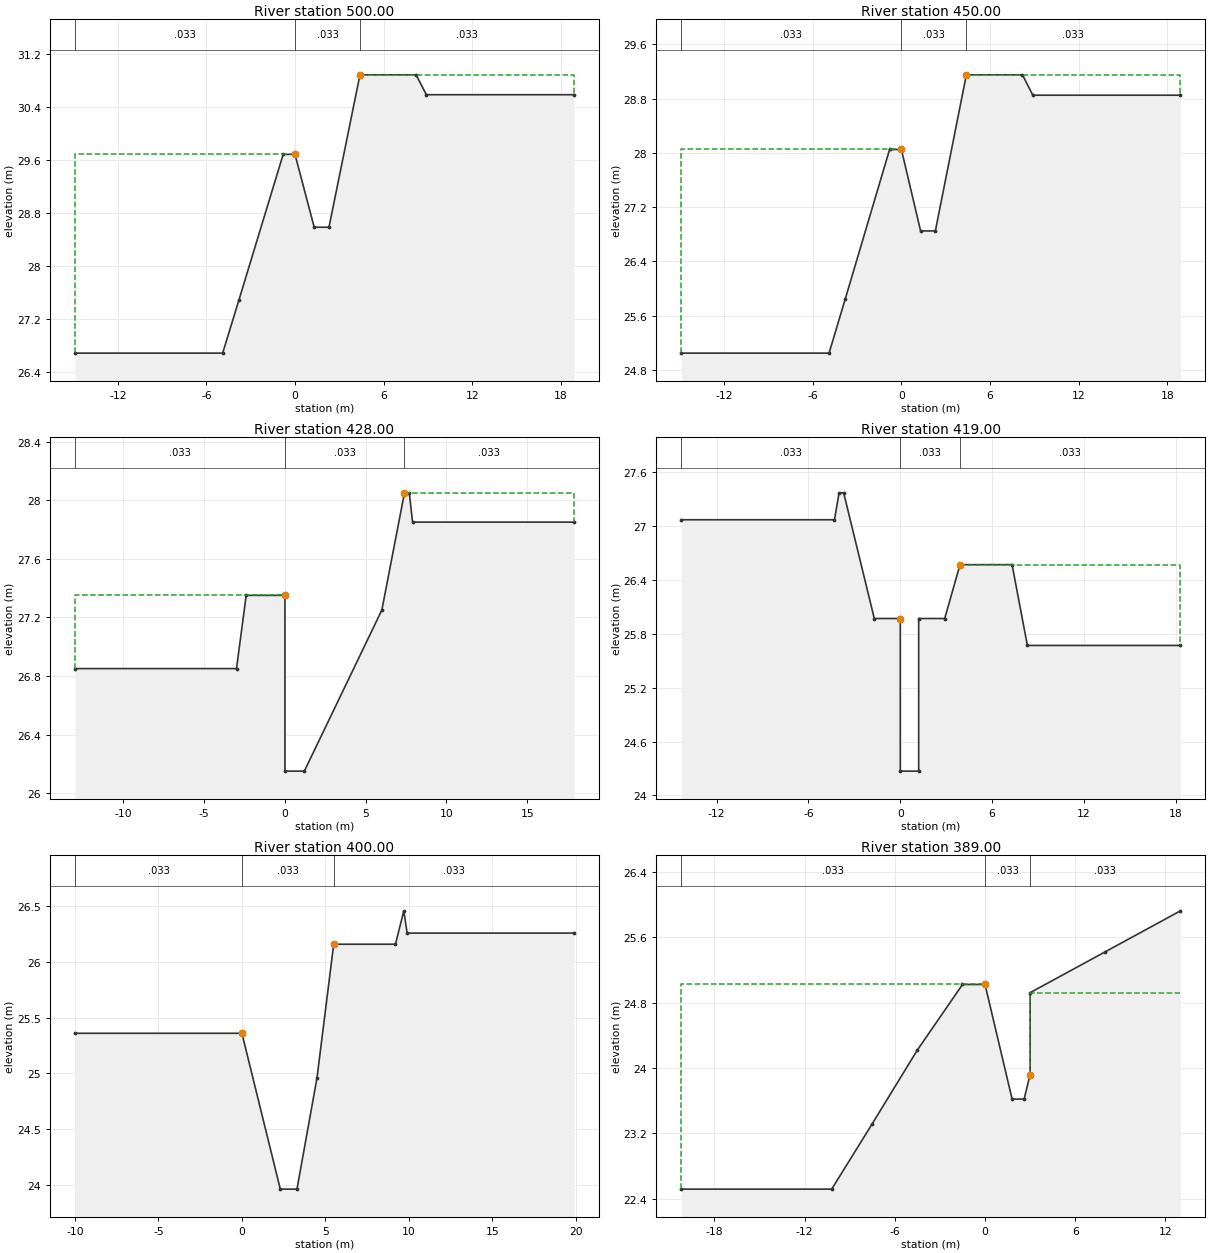
Type RM Length L Ch R = 1 ,500.00  ,50,50,50
BEGIN DESCRIPTION:
10
END DESCRIPTION:
#Sta/Elev= 11
   -14.9   26.68    -4.9   26.68    -3.8   27.48     -.8   29.68       0   29.68
     1.3   28.58     2.3   28.58     4.4   30.88     8.2   30.88     8.9   30.58
    18.9   30.58
#Mann= 3 , 0 , 0
   -14.9    .033       0       0    .033       0     4.4    .033       0
#XS Ineff= 2 , 0
               0   29.68     4.4           30.88
Permanent Ineff=
       F       F
Bank Sta=0,4.4
XS Rating Curve= 0
Exp/Cntr=.3,.1

Type RM Length L Ch R = 1 ,450.00  ,22,22,22
BEGIN DESCRIPTION:
9
END DESCRIPTION:
#Sta/Elev= 11
   -14.9   25.05    -4.9   25.05    -3.8   25.85     -.8   28.05       0   28.05
     1.3   26.85     2.3   26.85     4.4   29.15     8.2   29.15     8.9   28.85
    18.9   28.85
#Mann= 3 , 0 , 0
   -14.9    .033       0       0    .033       0     4.4    .033       0
#XS Ineff= 2 , 0
               0   28.05     4.4           29.15
Permanent Ineff=
       F       F
Bank Sta=0,4.4
XS Rating Curve= 0
Exp/Cntr=.3,.1

Type RM Length L Ch R = 1 ,428.00  ,9,9,9
BEGIN DESCRIPTION:
8.028
END DESCRIPTION:
#Sta/Elev= 11
     -13   26.85      -3   26.85    -2.4   27.35       0   27.35       0   26.15
     1.2   26.15       6   27.25     7.4   28.05     7.7   28.05     7.9   27.85
    17.9   27.85
#Mann= 3 , 0 , 0
     -13    .033       0       0    .033       0     7.4    .033       0
#XS Ineff= 2 , 0
               0   27.35     7.4           28.05
Permanent Ineff=
       F       F
Bank Sta=0,7.4
XS Rating Curve= 0
Exp/Cntr=.3,.1

Type RM Length L Ch R = 1 ,419.00  ,19,19,19
BEGIN DESCRIPTION:
8.019
END DESCRIPTION:
#Sta/Elev= 14
   -14.3   27.07    -4.3   27.07      -4   27.37    -3.7   27.37    -1.7   25.97
       0   25.97       0   24.27     1.2   24.27     1.2   25.97     2.9   25.97
     3.9   26.57     7.3   26.57     8.3   25.67    18.3   25.67
#Mann= 3 , 0 , 0
   -14.3    .033       0       0    .033       0     3.9    .033       0
#XS Ineff= 2 , 0
               0   25.97     3.9           26.57
Permanent Ineff=
       F       F
Bank Sta=0,3.9
XS Rating Curve= 0
Exp/Cntr=.3,.1

Type RM Length L Ch R = 1 ,400.00  ,11,11,11
BEGIN DESCRIPTION:
8
END DESCRIPTION:
#Sta/Elev= 10
     -10   25.36       0   25.36     2.3   23.96     3.3   23.96     4.5   24.96
     5.5   26.16     9.2   26.16     9.7   26.46     9.9   26.26    19.9   26.26
#Mann= 3 , 0 , 0
     -10    .033       0       0    .033       0     5.5    .033       0
#XS Ineff= 2 , 0
               0   25.36     5.5           26.16
Permanent Ineff=
       F       F
Bank Sta=0,5.5
XS Rating Curve= 0
Exp/Cntr=.3,.1

Type RM Length L Ch R = 1 ,389.00  ,39,39,39
BEGIN DESCRIPTION:
7.039
END DESCRIPTION:
#Sta/Elev= 12
   -20.2   22.52   -10.2   22.52    -7.5   23.32    -4.5   24.22    -1.5   25.02
       0   25.02     1.8   23.62     2.6   23.62       3   23.92       3   24.92
       8   25.42      13   25.92
#Mann= 3 , 0 , 0
   -20.2    .033       0       0    .033       0       3    .033       0
#XS Ineff= 2 , 0
               0   25.02       3           24.92
Permanent Ineff=
       F       F
Bank Sta=0,3
XS Rating Curve= 0
Exp/Cntr=.3,.1

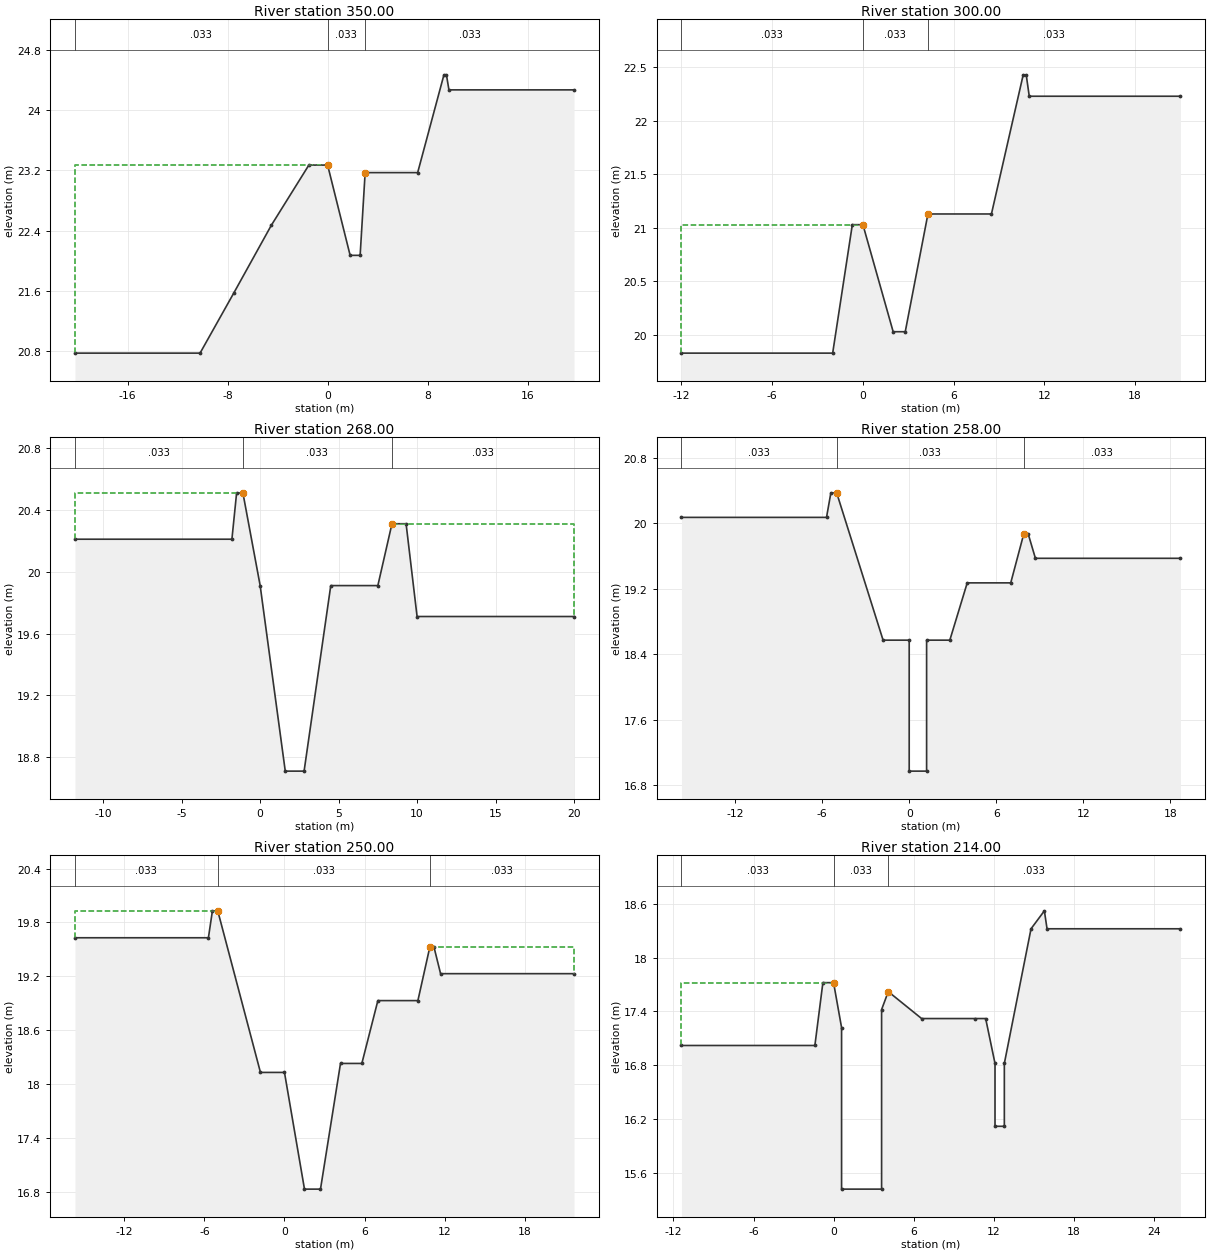
Type RM Length L Ch R = 1 ,350.00  ,50,50,50
BEGIN DESCRIPTION:
7
END DESCRIPTION:
#Sta/Elev= 14
   -20.2   20.77   -10.2   20.77    -7.5   21.57    -4.5   22.47    -1.5   23.27
       0   23.27     1.8   22.07     2.6   22.07       3   23.17     7.2   23.17
     9.3   24.47     9.5   24.47     9.7   24.27    19.7   24.27
#Mann= 3 , 0 , 0
   -20.2    .033       0       0    .033       0       3    .033       0
#XS Ineff= 2 , 0
               0   23.27       3           23.17
Permanent Ineff=
       F       F
Bank Sta=0,3
XS Rating Curve= 0
Exp/Cntr=.3,.1

Type RM Length L Ch R = 1 ,300.00  ,32,32,32
BEGIN DESCRIPTION:
6
END DESCRIPTION:
#Sta/Elev= 12
     -12   19.83      -2   19.83     -.7   21.03       0   21.03       2   20.03
     2.8   20.03     4.3   21.13     8.5   21.13    10.6   22.43    10.8   22.43
      11   22.23      21   22.23
#Mann= 3 , 0 , 0
     -12    .033       0       0    .033       0     4.3    .033       0
#XS Ineff= 2 , 0
               0   21.03     4.3           21.13
Permanent Ineff=
       F       F
Bank Sta=0,4.3
XS Rating Curve= 0
Exp/Cntr=.3,.1

Type RM Length L Ch R = 1 ,268.00  ,10,10,10
BEGIN DESCRIPTION:
5.018
END DESCRIPTION:
#Sta/Elev= 13
   -11.8   20.21    -1.8   20.21    -1.5   20.51    -1.1   20.51       0   19.91
     1.6   18.71     2.8   18.71     4.5   19.91     7.5   19.91     8.4   20.31
     9.3   20.31      10   19.71      20   19.71
#Mann= 3 , 0 , 0
   -11.8    .033       0    -1.1    .033       0     8.4    .033       0
#XS Ineff= 2 , 0
            -1.1   20.51     8.4           20.31
Permanent Ineff=
       F       F
Bank Sta=-1.1,8.4
XS Rating Curve= 0
Exp/Cntr=.3,.1

Type RM Length L Ch R = 1 ,258.00  ,8,8,8
BEGIN DESCRIPTION:
5.008
END DESCRIPTION:
#Sta/Elev= 16
   -15.7   20.07    -5.7   20.07    -5.4   20.37      -5   20.37    -1.8   18.57
       0   18.57       0   16.97     1.2   16.97     1.2   18.57     2.8   18.57
       4   19.27       7   19.27     7.9   19.87     8.2   19.87     8.7   19.57
    18.7   19.57
#Mann= 3 , 0 , 0
   -15.7    .033       0      -5    .033       0     7.9    .033       0
Bank Sta=-5,7.9
XS Rating Curve= 0
Exp/Cntr=.3,.1

Type RM Length L Ch R = 1 ,250.00  ,36,36,36
BEGIN DESCRIPTION:
5
END DESCRIPTION:
#Sta/Elev= 16
   -15.7   19.63    -5.7   19.63    -5.4   19.93      -5   19.93    -1.8   18.13
       0   18.13     1.5   16.83     2.7   16.83     4.2   18.23     5.8   18.23
       7   18.93      10   18.93    10.9   19.53    11.2   19.53    11.7   19.23
    21.7   19.23
#Mann= 3 , 0 , 0
   -15.7    .033       0      -5    .033       0    10.9    .033       0
#XS Ineff= 2 , 0
              -5   19.93    10.9           19.53
Permanent Ineff=
       F       F
Bank Sta=-5,10.9
XS Rating Curve= 0
Exp/Cntr=.3,.1

Type RM Length L Ch R = 1 ,214.00  ,14,14,14
BEGIN DESCRIPTION:
4.014
END DESCRIPTION:
#Sta/Elev= 20
   -11.4   17.02    -1.4   17.02     -.8   17.72       0   17.72      .6   17.22
      .6   15.42     3.6   15.42     3.6   17.42     4.1   17.62     6.6   17.32
    10.6   17.32    11.4   17.32    12.1   16.82    12.1   16.12    12.8   16.12
    12.8   16.82    14.8   18.32    15.8   18.52      16   18.32      26   18.32
#Mann= 3 , 0 , 0
   -11.4    .033       0       0    .033       0     4.1    .033       0
#XS Ineff= 2 , 0
               0   17.72     4.1           17.62
Permanent Ineff=
       F       F
Bank Sta=0,4.1
XS Rating Curve= 0
Exp/Cntr=.3,.1

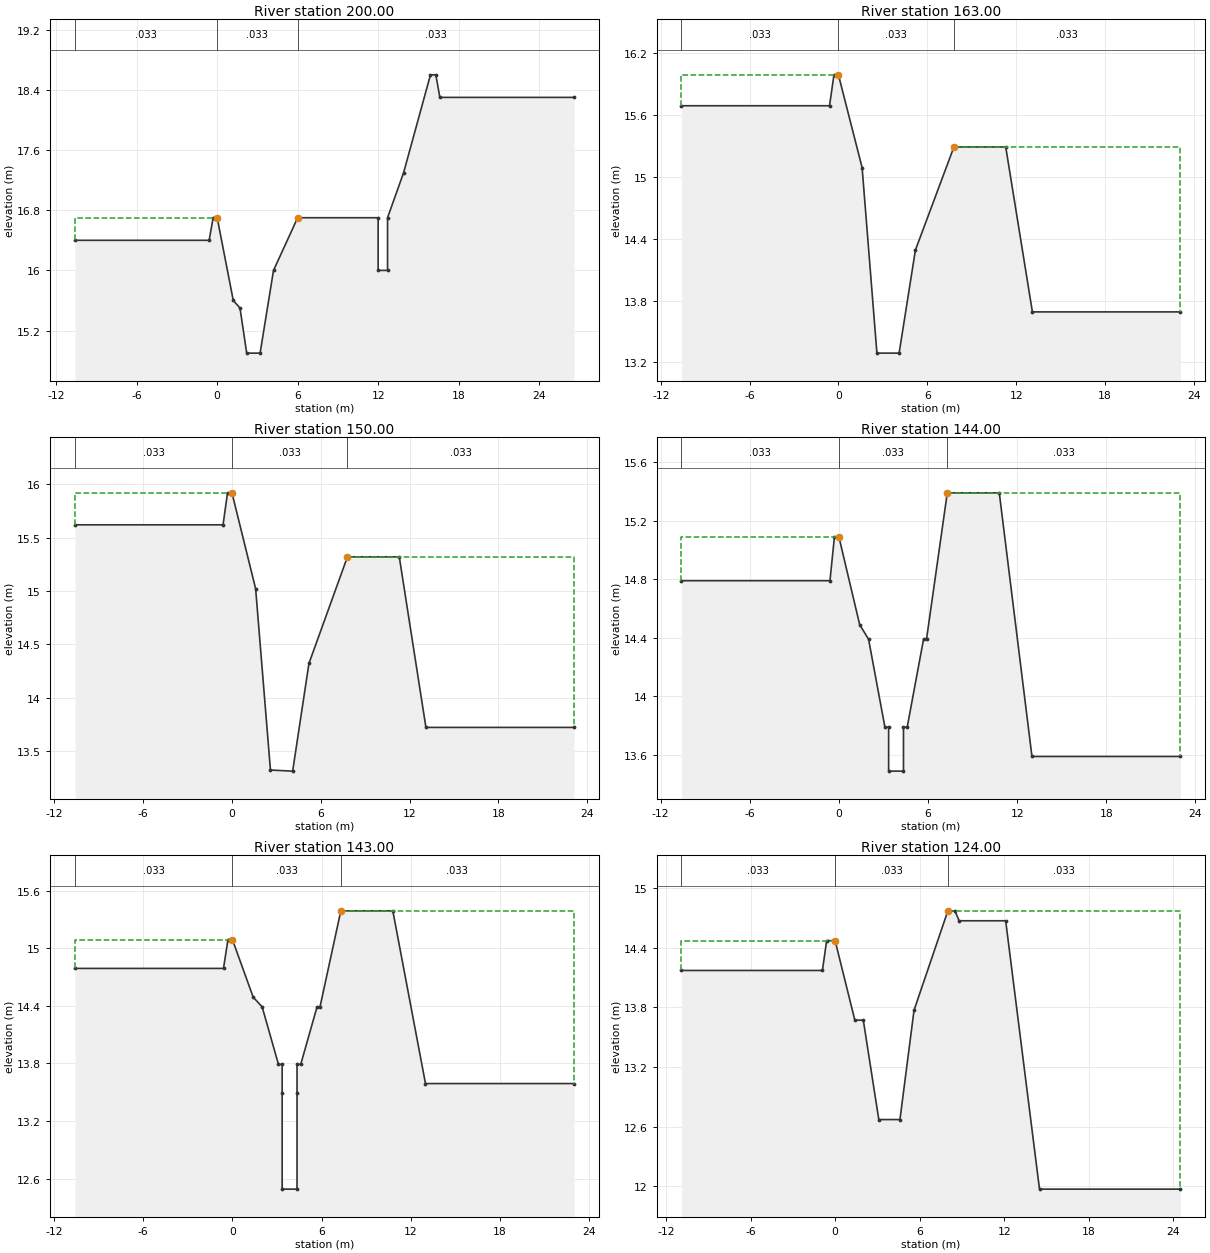
Type RM Length L Ch R = 1 ,200.00  ,37,37,37
BEGIN DESCRIPTION:
4
END DESCRIPTION:
#Sta/Elev= 19
   -10.6    16.4     -.6    16.4     -.3    16.7       0    16.7     1.2    15.6
     1.7    15.5     2.2    14.9     3.2    14.9     4.2      16       6    16.7
      12    16.7      12      16    12.7      16    12.7    16.7    13.9    17.3
    15.9    18.6    16.3    18.6    16.6    18.3    26.6    18.3
#Mann= 3 , 0 , 0
   -10.6    .033       0       0    .033       0       6    .033       0
#XS Ineff= 2 , 0
               0    16.7       6            16.7
Permanent Ineff=
       F       F
Bank Sta=0,6
XS Rating Curve= 0
Exp/Cntr=.3,.1

Type RM Length L Ch R = 1 ,163.00  ,13,13,13
BEGIN DESCRIPTION:
3.013
END DESCRIPTION:
#Sta/Elev= 12
   -10.6   15.69     -.6   15.69     -.3   15.99       0   15.99     1.6   15.09
     2.6   13.29     4.1   13.29     5.2   14.29     7.8   15.29    11.3   15.29
    13.1   13.69    23.1   13.69
#Mann= 3 , 0 , 0
   -10.6    .033       0       0    .033       0     7.8    .033       0
#XS Ineff= 2 , 0
               0   15.99     7.8           15.29
Permanent Ineff=
       F       F
Bank Sta=0,7.8
XS Rating Curve= 0
Exp/Cntr=.3,.1

Type RM Length L Ch R = 1 ,150.00  ,6,6,6
BEGIN DESCRIPTION:
3
END DESCRIPTION:
#Sta/Elev= 12
   -10.6   15.62     -.6   15.62     -.3   15.92       0   15.92     1.6   15.02
     2.6   13.32     4.1   13.31     5.2   14.32     7.8   15.32    11.3   15.32
    13.1   13.72    23.1   13.72
#Mann= 3 , 0 , 0
   -10.6    .033       0       0    .033       0     7.8    .033       0
#XS Ineff= 2 , 0
               0   15.92     7.8           15.32
Permanent Ineff=
       F       F
Bank Sta=0,7.8
XS Rating Curve= 0
Exp/Cntr=.3,.1

Type RM Length L Ch R = 1 ,144.00  ,1,1,1
BEGIN DESCRIPTION:
2.044
END DESCRIPTION:
#Sta/Elev= 18
   -10.6   14.79     -.6   14.79     -.3   15.09       0   15.09     1.4   14.49
       2   14.39     3.1   13.79    3.35   13.79    3.35   13.49    4.35   13.49
    4.35   13.79     4.6   13.79     5.7   14.39     5.9   14.39     7.3   15.39
    10.8   15.39      13   13.59      23   13.59
#Mann= 3 , 0 , 0
   -10.6    .033       0       0    .033       0     7.3    .033       0
#XS Ineff= 2 , 0
               0   15.09     7.3           15.39
Permanent Ineff=
       F       F
Bank Sta=0,7.3
XS Rating Curve= 0
Exp/Cntr=.3,.1

Type RM Length L Ch R = 1 ,143.00  ,19,19,19
BEGIN DESCRIPTION:
2.043
END DESCRIPTION:
#Sta/Elev= 20
   -10.6   14.79     -.6   14.79     -.3   15.09       0   15.09     1.4   14.49
       2   14.39     3.1   13.79    3.35   13.79    3.35   13.49    3.35   12.49
    4.35   12.49    4.35   13.49    4.35   13.79     4.6   13.79     5.7   14.39
     5.9   14.39     7.3   15.39    10.8   15.39      13   13.59      23   13.59
#Mann= 3 , 0 , 0
   -10.6    .033       0       0    .033       0     7.3    .033       0
#XS Ineff= 2 , 0
               0   15.09     7.3           15.39
Permanent Ineff=
       F       F
Bank Sta=0,7.3
XS Rating Curve= 0
Exp/Cntr=.3,.1

Type RM Length L Ch R = 1 ,124.00  ,1,1,1
BEGIN DESCRIPTION:
2.024
END DESCRIPTION:
#Sta/Elev= 15
   -10.9   14.17     -.9   14.17     -.6   14.47       0   14.47     1.4   13.67
       2   13.67     3.1   12.67     4.6   12.67     5.6   13.77       8   14.77
     8.5   14.77     8.8   14.67    12.1   14.67    14.5   11.97    24.5   11.97
#Mann= 3 , 0 , 0
   -10.9    .033       0       0    .033       0       8    .033       0
#XS Ineff= 2 , 0
               0   14.47       8           14.77
Permanent Ineff=
       F       F
Bank Sta=0,8
XS Rating Curve= 0
Exp/Cntr=.3,.1

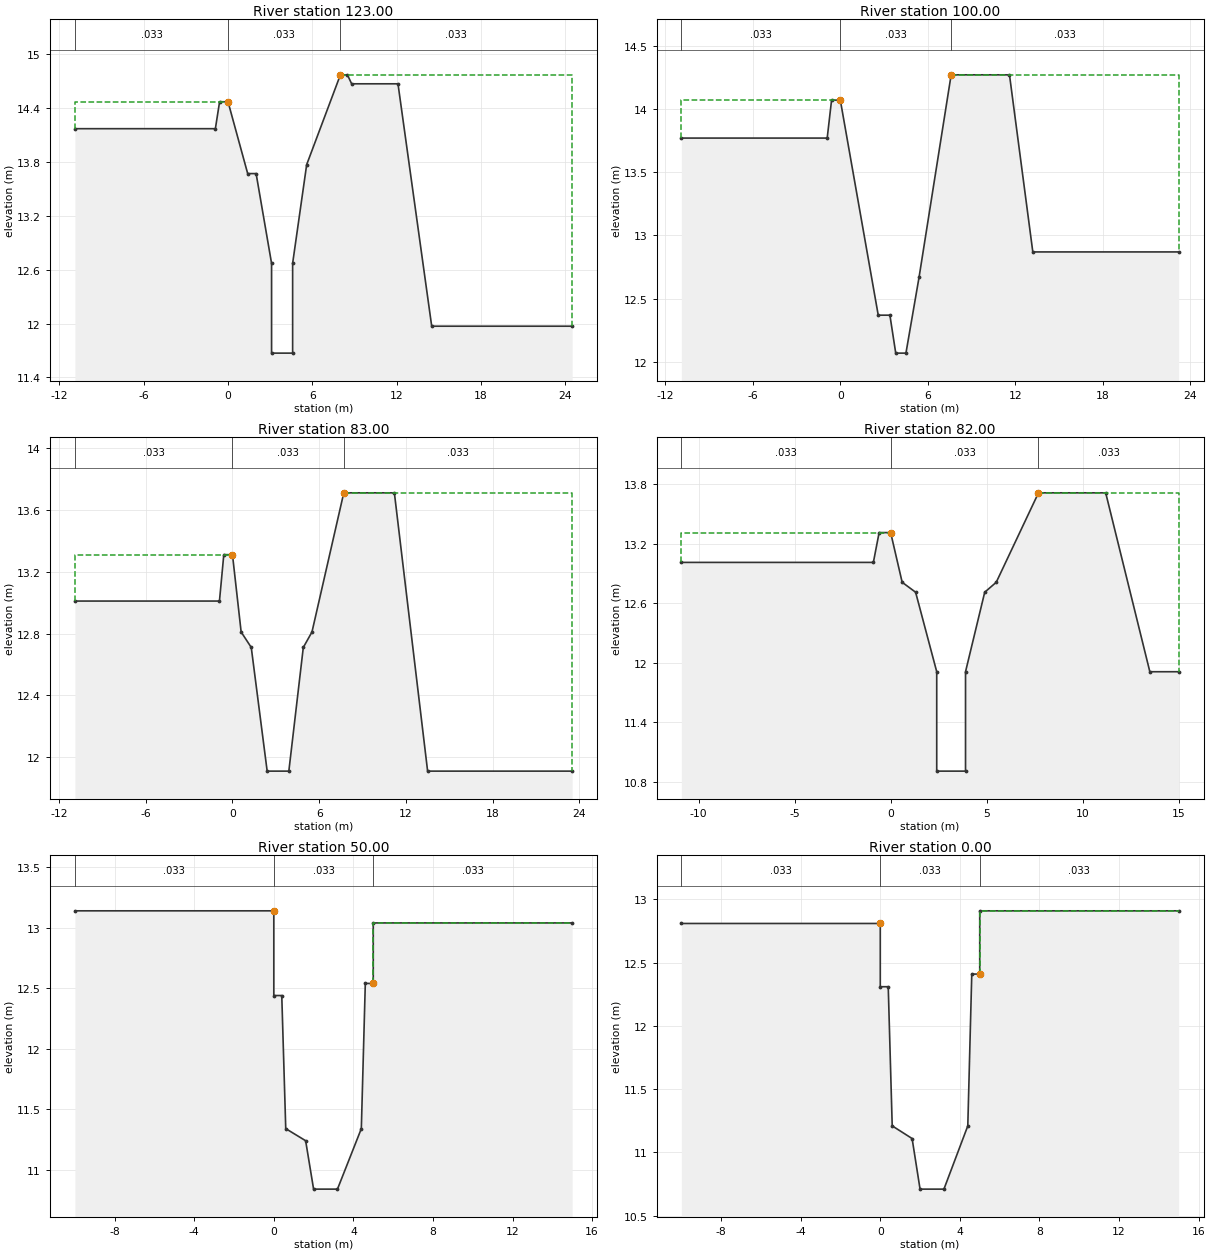
Type RM Length L Ch R = 1 ,123.00  ,23,23,23
BEGIN DESCRIPTION:
2.023
END DESCRIPTION:
#Sta/Elev= 17
   -10.9   14.17     -.9   14.17     -.6   14.47       0   14.47     1.4   13.67
       2   13.67     3.1   12.67     3.1   11.67     4.6   11.67     4.6   12.67
     5.6   13.77       8   14.77     8.5   14.77     8.8   14.67    12.1   14.67
    14.5   11.97    24.5   11.97
#Mann= 3 , 0 , 0
   -10.9    .033       0       0    .033       0       8    .033       0
#XS Ineff= 2 , 0
               0   14.47       8           14.77
Permanent Ineff=
       F       F
Bank Sta=0,8
XS Rating Curve= 0
Exp/Cntr=.3,.1

Type RM Length L Ch R = 1 ,100.00  ,17,17,17
BEGIN DESCRIPTION:
2
END DESCRIPTION:
#Sta/Elev= 13
   -10.9   13.77     -.9   13.77     -.6   14.07       0   14.07     2.6   12.37
     3.4   12.37     3.8   12.07     4.5   12.07     5.4   12.67     7.6   14.27
    11.6   14.27    13.2   12.87    23.2   12.87
#Mann= 3 , 0 , 0
   -10.9    .033       0       0    .033       0     7.6    .033       0
#XS Ineff= 2 , 0
               0   14.07     7.6           14.27
Permanent Ineff=
       F       F
Bank Sta=0,7.6
XS Rating Curve= 0
Exp/Cntr=.3,.1

Type RM Length L Ch R = 1 ,83.00   ,1,1,1
BEGIN DESCRIPTION:
1.033
END DESCRIPTION:
#Sta/Elev= 14
   -10.9   13.01     -.9   13.01     -.6   13.31       0   13.31      .6   12.81
     1.3   12.71     2.4   11.91     3.9   11.91     4.9   12.71     5.5   12.81
     7.7   13.71    11.2   13.71    13.5   11.91    23.5   11.91
#Mann= 3 , 0 , 0
   -10.9    .033       0       0    .033       0     7.7    .033       0
#XS Ineff= 2 , 0
               0   13.31     7.7           13.71
Permanent Ineff=
       F       F
Bank Sta=0,7.7
XS Rating Curve= 0
Exp/Cntr=.3,.1

Type RM Length L Ch R = 1 ,82.00   ,32,32,32
BEGIN DESCRIPTION:
1.032
END DESCRIPTION:
#Sta/Elev= 16
   -10.9   13.01     -.9   13.01     -.6   13.31       0   13.31      .6   12.81
     1.3   12.71     2.4   11.91     2.4   10.91     3.9   10.91     3.9   11.91
     4.9   12.71     5.5   12.81     7.7   13.71    11.2   13.71    13.5   11.91
      15   11.91
#Mann= 3 , 0 , 0
   -10.9    .033       0       0    .033       0     7.7    .033       0
#XS Ineff= 2 , 0
               0   13.31     7.7           13.71
Permanent Ineff=
       F       F
Bank Sta=0,7.7
XS Rating Curve= 0
Exp/Cntr=.3,.1

Type RM Length L Ch R = 1 ,50.00   ,50,50,50
BEGIN DESCRIPTION:
1
END DESCRIPTION:
#Sta/Elev= 13
     -10   13.14       0   13.14       0   12.44      .4   12.44      .6   11.34
     1.6   11.24       2   10.84     3.2   10.84     4.4   11.34     4.6   12.54
       5   12.54       5   13.04      15   13.04
#Mann= 3 , 0 , 0
     -10    .033       0       0    .033       0       5    .033       0
#XS Ineff= 2 , 0
               0   13.14       5           13.04
Permanent Ineff=
       F       F
Bank Sta=0,5
XS Rating Curve= 0
Exp/Cntr=.3,.1

Type RM Length L Ch R = 1 ,0.00    ,0,0,0
BEGIN DESCRIPTION:
0
END DESCRIPTION:
#Sta/Elev= 13
     -10   12.81       0   12.81       0   12.31      .4   12.31      .6   11.21
     1.6   11.11       2   10.71     3.2   10.71     4.4   11.21     4.6   12.41
       5   12.41       5   12.91      15   12.91
#Mann= 3 , 0 , 0
     -10    .033       0       0    .033       0       5    .033       0
#XS Ineff= 2 , 0
               0   12.81       5           12.91
Permanent Ineff=
       F       F
Bank Sta=0,5
XS Rating Curve= 0
Exp/Cntr=.3,.1

Chan Stop Cuts=-1