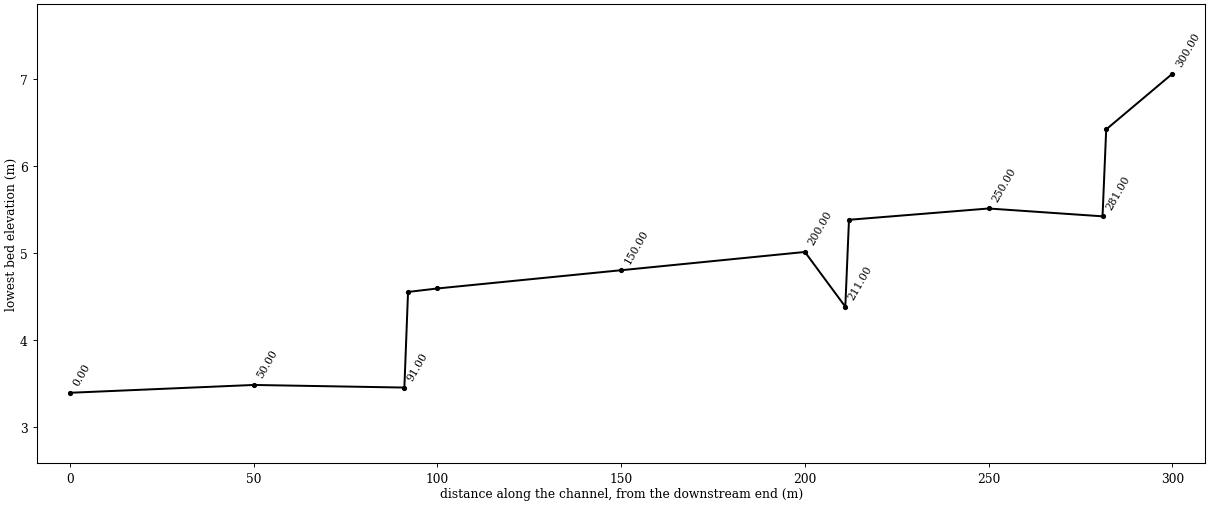
HEC-RAS study SR.prj: SIRU

--- SR.g01 (geometry) --- (continued)

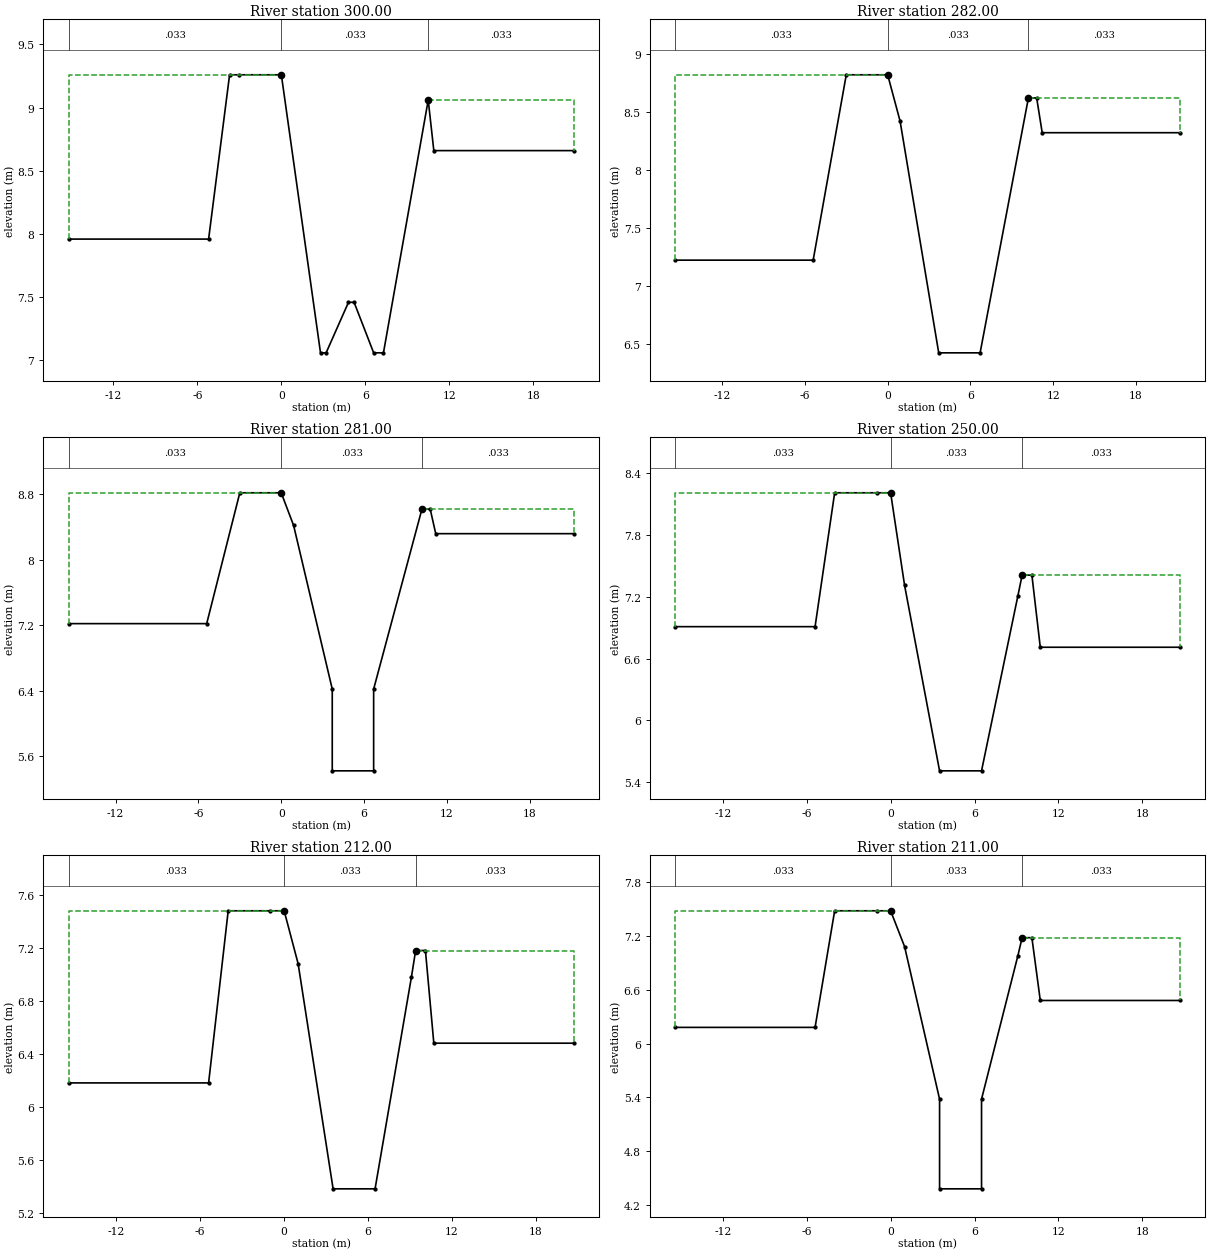
Type RM Length L Ch R = 1 ,300.00  ,18,18,18
BEGIN DESCRIPTION:
6
END DESCRIPTION:
#Sta/Elev= 14
   -15.2    7.96    -5.2    7.96    -3.7    9.26      -3    9.26       0    9.26
     2.8    7.06     3.2    7.06     4.8    7.46     5.2    7.46     6.6    7.06
     7.3    7.06    10.5    9.06    10.9    8.66    20.9    8.66
#Mann= 3 , 0 , 0
   -15.2    .033       0       0    .033       0    10.5    .033       0
#XS Ineff= 2 , 0
               0    9.26    10.5            9.06
Permanent Ineff=
       F       F
Bank Sta=0,10.5
XS Rating Curve= 0
Exp/Cntr=.3,.1

Type RM Length L Ch R = 1 ,282.00  ,1,1,1
BEGIN DESCRIPTION:
5.032
END DESCRIPTION:
#Sta/Elev= 11
   -15.4    7.22    -5.4    7.22      -3    8.82       0    8.82      .9    8.42
     3.7    6.42     6.7    6.42    10.2    8.62    10.8    8.62    11.2    8.32
    21.2    8.32
#Mann= 3 , 0 , 0
   -15.4    .033       0       0    .033       0    10.2    .033       0
#XS Ineff= 2 , 0
               0    8.82    10.2            8.62
Permanent Ineff=
       F       F
Bank Sta=0,10.2
XS Rating Curve= 0
Exp/Cntr=.3,.1

Type RM Length L Ch R = 1 ,281.00  ,31,31,31
BEGIN DESCRIPTION:
5.031
END DESCRIPTION:
#Sta/Elev= 13
   -15.4    7.22    -5.4    7.22      -3    8.82       0    8.82      .9    8.42
     3.7    6.42     3.7    5.42     6.7    5.42     6.7    6.42    10.2    8.62
    10.8    8.62    11.2    8.32    21.2    8.32
#Mann= 3 , 0 , 0
   -15.4    .033       0       0    .033       0    10.2    .033       0
#XS Ineff= 2 , 0
               0    8.82    10.2            8.62
Permanent Ineff=
       F       F
Bank Sta=0,10.2
XS Rating Curve= 0
Exp/Cntr=.3,.1

Type RM Length L Ch R = 1 ,250.00  ,38,38,38
BEGIN DESCRIPTION:
5
END DESCRIPTION:
#Sta/Elev= 13
   -15.4    6.91    -5.4    6.91      -4    8.21      -1    8.21       0    8.21
       1    7.31     3.5    5.51     6.5    5.51     9.1    7.21     9.4    7.41
    10.1    7.41    10.7    6.71    20.7    6.71
#Mann= 3 , 0 , 0
   -15.4    .033       0       0    .033       0     9.4    .033       0
#XS Ineff= 2 , 0
               0    8.21     9.4            7.41
Permanent Ineff=
       F       F
Bank Sta=0,9.4
XS Rating Curve= 0
Exp/Cntr=.3,.1

Type RM Length L Ch R = 1 ,212.00  ,1,1,1
BEGIN DESCRIPTION:
4.012
END DESCRIPTION:
#Sta/Elev= 13
   -15.4    6.18    -5.4    6.18      -4    7.48      -1    7.48       0    7.48
       1    7.08     3.5    5.38     6.5    5.38     9.1    6.98     9.4    7.18
    10.1    7.18    10.7    6.48    20.7    6.48
#Mann= 3 , 0 , 0
   -15.4    .033       0       0    .033       0     9.4    .033       0
#XS Ineff= 2 , 0
               0    7.48     9.4            7.18
Permanent Ineff=
       F       F
Bank Sta=0,9.4
XS Rating Curve= 0
Exp/Cntr=.3,.1

Type RM Length L Ch R = 1 ,211.00  ,11,11,11
BEGIN DESCRIPTION:
4.011
END DESCRIPTION:
#Sta/Elev= 15
   -15.4    6.18    -5.4    6.18      -4    7.48      -1    7.48       0    7.48
       1    7.08     3.5    5.38     3.5    4.38     6.5    4.38     6.5    5.38
     9.1    6.98     9.4    7.18    10.1    7.18    10.7    6.48    20.7    6.48
#Mann= 3 , 0 , 0
   -15.4    .033       0       0    .033       0     9.4    .033       0
#XS Ineff= 2 , 0
               0    7.48     9.4            7.18
Permanent Ineff=
       F       F
Bank Sta=0,9.4
XS Rating Curve= 0
Exp/Cntr=.3,.1

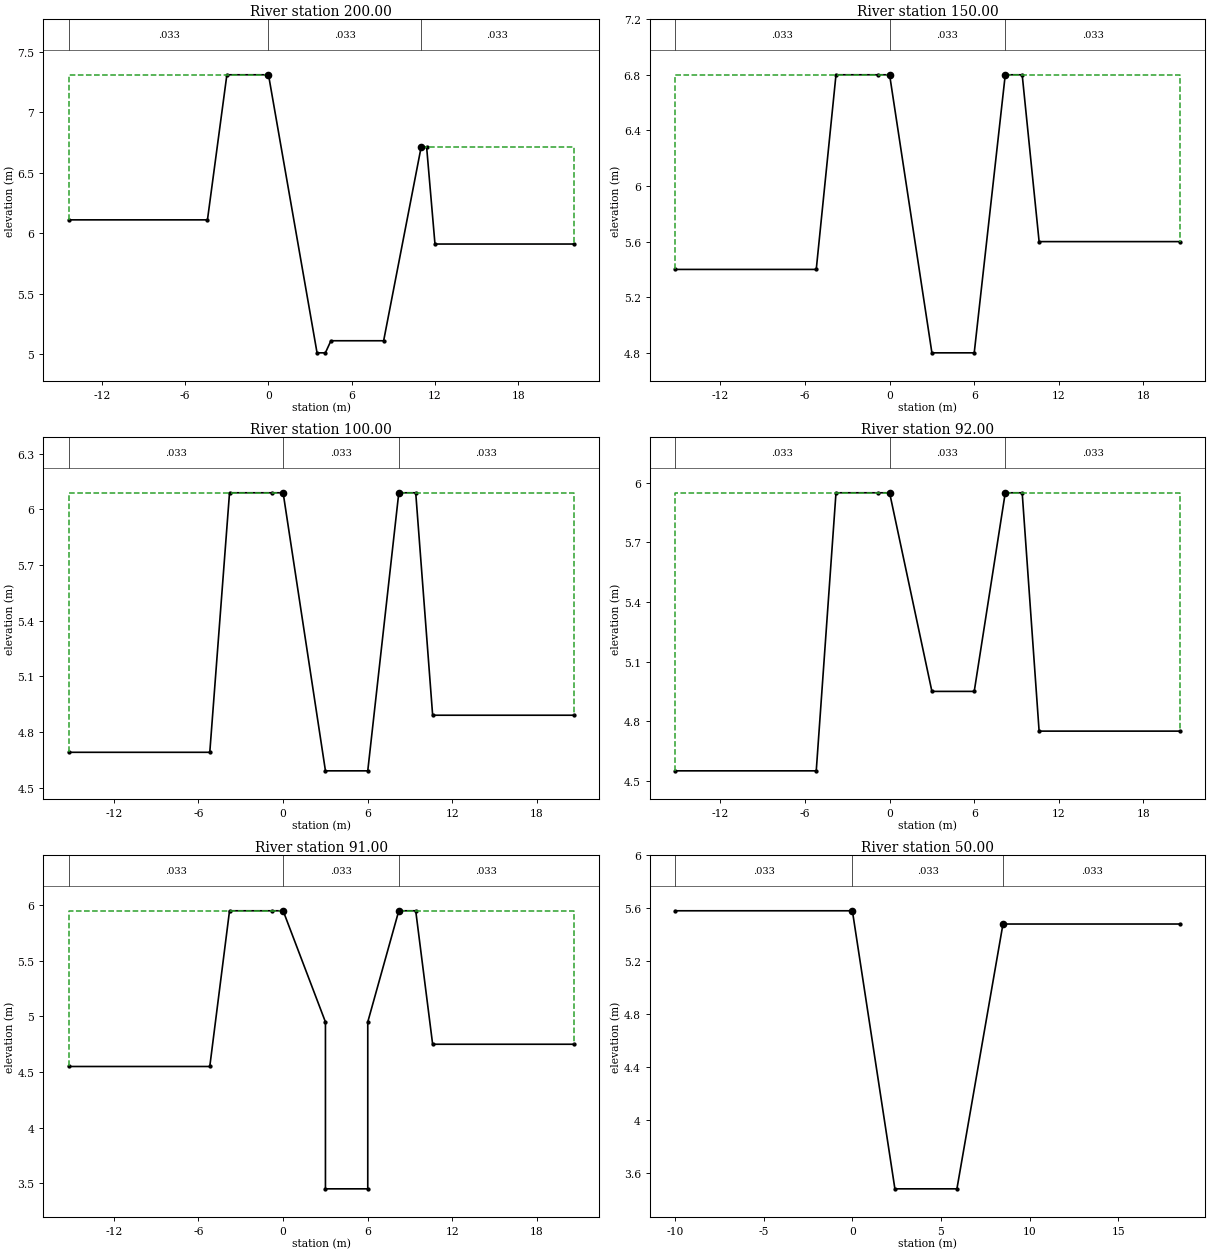
Type RM Length L Ch R = 1 ,200.00  ,50,50,50
BEGIN DESCRIPTION:
4
END DESCRIPTION:
#Sta/Elev= 12
   -14.4    6.11    -4.4    6.11      -3    7.31       0    7.31     3.5    5.01
     4.1    5.01     4.5    5.11     8.3    5.11      11    6.71    11.4    6.71
      12    5.91      22    5.91
#Mann= 3 , 0 , 0
   -14.4    .033       0       0    .033       0      11    .033       0
#XS Ineff= 2 , 0
               0    7.31      11            6.71
Permanent Ineff=
       F       F
Bank Sta=0,11
XS Rating Curve= 0
Exp/Cntr=.3,.1

Type RM Length L Ch R = 1 ,150.00  ,50,50,50
BEGIN DESCRIPTION:
3
END DESCRIPTION:
#Sta/Elev= 11
   -15.2     5.4    -5.2     5.4    -3.8     6.8     -.8     6.8       0     6.8
       3     4.8       6     4.8     8.2     6.8     9.4     6.8    10.6     5.6
    20.6     5.6
#Mann= 3 , 0 , 0
   -15.2    .033       0       0    .033       0     8.2    .033       0
#XS Ineff= 2 , 0
               0     6.8     8.2             6.8
Permanent Ineff=
       F       F
Bank Sta=0,8.2
XS Rating Curve= 0
Exp/Cntr=.3,.1

Type RM Length L Ch R = 1 ,100.00  ,8,8,8
BEGIN DESCRIPTION:
2
END DESCRIPTION:
#Sta/Elev= 11
   -15.2    4.69    -5.2    4.69    -3.8    6.09     -.8    6.09       0    6.09
       3    4.59       6    4.59     8.2    6.09     9.4    6.09    10.6    4.89
    20.6    4.89
#Mann= 3 , 0 , 0
   -15.2    .033       0       0    .033       0     8.2    .033       0
#XS Ineff= 2 , 0
               0    6.09     8.2            6.09
Permanent Ineff=
       F       F
Bank Sta=0,8.2
XS Rating Curve= 0
Exp/Cntr=.3,.1

Type RM Length L Ch R = 1 ,92.00   ,1,1,1
BEGIN DESCRIPTION:
1.042
END DESCRIPTION:
#Sta/Elev= 11
   -15.2    4.55    -5.2    4.55    -3.8    5.95     -.8    5.95       0    5.95
       3    4.95       6    4.95     8.2    5.95     9.4    5.95    10.6    4.75
    20.6    4.75
#Mann= 3 , 0 , 0
   -15.2    .033       0       0    .033       0     8.2    .033       0
#XS Ineff= 2 , 0
               0    5.95     8.2            5.95
Permanent Ineff=
       F       F
Bank Sta=0,8.2
XS Rating Curve= 0
Exp/Cntr=.3,.1

Type RM Length L Ch R = 1 ,91.00   ,41,41,41
BEGIN DESCRIPTION:
1.041
END DESCRIPTION:
#Sta/Elev= 13
   -15.2    4.55    -5.2    4.55    -3.8    5.95     -.8    5.95       0    5.95
       3    4.95       3    3.45       6    3.45       6    4.95     8.2    5.95
     9.4    5.95    10.6    4.75    20.6    4.75
#Mann= 3 , 0 , 0
   -15.2    .033       0       0    .033       0     8.2    .033       0
#XS Ineff= 2 , 0
               0    5.95     8.2            5.95
Permanent Ineff=
       F       F
Bank Sta=0,8.2
XS Rating Curve= 0
Exp/Cntr=.3,.1

Type RM Length L Ch R = 1 ,50.00   ,50,50,50
BEGIN DESCRIPTION:
1
END DESCRIPTION:
#Sta/Elev= 6
     -10    5.58       0    5.58     2.4    3.48     5.9    3.48     8.5    5.48
    18.5    5.48
#Mann= 3 , 0 , 0
     -10    .033       0       0    .033       0     8.5    .033       0
#XS Ineff= 2 , 0
               0    5.58     8.5            5.48
Permanent Ineff=
       F       F
Bank Sta=0,8.5
XS Rating Curve= 0
Exp/Cntr=.3,.1

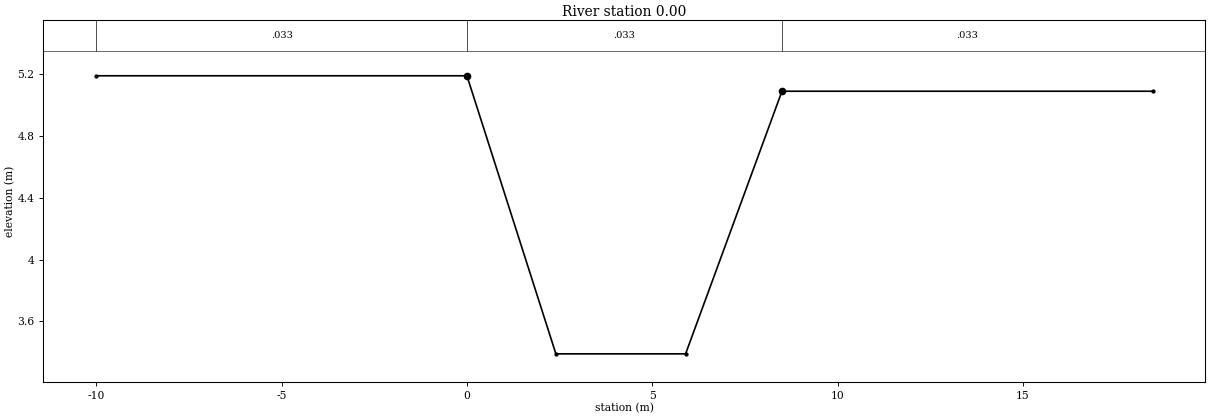
Type RM Length L Ch R = 1 ,0.00    ,0,0,0
BEGIN DESCRIPTION:
0
END DESCRIPTION:
#Sta/Elev= 6
     -10    5.19       0    5.19     2.4    3.39     5.9    3.39     8.5    5.09
    18.5    5.09
#Mann= 3 , 0 , 0
     -10    .033       0       0    .033       0     8.5    .033       0
#XS Ineff= 2 , 0
               0    5.19     8.5            5.09
Permanent Ineff=
       F       F
Bank Sta=0,8.5
XS Rating Curve= 0
Exp/Cntr=.3,.1

Chan Stop Cuts=-1