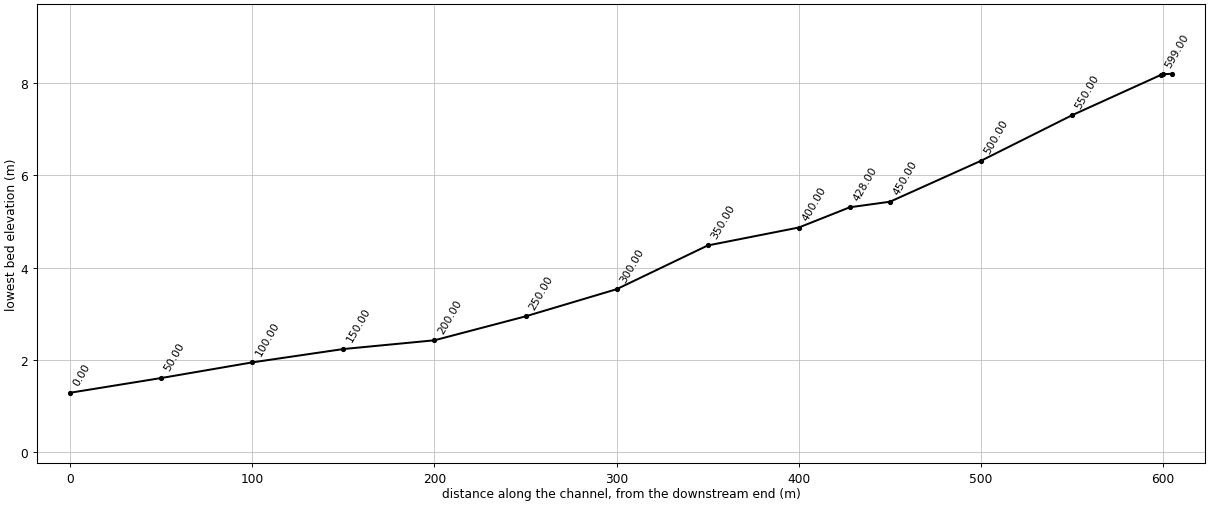
--- BANG.prj (project) ---

Proj Title=BANG
Current Plan=p01
Default Exp/Contr=.3,.1
SI Units
Geom File=g01
Flow File=f01
Plan File=p01
Y Axis Title=Elevation
X Axis Title(PF)=Main Channel Distance
X Axis Title(XS)=Station
BEGIN DESCRIPTION:
           BACK WATER COMPUTATION
      APPLICATION OF HEC-2 BY Samju Construction Engineering
      BANGJUKKOL-STREEM : 30 YR
END DESCRIPTION:
DSS Export Rating Curves= 0
DSS Export Rating Curve Sorted= 0
DSS Export Volume Flow Curves= 0
DXF OffsetX= 0
DXF OffsetY= 0
DXF ScaleX= 1
DXF ScaleY= 10

--- BANG.p01 (plan) ---

Plan Title=Imported Plan 01
Version=Version 3.0.1  Mar 2001
Short Identifier=Imported Pla
Geom File=g01
Flow File=f01
Subcritical Flow
K Sum by GR= 0
Std Step Tol= 0.003
Critical Tol= 0.003
Num of Std Step Trials= 20
Max Error Tol= 0.1
Flow Tol Ratio= 0.001
Split Flow NTrial= 30
Split Flow Tol= 0.02
Split Flow Ratio= 0.02
Log Output Level= 0
Friction Slope Method= 1
Unsteady Friction Slope Method= 2
Parabolic Critical Depth
Global Vel Dist= 0 , 0 , 0
Global Log Level= 0
CheckData=True
Encroach Param=-1 ,0,0, 0
Computation Interval=1HOUR
Output Interval=1HOUR
Run HTab= 0
Run UNet= 0
Run PostProcess= 0
UNET Theta= 1
UNET ZTol= 0.02
UNET ZSATol= 0.1
UNET MxIter= 20
UNET MaxInSteps= 20
UNET DtIC= 0
UNET DtMin= 0
UNET MaxCRTS= 20
UNET WFStab= 2
UNET SFStab= 1
UNET WFX= 1
UNET SFX= 1
UNET Convert EG Bridges=-1
UNET Use Existing IB Tables=-1
Instantaneous Interval=1HOUR
Write IC File= 0
Write Velocity= 0
Write Detailed= 0

--- BANG.f01 (steady flow) ---

Flow Title=Imported Flow 01
Version=Version 3.0.1  Mar 2001
Number of Profiles= 5
Profile Names=10YR,20YR,30YR,50YR,80YR
River Rch & RM=RIVER-1,Reach-1         ,605.00
   11.84   13.04   13.74   14.62   15.43
Boundary for River Rch & Prof#=RIVER-1,Reach-1         , 1
Up Type= 0
Dn Type= 3
Dn Slope=.03
Boundary for River Rch & Prof#=RIVER-1,Reach-1         , 2
Up Type= 0
Dn Type= 3
Dn Slope=.03
Boundary for River Rch & Prof#=RIVER-1,Reach-1         , 3
Up Type= 0
Dn Type= 3
Dn Slope=.03
Boundary for River Rch & Prof#=RIVER-1,Reach-1         , 4
Up Type= 0
Dn Type= 3
Dn Slope=.03
Boundary for River Rch & Prof#=RIVER-1,Reach-1         , 5
Up Type= 0
Dn Type= 3
Dn Slope=.03
DSS Import GetInterval= 0
DSS Import GetPeak= 0
DSS Import FillOption= 0

--- BANG.g01 (geometry) ---

Geom Title=Imported Geom 01
Version=Version 3.0.1  Mar 2001

River Reach=RIVER-1         ,Reach-1
Reach XY= 2
              .5             .95              .5             .05

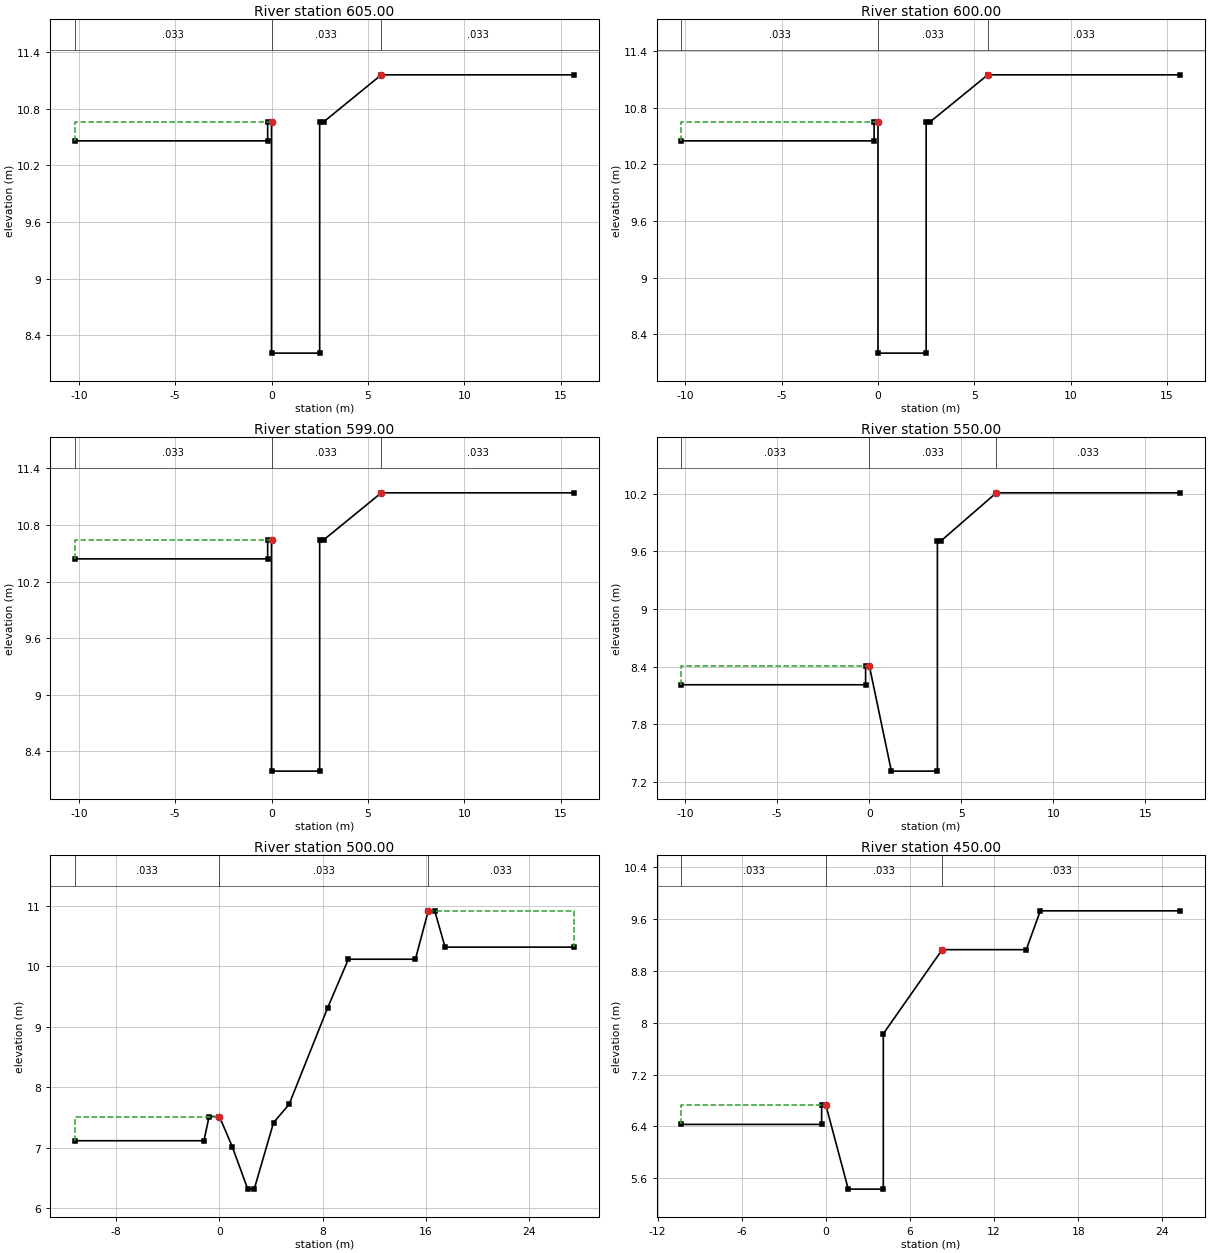
Type RM Length L Ch R = 1 ,605.00  ,5,5,5
BEGIN DESCRIPTION:
12.005
END DESCRIPTION:
#Sta/Elev= 10
   -10.2   10.46     -.2   10.46     -.2   10.66       0   10.66       0    8.21
     2.5    8.21     2.5   10.66     2.7   10.66     5.7   11.16    15.7   11.16
#Mann= 3 , 0 , 0
   -10.2    .033       0       0    .033       0     5.7    .033       0
#XS Ineff= 2 , 0
               0   10.66     5.7           11.16
Permanent Ineff=
       F       F
Bank Sta=0,5.7
XS Rating Curve= 0
Exp/Cntr=.3,.1

Type RM Length L Ch R = 1 ,600.00  ,1,1,1
BEGIN DESCRIPTION:
12
END DESCRIPTION:
#Sta/Elev= 10
   -10.2   10.45     -.2   10.45     -.2   10.65       0   10.65       0     8.2
     2.5     8.2     2.5   10.65     2.7   10.65     5.7   11.15    15.7   11.15
#Mann= 3 , 0 , 0
   -10.2    .033       0       0    .033       0     5.7    .033       0
#XS Ineff= 2 , 0
               0   10.65     5.7           11.15
Permanent Ineff=
       F       F
Bank Sta=0,5.7
XS Rating Curve= 0
Exp/Cntr=.3,.1

Type RM Length L Ch R = 1 ,599.00  ,49,49,49
BEGIN DESCRIPTION:
11.049
END DESCRIPTION:
#Sta/Elev= 10
   -10.2   10.44     -.2   10.44     -.2   10.64       0   10.64       0    8.19
     2.5    8.19     2.5   10.64     2.7   10.64     5.7   11.14    15.7   11.14
#Mann= 3 , 0 , 0
   -10.2    .033       0       0    .033       0     5.7    .033       0
#XS Ineff= 2 , 0
               0   10.64     5.7           11.14
Permanent Ineff=
       F       F
Bank Sta=0,5.7
XS Rating Curve= 0
Exp/Cntr=.3,.1

Type RM Length L Ch R = 1 ,550.00  ,50,50,50
BEGIN DESCRIPTION:
11
END DESCRIPTION:
#Sta/Elev= 10
   -10.2    8.21     -.2    8.21     -.2    8.41       0    8.41     1.2    7.31
     3.7    7.31     3.7    9.71     3.9    9.71     6.9   10.21    16.9   10.21
#Mann= 3 , 0 , 0
   -10.2    .033       0       0    .033       0     6.9    .033       0
#XS Ineff= 2 , 0
               0    8.41     6.9           10.21
Permanent Ineff=
       F       F
Bank Sta=0,6.9
XS Rating Curve= 0
Exp/Cntr=.3,.1

Type RM Length L Ch R = 1 ,500.00  ,50,50,50
BEGIN DESCRIPTION:
10
END DESCRIPTION:
#Sta/Elev= 16
   -11.2    7.12    -1.2    7.12     -.8    7.52       0    7.52       1    7.02
     2.2    6.32     2.7    6.32     4.2    7.42     5.4    7.72     8.4    9.32
      10   10.12    15.2   10.12    16.2   10.92    16.7   10.92    17.5   10.32
    27.5   10.32
#Mann= 3 , 0 , 0
   -11.2    .033       0       0    .033       0    16.2    .033       0
#XS Ineff= 2 , 0
               0    7.52    16.2           10.92
Permanent Ineff=
       F       F
Bank Sta=0,16.2
XS Rating Curve= 0
Exp/Cntr=.3,.1

Type RM Length L Ch R = 1 ,450.00  ,22,22,22
BEGIN DESCRIPTION:
9
END DESCRIPTION:
#Sta/Elev= 11
   -10.3    6.43     -.3    6.43     -.3    6.73       0    6.73     1.6    5.43
     4.1    5.43     4.1    7.83     8.3    9.13    14.3    9.13    15.3    9.73
    25.3    9.73
#Mann= 3 , 0 , 0
   -10.3    .033       0       0    .033       0     8.3    .033       0
#XS Ineff= 2 , 0
               0    6.73     8.3            9.13
Permanent Ineff=
       F       F
Bank Sta=0,8.3
XS Rating Curve= 0
Exp/Cntr=.3,.1

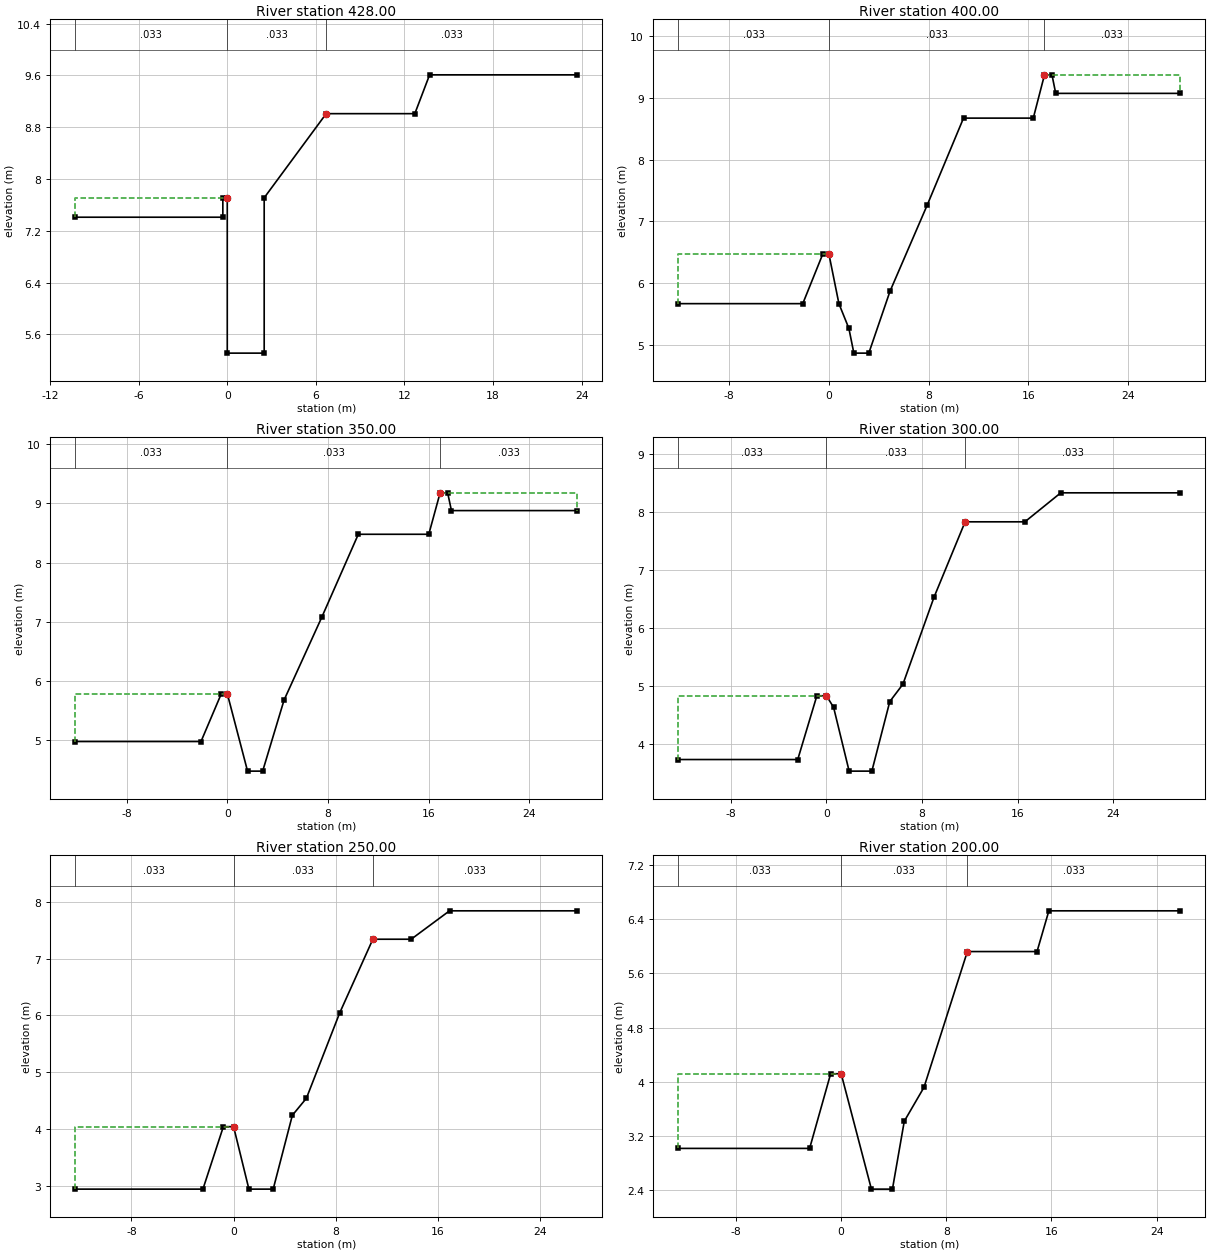
Type RM Length L Ch R = 1 ,428.00  ,28,28,28
BEGIN DESCRIPTION:
8.028
END DESCRIPTION:
#Sta/Elev= 11
   -10.3    7.41     -.3    7.41     -.3    7.71       0    7.71       0    5.31
     2.5    5.31     2.5    7.71     6.7    9.01    12.7    9.01    13.7    9.61
    23.7    9.61
#Mann= 3 , 0 , 0
   -10.3    .033       0       0    .033       0     6.7    .033       0
#XS Ineff= 2 , 0
               0    7.71     6.7            9.01
Permanent Ineff=
       F       F
Bank Sta=0,6.7
XS Rating Curve= 0
Exp/Cntr=.3,.1

Type RM Length L Ch R = 1 ,400.00  ,50,50,50
BEGIN DESCRIPTION:
8
END DESCRIPTION:
#Sta/Elev= 16
   -12.1    5.67    -2.1    5.67     -.5    6.47       0    6.47      .8    5.67
     1.6    5.27       2    4.87     3.2    4.87     4.9    5.87     7.9    7.27
    10.8    8.67    16.4    8.67    17.3    9.37    17.9    9.37    18.2    9.07
    28.2    9.07
#Mann= 3 , 0 , 0
   -12.1    .033       0       0    .033       0    17.3    .033       0
#XS Ineff= 2 , 0
               0    6.47    17.3            9.37
Permanent Ineff=
       F       F
Bank Sta=0,17.3
XS Rating Curve= 0
Exp/Cntr=.3,.1

Type RM Length L Ch R = 1 ,350.00  ,50,50,50
BEGIN DESCRIPTION:
7
END DESCRIPTION:
#Sta/Elev= 14
   -12.1    4.98    -2.1    4.98     -.5    5.78       0    5.78     1.6    4.48
     2.8    4.48     4.5    5.68     7.5    7.08    10.4    8.48      16    8.48
    16.9    9.18    17.5    9.18    17.8    8.88    27.8    8.88
#Mann= 3 , 0 , 0
   -12.1    .033       0       0    .033       0    16.9    .033       0
#XS Ineff= 2 , 0
               0    5.78    16.9            9.18
Permanent Ineff=
       F       F
Bank Sta=0,16.9
XS Rating Curve= 0
Exp/Cntr=.3,.1

Type RM Length L Ch R = 1 ,300.00  ,50,50,50
BEGIN DESCRIPTION:
6
END DESCRIPTION:
#Sta/Elev= 14
   -12.4    3.73    -2.4    3.73     -.8    4.83       0    4.83      .6    4.63
     1.9    3.53     3.8    3.53     5.3    4.73     6.4    5.03       9    6.53
    11.6    7.83    16.6    7.83    19.6    8.33    29.6    8.33
#Mann= 3 , 0 , 0
   -12.4    .033       0       0    .033       0    11.6    .033       0
#XS Ineff= 2 , 0
               0    4.83    11.6            7.83
Permanent Ineff=
       F       F
Bank Sta=0,11.6
XS Rating Curve= 0
Exp/Cntr=.3,.1

Type RM Length L Ch R = 1 ,250.00  ,50,50,50
BEGIN DESCRIPTION:
5
END DESCRIPTION:
#Sta/Elev= 13
   -12.4    2.94    -2.4    2.94     -.8    4.04       0    4.04     1.2    2.94
     3.1    2.94     4.6    4.24     5.7    4.54     8.3    6.04    10.9    7.34
    13.9    7.34    16.9    7.84    26.9    7.84
#Mann= 3 , 0 , 0
   -12.4    .033       0       0    .033       0    10.9    .033       0
#XS Ineff= 2 , 0
               0    4.04    10.9            7.34
Permanent Ineff=
       F       F
Bank Sta=0,10.9
XS Rating Curve= 0
Exp/Cntr=.3,.1

Type RM Length L Ch R = 1 ,200.00  ,50,50,50
BEGIN DESCRIPTION:
4
END DESCRIPTION:
#Sta/Elev= 12
   -12.4    3.02    -2.4    3.02     -.8    4.12       0    4.12     2.3    2.42
     3.9    2.42     4.8    3.42     6.3    3.92     9.6    5.92    14.9    5.92
    15.8    6.52    25.8    6.52
#Mann= 3 , 0 , 0
   -12.4    .033       0       0    .033       0     9.6    .033       0
#XS Ineff= 2 , 0
               0    4.12     9.6            5.92
Permanent Ineff=
       F       F
Bank Sta=0,9.6
XS Rating Curve= 0
Exp/Cntr=.3,.1

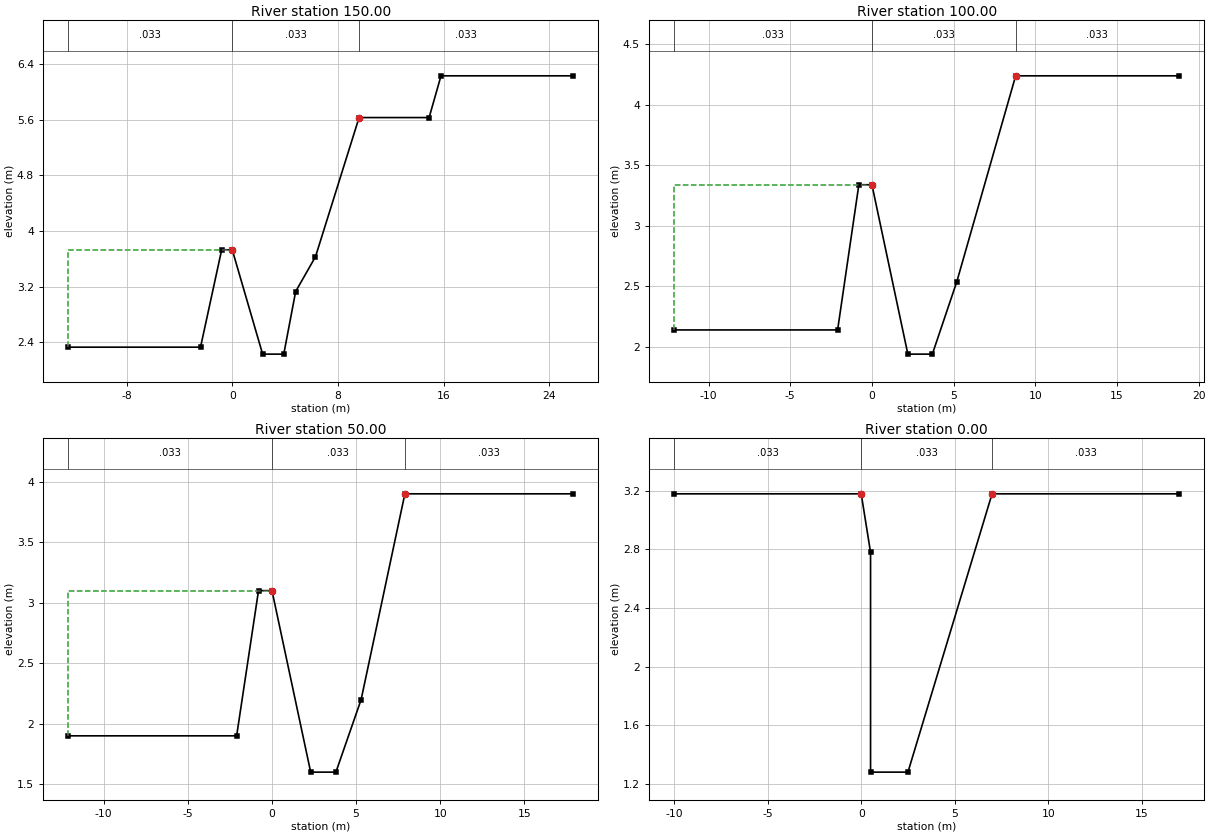
Type RM Length L Ch R = 1 ,150.00  ,50,50,50
BEGIN DESCRIPTION:
3
END DESCRIPTION:
#Sta/Elev= 12
   -12.4    2.33    -2.4    2.33     -.8    3.73       0    3.73     2.3    2.23
     3.9    2.23     4.8    3.13     6.3    3.63     9.6    5.63    14.9    5.63
    15.8    6.23    25.8    6.23
#Mann= 3 , 0 , 0
   -12.4    .033       0       0    .033       0     9.6    .033       0
#XS Ineff= 2 , 0
               0    3.73     9.6            5.63
Permanent Ineff=
       F       F
Bank Sta=0,9.6
XS Rating Curve= 0
Exp/Cntr=.3,.1

Type RM Length L Ch R = 1 ,100.00  ,50,50,50
BEGIN DESCRIPTION:
2
END DESCRIPTION:
#Sta/Elev= 9
   -12.1    2.14    -2.1    2.14     -.8    3.34       0    3.34     2.2    1.94
     3.7    1.94     5.2    2.54     8.8    4.24    18.8    4.24
#Mann= 3 , 0 , 0
   -12.1    .033       0       0    .033       0     8.8    .033       0
#XS Ineff= 2 , 0
               0    3.34     8.8            4.24
Permanent Ineff=
       F       F
Bank Sta=0,8.8
XS Rating Curve= 0
Exp/Cntr=.3,.1

Type RM Length L Ch R = 1 ,50.00   ,50,50,50
BEGIN DESCRIPTION:
1
END DESCRIPTION:
#Sta/Elev= 9
   -12.1     1.9    -2.1     1.9     -.8     3.1       0     3.1     2.3     1.6
     3.8     1.6     5.3     2.2     7.9     3.9    17.9     3.9
#Mann= 3 , 0 , 0
   -12.1    .033       0       0    .033       0     7.9    .033       0
#XS Ineff= 2 , 0
               0     3.1     7.9             3.9
Permanent Ineff=
       F       F
Bank Sta=0,7.9
XS Rating Curve= 0
Exp/Cntr=.3,.1

Type RM Length L Ch R = 1 ,0.00    ,0,0,0
BEGIN DESCRIPTION:
0
END DESCRIPTION:
#Sta/Elev= 7
     -10    3.18       0    3.18      .5    2.78      .5    1.28     2.5    1.28
       7    3.18      17    3.18
#Mann= 3 , 0 , 0
     -10    .033       0       0    .033       0       7    .033       0
#XS Ineff= 2 , 0
               0    3.18       7            3.18
Permanent Ineff=
       F       F
Bank Sta=0,7
XS Rating Curve= 0
Exp/Cntr=.3,.1

Chan Stop Cuts=-1