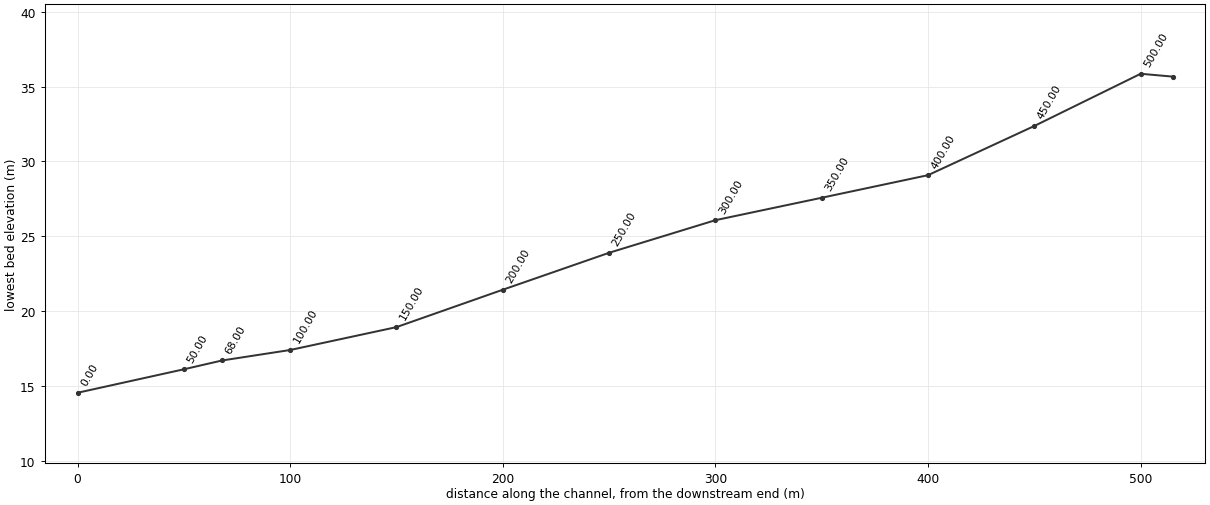
--- SONG.prj (project) ---

Proj Title=SONG
Current Plan=p01
Default Exp/Contr=.3,.1
SI Units
Geom File=g01
Flow File=f01
Plan File=p01
Y Axis Title=Elevation
X Axis Title(PF)=Main Channel Distance
X Axis Title(XS)=Station
BEGIN DESCRIPTION:
           BACK WATER COMPUTATION
      APPLICATION OF HEC-2 BY Samju Construction Engineering
      SONGRIM-STREEM : 30 YR
END DESCRIPTION:
DSS Export Rating Curves= 0
DSS Export Rating Curve Sorted= 0
DSS Export Volume Flow Curves= 0
DXF OffsetX= 0
DXF OffsetY= 0
DXF ScaleX= 1
DXF ScaleY= 10

--- SONG.p01 (plan) ---

Plan Title=Imported Plan 01
Version=Version 3.0.1  Mar 2001
Short Identifier=Imported Pla
Geom File=g01
Flow File=f01
Subcritical Flow
K Sum by GR= 0
Std Step Tol= 0.003
Critical Tol= 0.003
Num of Std Step Trials= 20
Max Error Tol= 0.1
Flow Tol Ratio= 0.001
Split Flow NTrial= 30
Split Flow Tol= 0.02
Split Flow Ratio= 0.02
Log Output Level= 0
Friction Slope Method= 1
Unsteady Friction Slope Method= 2
Parabolic Critical Depth
Global Vel Dist= 0 , 0 , 0
Global Log Level= 0
CheckData=True
Encroach Param=-1 ,0,0, 0
Computation Interval=1HOUR
Output Interval=1HOUR
Run HTab= 0
Run UNet= 0
Run PostProcess= 0
UNET Theta= 1
UNET ZTol= 0.02
UNET ZSATol= 0.1
UNET MxIter= 20
UNET MaxInSteps= 20
UNET DtIC= 0
UNET DtMin= 0
UNET MaxCRTS= 20
UNET WFStab= 2
UNET SFStab= 1
UNET WFX= 1
UNET SFX= 1
UNET Convert EG Bridges=-1
UNET Use Existing IB Tables=-1
Instantaneous Interval=1HOUR
Write IC File= 0
Write Velocity= 0
Write Detailed= 0

--- SONG.f01 (steady flow) ---

Flow Title=Imported Flow 01
Version=Version 3.0.1  Mar 2001
Number of Profiles= 5
Profile Names=10YR,20YR,30YR,50YR,80YR
River Rch & RM=RIVER-1,Reach-1         ,515.00
    4.25    4.68    4.94    5.26    5.55
Boundary for River Rch & Prof#=RIVER-1,Reach-1         , 1
Up Type= 0
Dn Type= 3
Dn Slope=.022
Boundary for River Rch & Prof#=RIVER-1,Reach-1         , 2
Up Type= 0
Dn Type= 3
Dn Slope=.022
Boundary for River Rch & Prof#=RIVER-1,Reach-1         , 3
Up Type= 0
Dn Type= 3
Dn Slope=.022
Boundary for River Rch & Prof#=RIVER-1,Reach-1         , 4
Up Type= 0
Dn Type= 3
Dn Slope=.022
Boundary for River Rch & Prof#=RIVER-1,Reach-1         , 5
Up Type= 0
Dn Type= 3
Dn Slope=.022
DSS Import GetInterval= 0
DSS Import GetPeak= 0
DSS Import FillOption= 0

--- SONG.g01 (geometry) ---

Geom Title=Imported Geom 01
Version=Version 3.0.1  Mar 2001

River Reach=RIVER-1         ,Reach-1
Reach XY= 2
              .5             .95              .5             .05

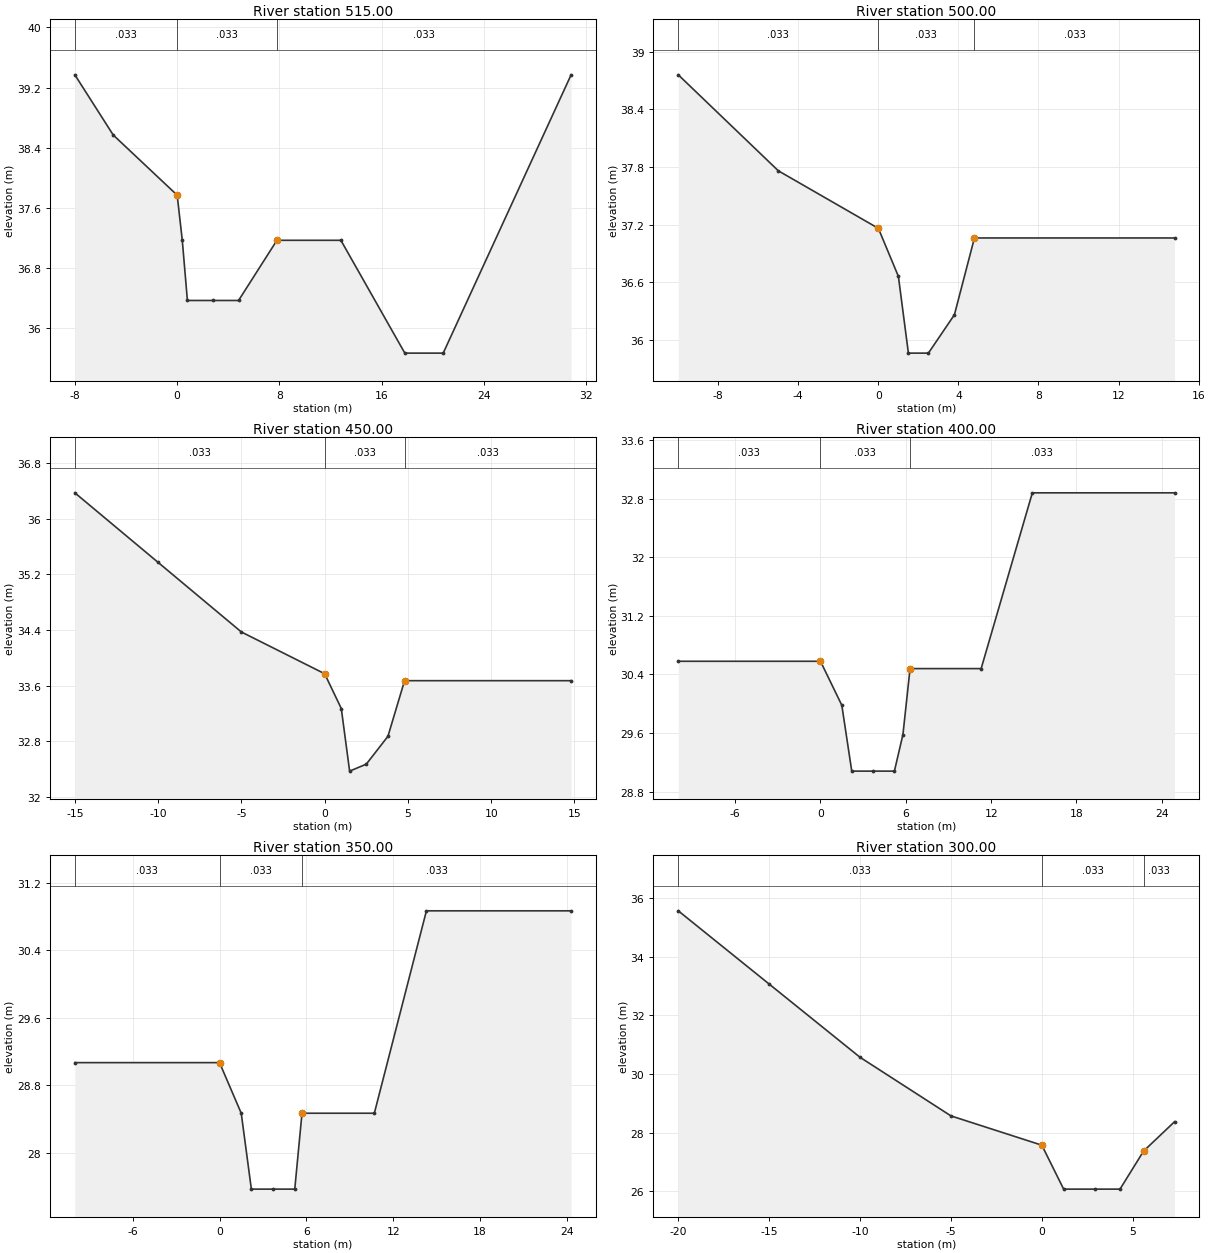
Type RM Length L Ch R = 1 ,515.00  ,15,15,15
BEGIN DESCRIPTION:
10.015
END DESCRIPTION:
#Sta/Elev= 12
      -8   39.37      -5   38.57       0   37.77      .4   37.17      .8   36.37
     2.8   36.37     4.8   36.37     7.8   37.17    12.8   37.17    17.8   35.67
    20.8   35.67    30.8   39.37
#Mann= 3 , 0 , 0
      -8    .033       0       0    .033       0     7.8    .033       0
#XS Ineff= 2 , 0
               0   37.77     7.8           37.17
Permanent Ineff=
       F       F
Bank Sta=0,7.8
XS Rating Curve= 0
Exp/Cntr=.3,.1

Type RM Length L Ch R = 1 ,500.00  ,50,50,50
BEGIN DESCRIPTION:
10
END DESCRIPTION:
#Sta/Elev= 9
     -10   38.76      -5   37.76       0   37.16       1   36.66     1.5   35.86
     2.5   35.86     3.8   36.26     4.8   37.06    14.8   37.06
#Mann= 3 , 0 , 0
     -10    .033       0       0    .033       0     4.8    .033       0
#XS Ineff= 2 , 0
               0   37.16     4.8           37.06
Permanent Ineff=
       F       F
Bank Sta=0,4.8
XS Rating Curve= 0
Exp/Cntr=.3,.1

Type RM Length L Ch R = 1 ,450.00  ,50,50,50
BEGIN DESCRIPTION:
9
END DESCRIPTION:
#Sta/Elev= 10
     -15   36.37     -10   35.37      -5   34.37       0   33.77       1   33.27
     1.5   32.37     2.5   32.47     3.8   32.87     4.8   33.67    14.8   33.67
#Mann= 3 , 0 , 0
     -15    .033       0       0    .033       0     4.8    .033       0
#XS Ineff= 2 , 0
               0   33.77     4.8           33.67
Permanent Ineff=
       F       F
Bank Sta=0,4.8
XS Rating Curve= 0
Exp/Cntr=.3,.1

Type RM Length L Ch R = 1 ,400.00  ,50,50,50
BEGIN DESCRIPTION:
8
END DESCRIPTION:
#Sta/Elev= 11
     -10   30.58       0   30.58     1.5   29.98     2.2   29.08     3.7   29.08
     5.2   29.08     5.8   29.58     6.3   30.48    11.3   30.48    14.9   32.88
    24.9   32.88
#Mann= 3 , 0 , 0
     -10    .033       0       0    .033       0     6.3    .033       0
#XS Ineff= 2 , 0
               0   30.58     6.3           30.48
Permanent Ineff=
       F       F
Bank Sta=0,6.3
XS Rating Curve= 0
Exp/Cntr=.3,.1

Type RM Length L Ch R = 1 ,350.00  ,50,50,50
BEGIN DESCRIPTION:
7
END DESCRIPTION:
#Sta/Elev= 10
     -10   29.07       0   29.07     1.5   28.47     2.2   27.57     3.7   27.57
     5.2   27.57     5.7   28.47    10.7   28.47    14.3   30.87    24.3   30.87
#Mann= 3 , 0 , 0
     -10    .033       0       0    .033       0     5.7    .033       0
#XS Ineff= 2 , 0
               0   29.07     5.7           28.47
Permanent Ineff=
       F       F
Bank Sta=0,5.7
XS Rating Curve= 0
Exp/Cntr=.3,.1

Type RM Length L Ch R = 1 ,300.00  ,50,50,50
BEGIN DESCRIPTION:
6
END DESCRIPTION:
#Sta/Elev= 10
     -20   35.57     -15   33.07     -10   30.57      -5   28.57       0   27.57
     1.2   26.07     2.9   26.07     4.3   26.07     5.6   27.37     7.3   28.37
#Mann= 3 , 0 , 0
     -20    .033       0       0    .033       0     5.6    .033       0
#XS Ineff= 2 , 0
               0   27.57     5.6           27.37
Permanent Ineff=
       F       F
Bank Sta=0,5.6
XS Rating Curve= 0
Exp/Cntr=.3,.1

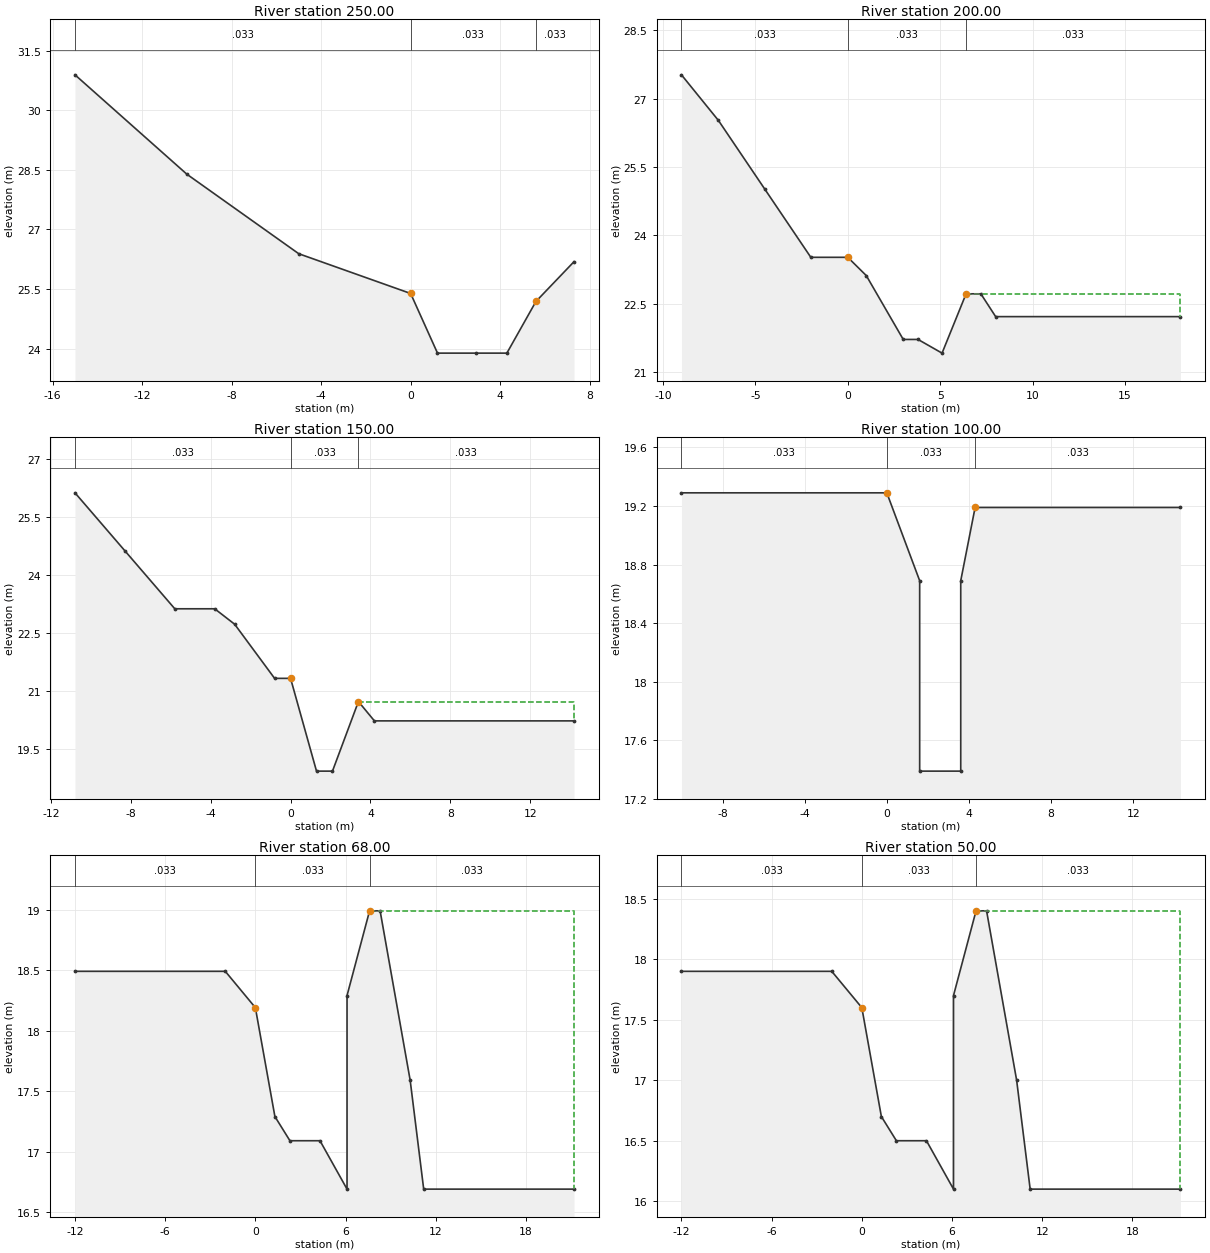
Type RM Length L Ch R = 1 ,250.00  ,50,50,50
BEGIN DESCRIPTION:
5
END DESCRIPTION:
#Sta/Elev= 9
     -15   30.89     -10   28.39      -5   26.39       0   25.39     1.2   23.89
     2.9   23.89     4.3   23.89     5.6   25.19     7.3   26.19
#Mann= 3 , 0 , 0
     -15    .033       0       0    .033       0     5.6    .033       0
#XS Ineff= 2 , 0
               0   25.39     5.6           25.19
Permanent Ineff=
       F       F
Bank Sta=0,5.6
XS Rating Curve= 0
Exp/Cntr=.3,.1

Type RM Length L Ch R = 1 ,200.00  ,50,50,50
BEGIN DESCRIPTION:
4
END DESCRIPTION:
#Sta/Elev= 13
      -9   27.52      -7   26.52    -4.5   25.02      -2   23.52       0   23.52
       1   23.12       3   21.72     3.8   21.72     5.1   21.42     6.4   22.72
     7.2   22.72       8   22.22      18   22.22
#Mann= 3 , 0 , 0
      -9    .033       0       0    .033       0     6.4    .033       0
#XS Ineff= 2 , 0
               0   23.52     6.4           22.72
Permanent Ineff=
       F       F
Bank Sta=0,6.4
XS Rating Curve= 0
Exp/Cntr=.3,.1

Type RM Length L Ch R = 1 ,150.00  ,50,50,50
BEGIN DESCRIPTION:
3
END DESCRIPTION:
#Sta/Elev= 12
   -10.8   26.12    -8.3   24.62    -5.8   23.12    -3.8   23.12    -2.8   22.72
     -.8   21.32       0   21.32     1.3   18.92     2.1   18.92     3.4   20.72
     4.2   20.22    14.2   20.22
#Mann= 3 , 0 , 0
   -10.8    .033       0       0    .033       0     3.4    .033       0
#XS Ineff= 2 , 0
               0   21.32     3.4           20.72
Permanent Ineff=
       F       F
Bank Sta=0,3.4
XS Rating Curve= 0
Exp/Cntr=.3,.1

Type RM Length L Ch R = 1 ,100.00  ,32,32,32
BEGIN DESCRIPTION:
2
END DESCRIPTION:
#Sta/Elev= 8
     -10   19.29       0   19.29     1.6   18.69     1.6   17.39     3.6   17.39
     3.6   18.69     4.3   19.19    14.3   19.19
#Mann= 3 , 0 , 0
     -10    .033       0       0    .033       0     4.3    .033       0
#XS Ineff= 2 , 0
               0   19.29     4.3           19.19
Permanent Ineff=
       F       F
Bank Sta=0,4.3
XS Rating Curve= 0
Exp/Cntr=.3,.1

Type RM Length L Ch R = 1 ,68.00   ,18,18,18
BEGIN DESCRIPTION:
1.018
END DESCRIPTION:
#Sta/Elev= 13
     -12   18.49      -2   18.49       0   18.19     1.3   17.29     2.3   17.09
     4.3   17.09     6.1   16.69     6.1   18.29     7.6   18.99     8.3   18.99
    10.3   17.59    11.2   16.69    21.2   16.69
#Mann= 3 , 0 , 0
     -12    .033       0       0    .033       0     7.6    .033       0
#XS Ineff= 2 , 0
               0   18.19     7.6           18.99
Permanent Ineff=
       F       F
Bank Sta=0,7.6
XS Rating Curve= 0
Exp/Cntr=.3,.1

Type RM Length L Ch R = 1 ,50.00   ,50,50,50
BEGIN DESCRIPTION:
1
END DESCRIPTION:
#Sta/Elev= 13
     -12    17.9      -2    17.9       0    17.6     1.3    16.7     2.3    16.5
     4.3    16.5     6.1    16.1     6.1    17.7     7.6    18.4     8.3    18.4
    10.3      17    11.2    16.1    21.2    16.1
#Mann= 3 , 0 , 0
     -12    .033       0       0    .033       0     7.6    .033       0
#XS Ineff= 2 , 0
               0    17.6     7.6            18.4
Permanent Ineff=
       F       F
Bank Sta=0,7.6
XS Rating Curve= 0
Exp/Cntr=.3,.1

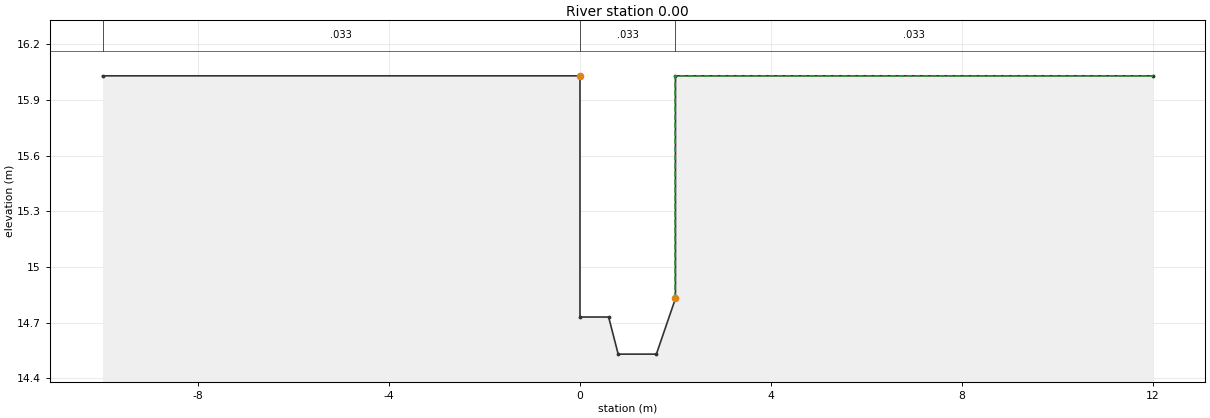
Type RM Length L Ch R = 1 ,0.00    ,0,0,0
BEGIN DESCRIPTION:
0
END DESCRIPTION:
#Sta/Elev= 9
     -10   16.03       0   16.03       0   14.73      .6   14.73      .8   14.53
     1.6   14.53       2   14.83       2   16.03      12   16.03
#Mann= 3 , 0 , 0
     -10    .033       0       0    .033       0       2    .033       0
#XS Ineff= 2 , 0
               0   16.03       2           16.03
Permanent Ineff=
       F       F
Bank Sta=0,2
XS Rating Curve= 0
Exp/Cntr=.3,.1

Chan Stop Cuts=-1