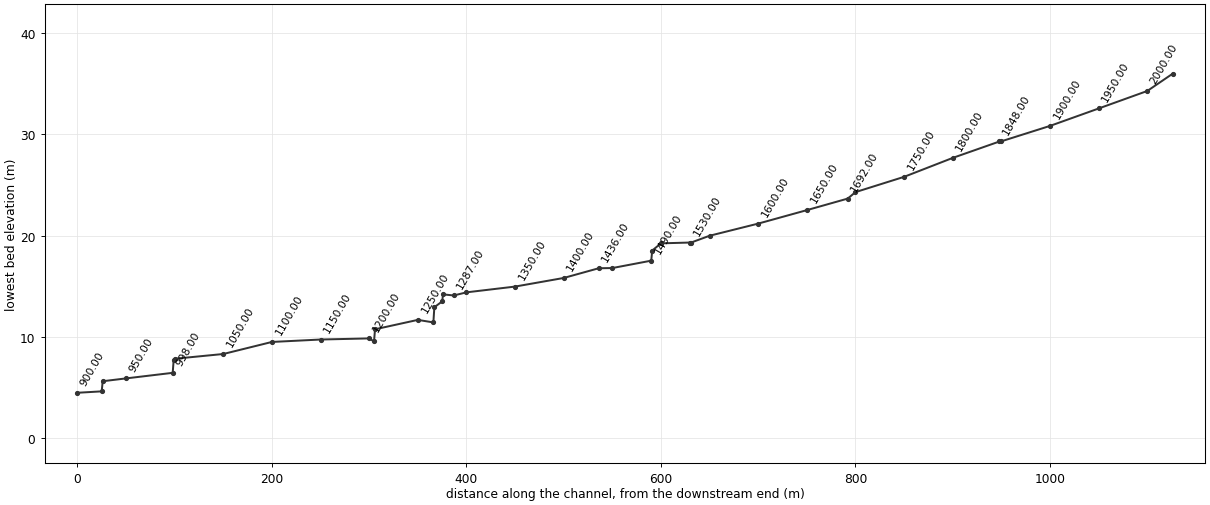
--- SAM.prj (project) ---

Proj Title=SAM
Current Plan=p01
Default Exp/Contr=.3,.1
SI Units
Geom File=g01
Flow File=f01
Plan File=p01
Y Axis Title=Elevation
X Axis Title(PF)=Main Channel Distance
X Axis Title(XS)=Station
BEGIN DESCRIPTION:
           BACK WATER COMPUTATION
      APPLICATION OF HEC-2 BY Samju Construction Engineering
      SAMGOL-STREEM : 30 YR
END DESCRIPTION:
DSS Export Rating Curves= 0
DSS Export Rating Curve Sorted= 0
DSS Export Volume Flow Curves= 0
DXF OffsetX= 0
DXF OffsetY= 0
DXF ScaleX= 1
DXF ScaleY= 10

--- SAM.p01 (plan) ---

Plan Title=Imported Plan 01
Version=Version 3.0.1  Mar 2001
Short Identifier=Imported Pla
Geom File=g01
Flow File=f01
Subcritical Flow
K Sum by GR= 0
Std Step Tol= 0.003
Critical Tol= 0.003
Num of Std Step Trials= 20
Max Error Tol= 0.1
Flow Tol Ratio= 0.001
Split Flow NTrial= 30
Split Flow Tol= 0.02
Split Flow Ratio= 0.02
Log Output Level= 0
Friction Slope Method= 1
Unsteady Friction Slope Method= 2
Parabolic Critical Depth
Global Vel Dist= 0 , 0 , 0
Global Log Level= 0
CheckData=True
Encroach Param=-1 ,0,0, 0
Computation Interval=1HOUR
Output Interval=1HOUR
Run HTab= 0
Run UNet= 0
Run PostProcess= 0
UNET Theta= 1
UNET ZTol= 0.02
UNET ZSATol= 0.1
UNET MxIter= 20
UNET MaxInSteps= 20
UNET DtIC= 0
UNET DtMin= 0
UNET MaxCRTS= 20
UNET WFStab= 2
UNET SFStab= 1
UNET WFX= 1
UNET SFX= 1
UNET Convert EG Bridges=-1
UNET Use Existing IB Tables=-1
Instantaneous Interval=1HOUR
Write IC File= 0
Write Velocity= 0
Write Detailed= 0

--- SAM.f01 (steady flow) ---

Flow Title=Imported Flow 01
Version=Version 3.0.1  Mar 2001
Number of Profiles= 5
Profile Names=10YR,20YR,30YR,50YR,80YR
River Rch & RM=RIVER-1,Reach-1         ,2026.00
   25.57   28.17   29.68   31.59   33.35
River Rch & RM=RIVER-1,Reach-1         ,750.00
   30.75   33.89   35.73   38.05   40.18
Boundary for River Rch & Prof#=RIVER-1,Reach-1         , 1
Up Type= 0
Dn Type= 3
Dn Slope=.038
Boundary for River Rch & Prof#=RIVER-1,Reach-1         , 2
Up Type= 0
Dn Type= 3
Dn Slope=.038
Boundary for River Rch & Prof#=RIVER-1,Reach-1         , 3
Up Type= 0
Dn Type= 3
Dn Slope=.038
Boundary for River Rch & Prof#=RIVER-1,Reach-1         , 4
Up Type= 0
Dn Type= 3
Dn Slope=.038
Boundary for River Rch & Prof#=RIVER-1,Reach-1         , 5
Up Type= 0
Dn Type= 3
Dn Slope=.038
DSS Import GetInterval= 0
DSS Import GetPeak= 0
DSS Import FillOption= 0

--- SAM.g01 (geometry) ---

Geom Title=Imported Geom 01
Version=Version 3.0.1  Mar 2001

River Reach=RIVER-1         ,Reach-1
Reach XY= 2
              .5             .95              .5             .05

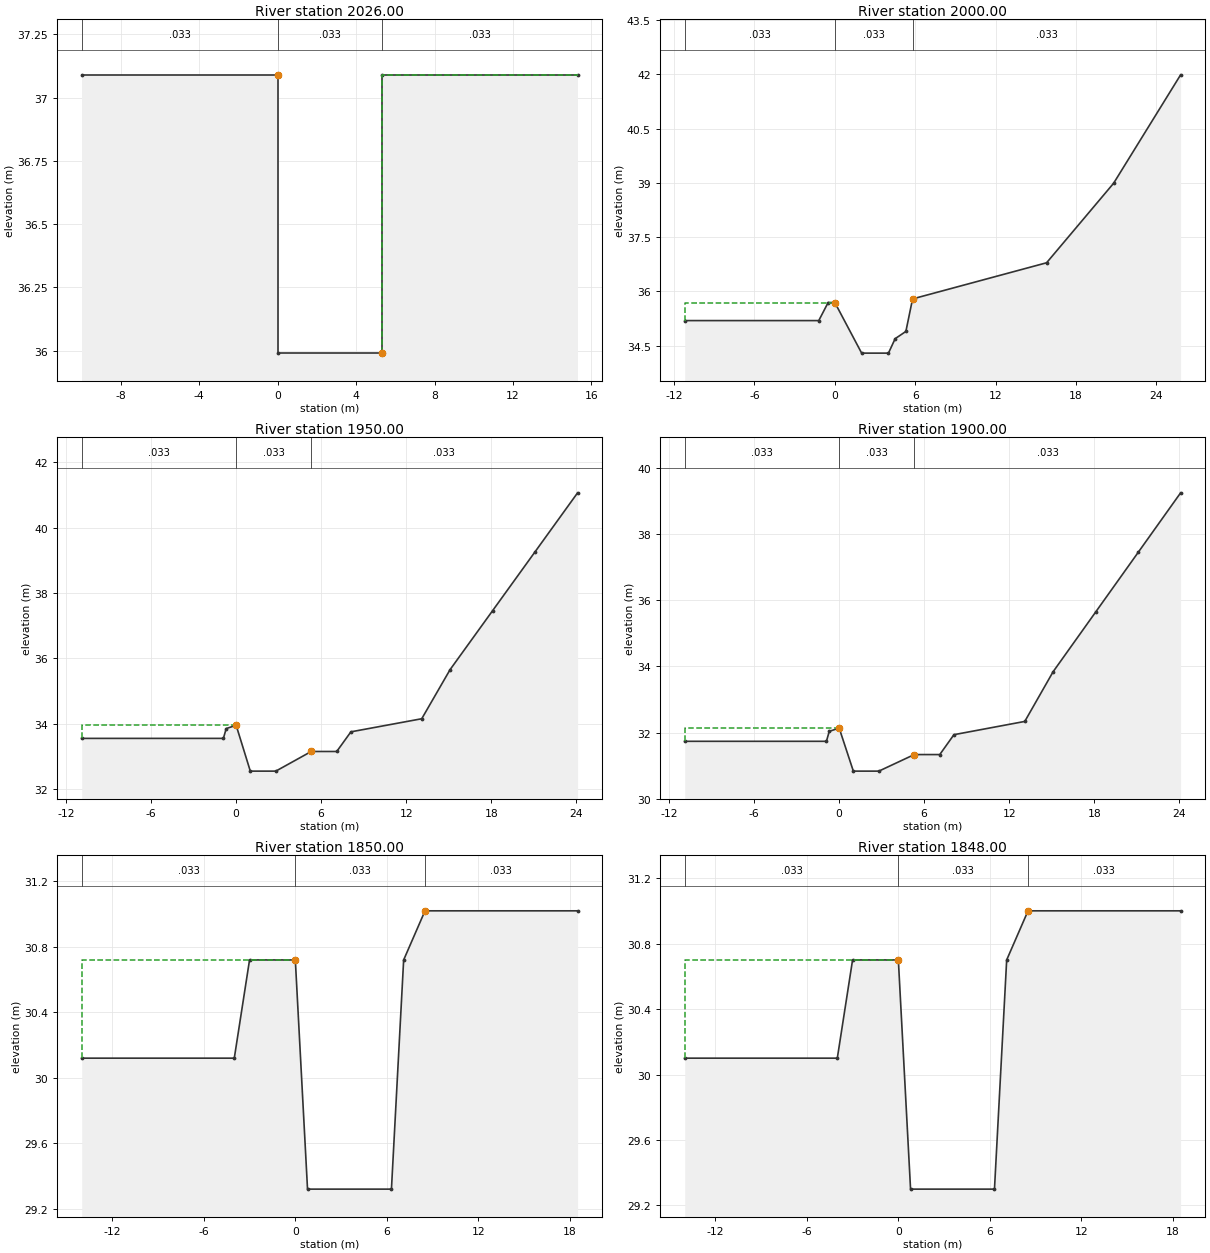
Type RM Length L Ch R = 1 ,2026.00 ,26,26,26
BEGIN DESCRIPTION:
40.026
END DESCRIPTION:
#Sta/Elev= 6
     -10   37.09       0   37.09       0   35.99     5.3   35.99     5.3   37.09
    15.3   37.09
#Mann= 3 , 0 , 0
     -10    .033       0       0    .033       0     5.3    .033       0
#XS Ineff= 2 , 0
               0   37.09     5.3           37.09
Permanent Ineff=
       F       F
Bank Sta=0,5.3
XS Rating Curve= 0
Exp/Cntr=.3,.1

Type RM Length L Ch R = 1 ,2000.00 ,50,50,50
BEGIN DESCRIPTION:
40
END DESCRIPTION:
#Sta/Elev= 12
   -11.2   35.19    -1.2   35.19     -.5   35.69       0   35.69       2   34.29
       4   34.29     4.5   34.69     5.3   34.89     5.8   35.79    15.8   36.79
    20.8   38.99    25.8   41.99
#Mann= 3 , 0 , 0
   -11.2    .033       0       0    .033       0     5.8    .033       0
#XS Ineff= 2 , 0
               0   35.69     5.8           35.79
Permanent Ineff=
       F       F
Bank Sta=0,5.8
XS Rating Curve= 0
Exp/Cntr=.3,.1

Type RM Length L Ch R = 1 ,1950.00 ,50,50,50
BEGIN DESCRIPTION:
39
END DESCRIPTION:
#Sta/Elev= 14
   -10.9   33.56     -.9   33.56     -.7   33.86       0   33.96       1   32.56
     2.8   32.56     5.3   33.16     7.1   33.16     8.1   33.76    13.1   34.16
    15.1   35.66    18.1   37.46    21.1   39.26    24.1   41.06
#Mann= 3 , 0 , 0
   -10.9    .033       0       0    .033       0     5.3    .033       0
#XS Ineff= 2 , 0
               0   33.96     5.3           33.16
Permanent Ineff=
       F       F
Bank Sta=0,5.3
XS Rating Curve= 0
Exp/Cntr=.3,.1

Type RM Length L Ch R = 1 ,1900.00 ,50,50,50
BEGIN DESCRIPTION:
38
END DESCRIPTION:
#Sta/Elev= 14
   -10.9   31.74     -.9   31.74     -.7   32.04       0   32.14       1   30.84
     2.8   30.84     5.3   31.34     7.1   31.34     8.1   31.94    13.1   32.34
    15.1   33.84    18.1   35.64    21.1   37.44    24.1   39.24
#Mann= 3 , 0 , 0
   -10.9    .033       0       0    .033       0     5.3    .033       0
#XS Ineff= 2 , 0
               0   32.14     5.3           31.34
Permanent Ineff=
       F       F
Bank Sta=0,5.3
XS Rating Curve= 0
Exp/Cntr=.3,.1

Type RM Length L Ch R = 1 ,1850.00 ,2,2,2
BEGIN DESCRIPTION:
37
END DESCRIPTION:
#Sta/Elev= 9
     -14   30.12      -4   30.12      -3   30.72       0   30.72      .8   29.32
     6.3   29.32     7.1   30.72     8.5   31.02    18.5   31.02
#Mann= 3 , 0 , 0
     -14    .033       0       0    .033       0     8.5    .033       0
#XS Ineff= 2 , 0
               0   30.72     8.5           31.02
Permanent Ineff=
       F       F
Bank Sta=0,8.5
XS Rating Curve= 0
Exp/Cntr=.3,.1

Type RM Length L Ch R = 1 ,1848.00 ,48,48,48
BEGIN DESCRIPTION:
36.048
END DESCRIPTION:
#Sta/Elev= 9
     -14    30.1      -4    30.1      -3    30.7       0    30.7      .8    29.3
     6.3    29.3     7.1    30.7     8.5      31    18.5      31
#Mann= 3 , 0 , 0
     -14    .033       0       0    .033       0     8.5    .033       0
#XS Ineff= 2 , 0
               0    30.7     8.5              31
Permanent Ineff=
       F       F
Bank Sta=0,8.5
XS Rating Curve= 0
Exp/Cntr=.3,.1

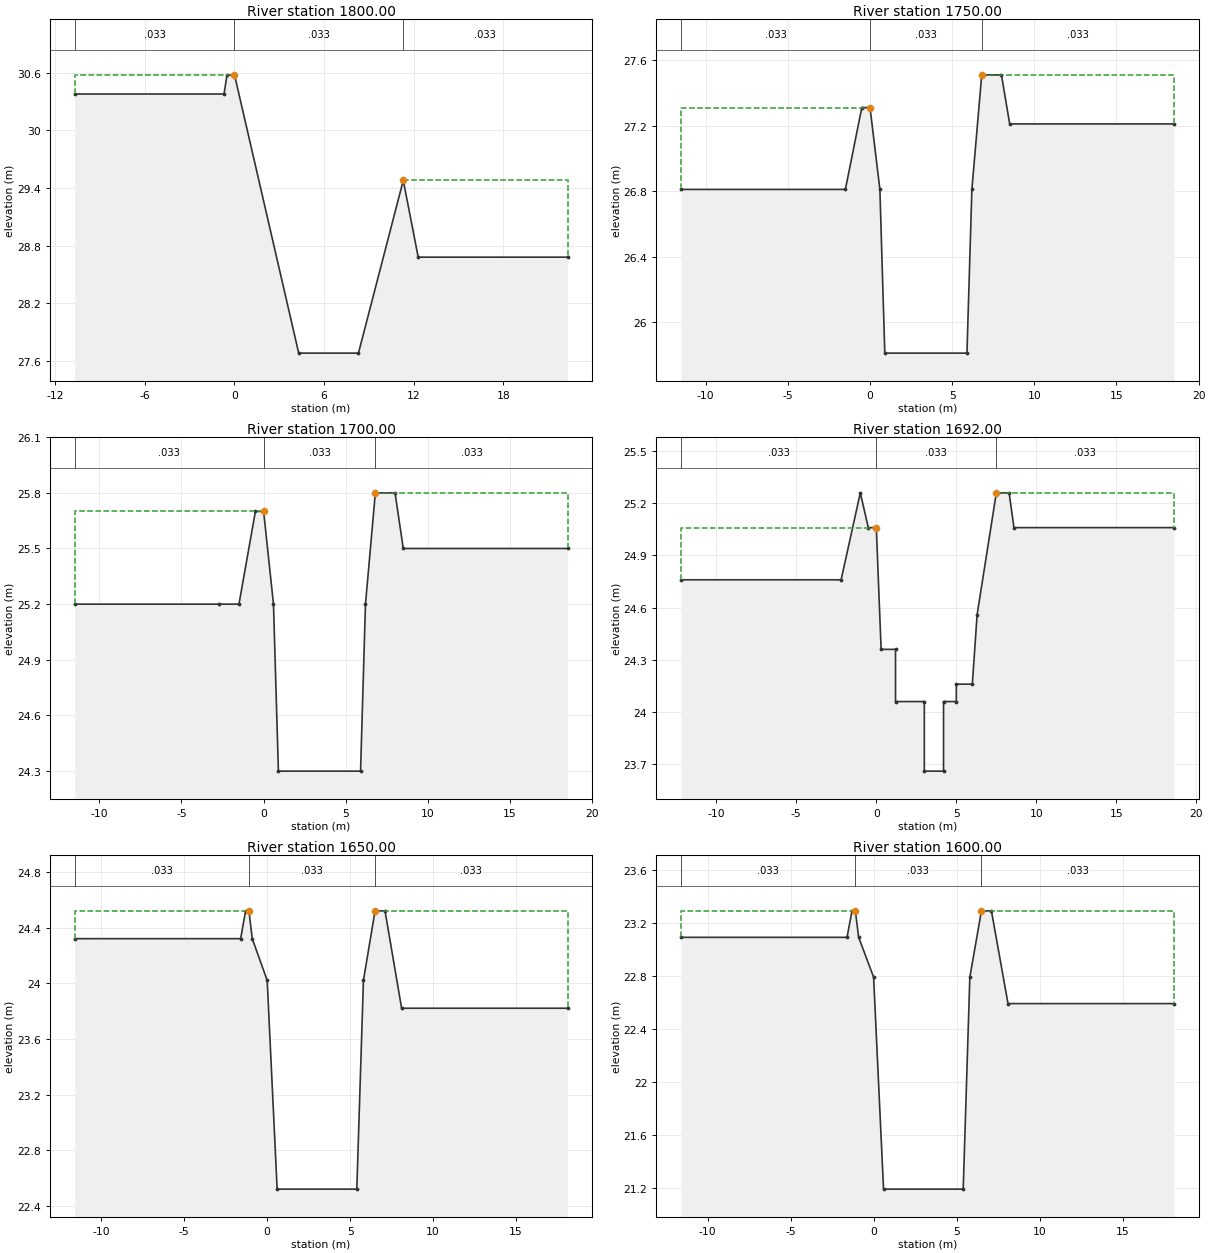
Type RM Length L Ch R = 1 ,1800.00 ,50,50,50
BEGIN DESCRIPTION:
36
END DESCRIPTION:
#Sta/Elev= 9
   -10.7   30.38     -.7   30.38     -.5   30.58       0   30.58     4.3   27.68
     8.3   27.68    11.3   29.48    12.3   28.68    22.3   28.68
#Mann= 3 , 0 , 0
   -10.7    .033       0       0    .033       0    11.3    .033       0
#XS Ineff= 2 , 0
               0   30.58    11.3           29.48
Permanent Ineff=
       F       F
Bank Sta=0,11.3
XS Rating Curve= 0
Exp/Cntr=.3,.1

Type RM Length L Ch R = 1 ,1750.00 ,50,50,50
BEGIN DESCRIPTION:
35
END DESCRIPTION:
#Sta/Elev= 12
   -11.5   26.81    -1.5   26.81     -.5   27.31       0   27.31      .6   26.81
      .9   25.81     5.9   25.81     6.2   26.81     6.8   27.51       8   27.51
     8.5   27.21    18.5   27.21
#Mann= 3 , 0 , 0
   -11.5    .033       0       0    .033       0     6.8    .033       0
#XS Ineff= 2 , 0
               0   27.31     6.8           27.51
Permanent Ineff=
       F       F
Bank Sta=0,6.8
XS Rating Curve= 0
Exp/Cntr=.3,.1

Type RM Length L Ch R = 1 ,1700.00 ,8,8,8
BEGIN DESCRIPTION:
34
END DESCRIPTION:
#Sta/Elev= 13
   -11.5    25.2    -2.7    25.2    -1.5    25.2     -.5    25.7       0    25.7
      .6    25.2      .9    24.3     5.9    24.3     6.2    25.2     6.8    25.8
       8    25.8     8.5    25.5    18.5    25.5
#Mann= 3 , 0 , 0
   -11.5    .033       0       0    .033       0     6.8    .033       0
#XS Ineff= 2 , 0
               0    25.7     6.8            25.8
Permanent Ineff=
       F       F
Bank Sta=0,6.8
XS Rating Curve= 0
Exp/Cntr=.3,.1

Type RM Length L Ch R = 1 ,1692.00 ,42,42,42
BEGIN DESCRIPTION:
33.042
END DESCRIPTION:
#Sta/Elev= 20
   -12.2   24.76    -2.2   24.76      -1   25.26     -.5   25.06       0   25.06
      .3   24.36     1.2   24.36     1.2   24.06       3   24.06       3   23.66
     4.2   23.66     4.2   24.06       5   24.06       5   24.16       6   24.16
     6.3   24.56     7.5   25.26     8.3   25.26     8.6   25.06    18.6   25.06
#Mann= 3 , 0 , 0
   -12.2    .033       0       0    .033       0     7.5    .033       0
#XS Ineff= 2 , 0
               0   25.06     7.5           25.26
Permanent Ineff=
       F       F
Bank Sta=0,7.5
XS Rating Curve= 0
Exp/Cntr=.3,.1

Type RM Length L Ch R = 1 ,1650.00 ,50,50,50
BEGIN DESCRIPTION:
33
END DESCRIPTION:
#Sta/Elev= 13
   -11.6   24.32    -1.6   24.32    -1.3   24.52    -1.1   24.52     -.9   24.32
       0   24.02      .6   22.52     5.4   22.52     5.8   24.02     6.5   24.52
     7.1   24.52     8.1   23.82    18.1   23.82
#Mann= 3 , 0 , 0
   -11.6    .033       0    -1.1    .033       0     6.5    .033       0
#XS Ineff= 2 , 0
            -1.1   24.52     6.5           24.52
Permanent Ineff=
       F       F
Bank Sta=-1.1,6.5
XS Rating Curve= 0
Exp/Cntr=.3,.1

Type RM Length L Ch R = 1 ,1600.00 ,50,50,50
BEGIN DESCRIPTION:
32
END DESCRIPTION:
#Sta/Elev= 13
   -11.6   23.09    -1.6   23.09    -1.3   23.29    -1.1   23.29     -.9   23.09
       0   22.79      .6   21.19     5.4   21.19     5.8   22.79     6.5   23.29
     7.1   23.29     8.1   22.59    18.1   22.59
#Mann= 3 , 0 , 0
   -11.6    .033       0    -1.1    .033       0     6.5    .033       0
#XS Ineff= 2 , 0
            -1.1   23.29     6.5           23.29
Permanent Ineff=
       F       F
Bank Sta=-1.1,6.5
XS Rating Curve= 0
Exp/Cntr=.3,.1

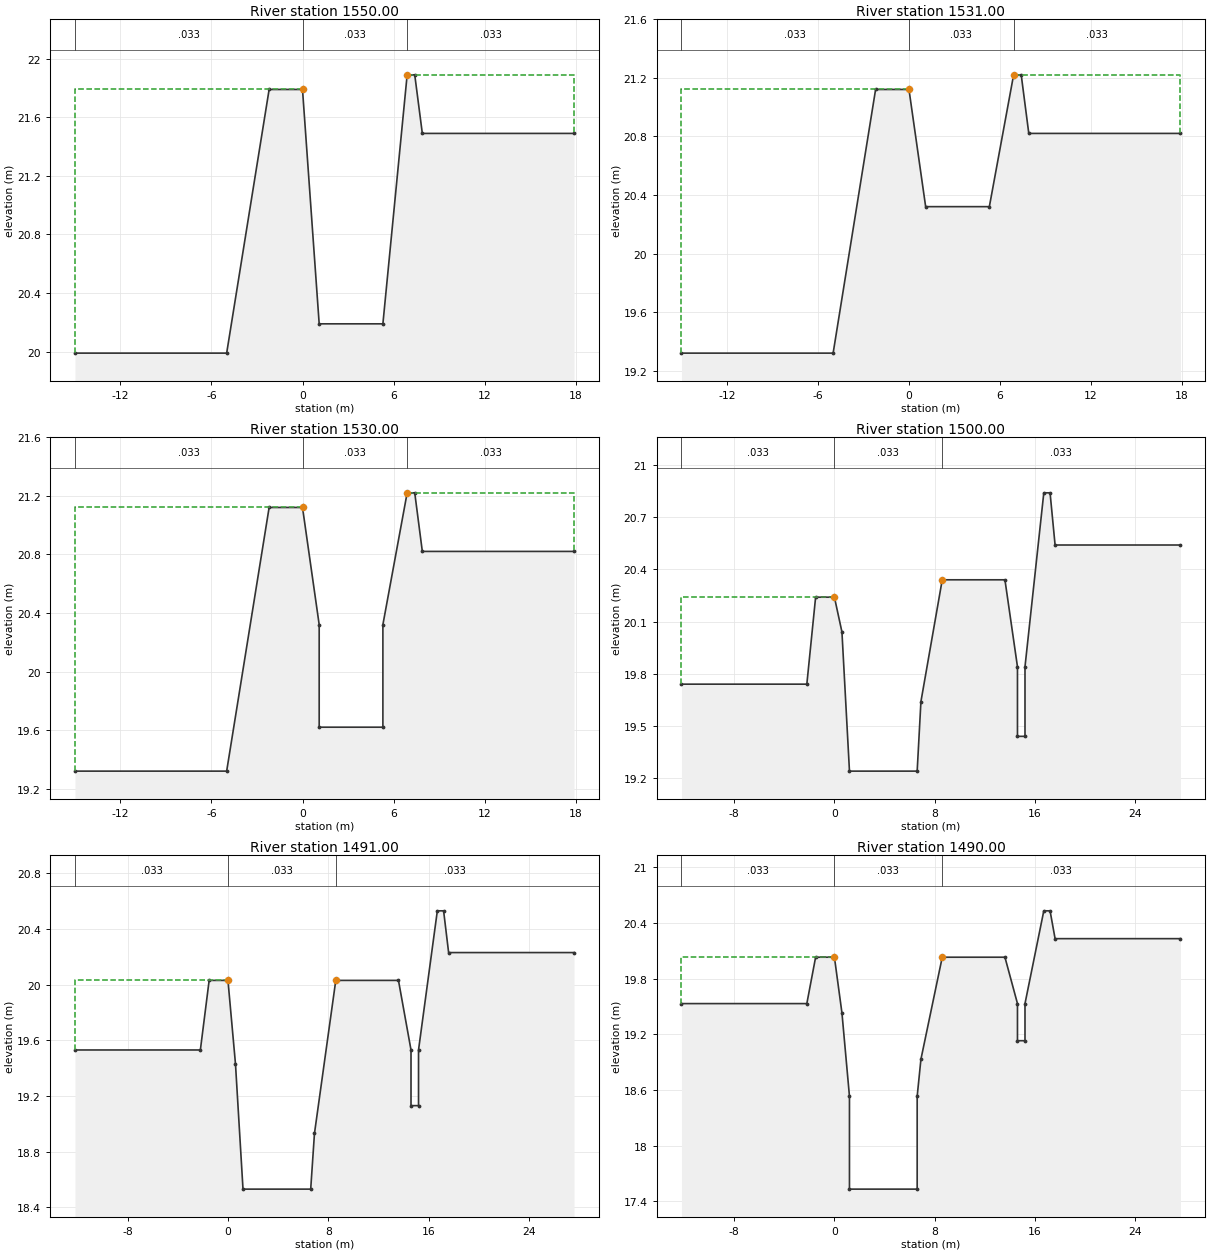
Type RM Length L Ch R = 1 ,1550.00 ,19,19,19
BEGIN DESCRIPTION:
31
END DESCRIPTION:
#Sta/Elev= 10
     -15   19.99      -5   19.99    -2.2   21.79       0   21.79     1.1   20.19
     5.3   20.19     6.9   21.89     7.4   21.89     7.9   21.49    17.9   21.49
#Mann= 3 , 0 , 0
     -15    .033       0       0    .033       0     6.9    .033       0
#XS Ineff= 2 , 0
               0   21.79     6.9           21.89
Permanent Ineff=
       F       F
Bank Sta=0,6.9
XS Rating Curve= 0
Exp/Cntr=.3,.1

Type RM Length L Ch R = 1 ,1531.00 ,1,1,1
BEGIN DESCRIPTION:
30.031
END DESCRIPTION:
#Sta/Elev= 10
     -15   19.32      -5   19.32    -2.2   21.12       0   21.12     1.1   20.32
     5.3   20.32     6.9   21.22     7.4   21.22     7.9   20.82    17.9   20.82
#Mann= 3 , 0 , 0
     -15    .033       0       0    .033       0     6.9    .033       0
#XS Ineff= 2 , 0
               0   21.12     6.9           21.22
Permanent Ineff=
       F       F
Bank Sta=0,6.9
XS Rating Curve= 0
Exp/Cntr=.3,.1

Type RM Length L Ch R = 1 ,1530.00 ,30,30,30
BEGIN DESCRIPTION:
30.03
END DESCRIPTION:
#Sta/Elev= 12
     -15   19.32      -5   19.32    -2.2   21.12       0   21.12     1.1   20.32
     1.1   19.62     5.3   19.62     5.3   20.32     6.9   21.22     7.4   21.22
     7.9   20.82    17.9   20.82
#Mann= 3 , 0 , 0
     -15    .033       0       0    .033       0     6.9    .033       0
#XS Ineff= 2 , 0
               0   21.12     6.9           21.22
Permanent Ineff=
       F       F
Bank Sta=0,6.9
XS Rating Curve= 0
Exp/Cntr=.3,.1

Type RM Length L Ch R = 1 ,1500.00 ,9,9,9
BEGIN DESCRIPTION:
30
END DESCRIPTION:
#Sta/Elev= 18
   -12.2   19.74    -2.2   19.74    -1.5   20.24       0   20.24      .6   20.04
     1.2   19.24     6.6   19.24     6.9   19.64     8.6   20.34    13.6   20.34
    14.6   19.84    14.6   19.44    15.2   19.44    15.2   19.84    16.7   20.84
    17.2   20.84    17.6   20.54    27.6   20.54
#Mann= 3 , 0 , 0
   -12.2    .033       0       0    .033       0     8.6    .033       0
#XS Ineff= 2 , 0
               0   20.24     8.6           20.34
Permanent Ineff=
       F       F
Bank Sta=0,8.6
XS Rating Curve= 0
Exp/Cntr=.3,.1

Type RM Length L Ch R = 1 ,1491.00 ,1,1,1
BEGIN DESCRIPTION:
29.041
END DESCRIPTION:
#Sta/Elev= 18
   -12.2   19.53    -2.2   19.53    -1.5   20.03       0   20.03      .6   19.43
     1.2   18.53     6.6   18.53     6.9   18.93     8.6   20.03    13.6   20.03
    14.6   19.53    14.6   19.13    15.2   19.13    15.2   19.53    16.7   20.53
    17.2   20.53    17.6   20.23    27.6   20.23
#Mann= 3 , 0 , 0
   -12.2    .033       0       0    .033       0     8.6    .033       0
#XS Ineff= 2 , 0
               0   20.03     8.6           20.03
Permanent Ineff=
       F       F
Bank Sta=0,8.6
XS Rating Curve= 0
Exp/Cntr=.3,.1

Type RM Length L Ch R = 1 ,1490.00 ,40,40,40
BEGIN DESCRIPTION:
29.04
END DESCRIPTION:
#Sta/Elev= 20
   -12.2   19.53    -2.2   19.53    -1.5   20.03       0   20.03      .6   19.43
     1.2   18.53     1.2   17.53     6.6   17.53     6.6   18.53     6.9   18.93
     8.6   20.03    13.6   20.03    14.6   19.53    14.6   19.13    15.2   19.13
    15.2   19.53    16.7   20.53    17.2   20.53    17.6   20.23    27.6   20.23
#Mann= 3 , 0 , 0
   -12.2    .033       0       0    .033       0     8.6    .033       0
#XS Ineff= 2 , 0
               0   20.03     8.6           20.03
Permanent Ineff=
       F       F
Bank Sta=0,8.6
XS Rating Curve= 0
Exp/Cntr=.3,.1

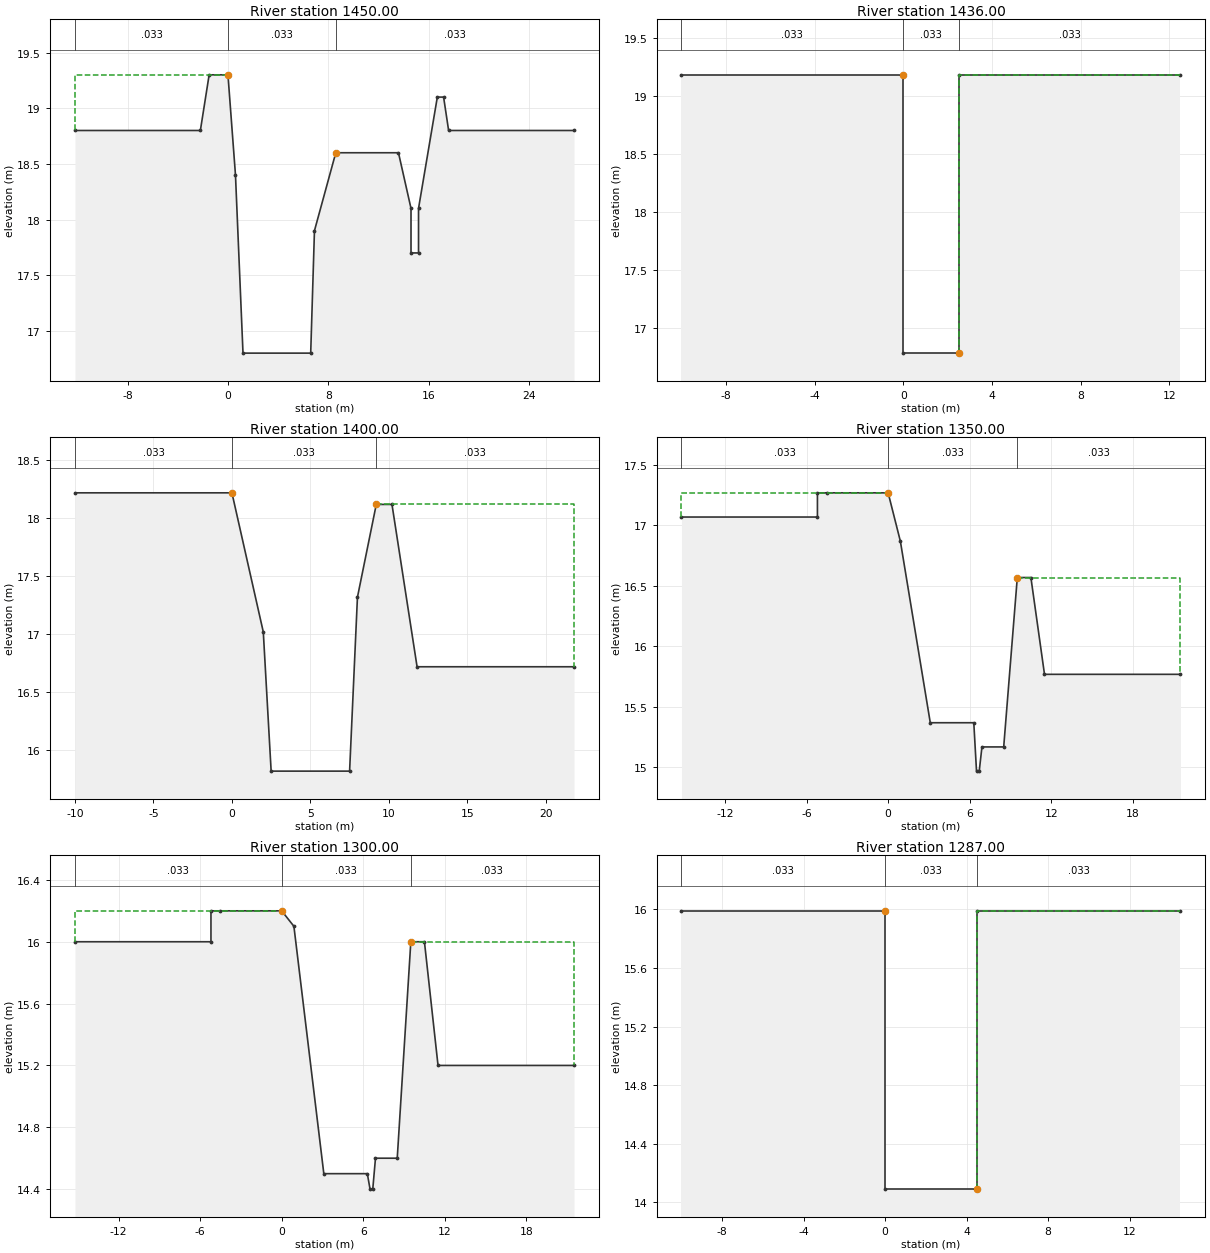
Type RM Length L Ch R = 1 ,1450.00 ,14,14,14
BEGIN DESCRIPTION:
29
END DESCRIPTION:
#Sta/Elev= 18
   -12.2    18.8    -2.2    18.8    -1.5    19.3       0    19.3      .6    18.4
     1.2    16.8     6.6    16.8     6.9    17.9     8.6    18.6    13.6    18.6
    14.6    18.1    14.6    17.7    15.2    17.7    15.2    18.1    16.7    19.1
    17.2    19.1    17.6    18.8    27.6    18.8
#Mann= 3 , 0 , 0
   -12.2    .033       0       0    .033       0     8.6    .033       0
#XS Ineff= 2 , 0
               0    19.3     8.6            18.6
Permanent Ineff=
       F       F
Bank Sta=0,8.6
XS Rating Curve= 0
Exp/Cntr=.3,.1

Type RM Length L Ch R = 1 ,1436.00 ,36,36,36
BEGIN DESCRIPTION:
28.036
END DESCRIPTION:
#Sta/Elev= 6
     -10   19.18       0   19.18       0   16.78     2.5   16.78     2.5   19.18
    12.5   19.18
#Mann= 3 , 0 , 0
     -10    .033       0       0    .033       0     2.5    .033       0
#XS Ineff= 2 , 0
               0   19.18     2.5           19.18
Permanent Ineff=
       F       F
Bank Sta=0,2.5
XS Rating Curve= 0
Exp/Cntr=.3,.1

Type RM Length L Ch R = 1 ,1400.00 ,50,50,50
BEGIN DESCRIPTION:
28
END DESCRIPTION:
#Sta/Elev= 10
     -10   18.22       0   18.22       2   17.02     2.5   15.82     7.5   15.82
       8   17.32     9.2   18.12    10.2   18.12    11.8   16.72    21.8   16.72
#Mann= 3 , 0 , 0
     -10    .033       0       0    .033       0     9.2    .033       0
#XS Ineff= 2 , 0
               0   18.22     9.2           18.12
Permanent Ineff=
       F       F
Bank Sta=0,9.2
XS Rating Curve= 0
Exp/Cntr=.3,.1

Type RM Length L Ch R = 1 ,1350.00 ,50,50,50
BEGIN DESCRIPTION:
27
END DESCRIPTION:
#Sta/Elev= 16
   -15.2   17.07    -5.2   17.07    -5.2   17.27    -4.5   17.27       0   17.27
      .9   16.87     3.1   15.37     6.3   15.37     6.5   14.97     6.7   14.97
     6.9   15.17     8.5   15.17     9.5   16.57    10.5   16.57    11.5   15.77
    21.5   15.77
#Mann= 3 , 0 , 0
   -15.2    .033       0       0    .033       0     9.5    .033       0
#XS Ineff= 2 , 0
               0   17.27     9.5           16.57
Permanent Ineff=
       F       F
Bank Sta=0,9.5
XS Rating Curve= 0
Exp/Cntr=.3,.1

Type RM Length L Ch R = 1 ,1300.00 ,13,13,13
BEGIN DESCRIPTION:
26
END DESCRIPTION:
#Sta/Elev= 16
   -15.2      16    -5.2      16    -5.2    16.2    -4.5    16.2       0    16.2
      .9    16.1     3.1    14.5     6.3    14.5     6.5    14.4     6.7    14.4
     6.9    14.6     8.5    14.6     9.5      16    10.5      16    11.5    15.2
    21.5    15.2
#Mann= 3 , 0 , 0
   -15.2    .033       0       0    .033       0     9.5    .033       0
#XS Ineff= 2 , 0
               0    16.2     9.5              16
Permanent Ineff=
       F       F
Bank Sta=0,9.5
XS Rating Curve= 0
Exp/Cntr=.3,.1

Type RM Length L Ch R = 1 ,1287.00 ,11,11,11
BEGIN DESCRIPTION:
25.037
END DESCRIPTION:
#Sta/Elev= 6
     -10   15.99       0   15.99       0   14.09     4.5   14.09     4.5   15.99
    14.5   15.99
#Mann= 3 , 0 , 0
     -10    .033       0       0    .033       0     4.5    .033       0
#XS Ineff= 2 , 0
               0   15.99     4.5           15.99
Permanent Ineff=
       F       F
Bank Sta=0,4.5
XS Rating Curve= 0
Exp/Cntr=.3,.1

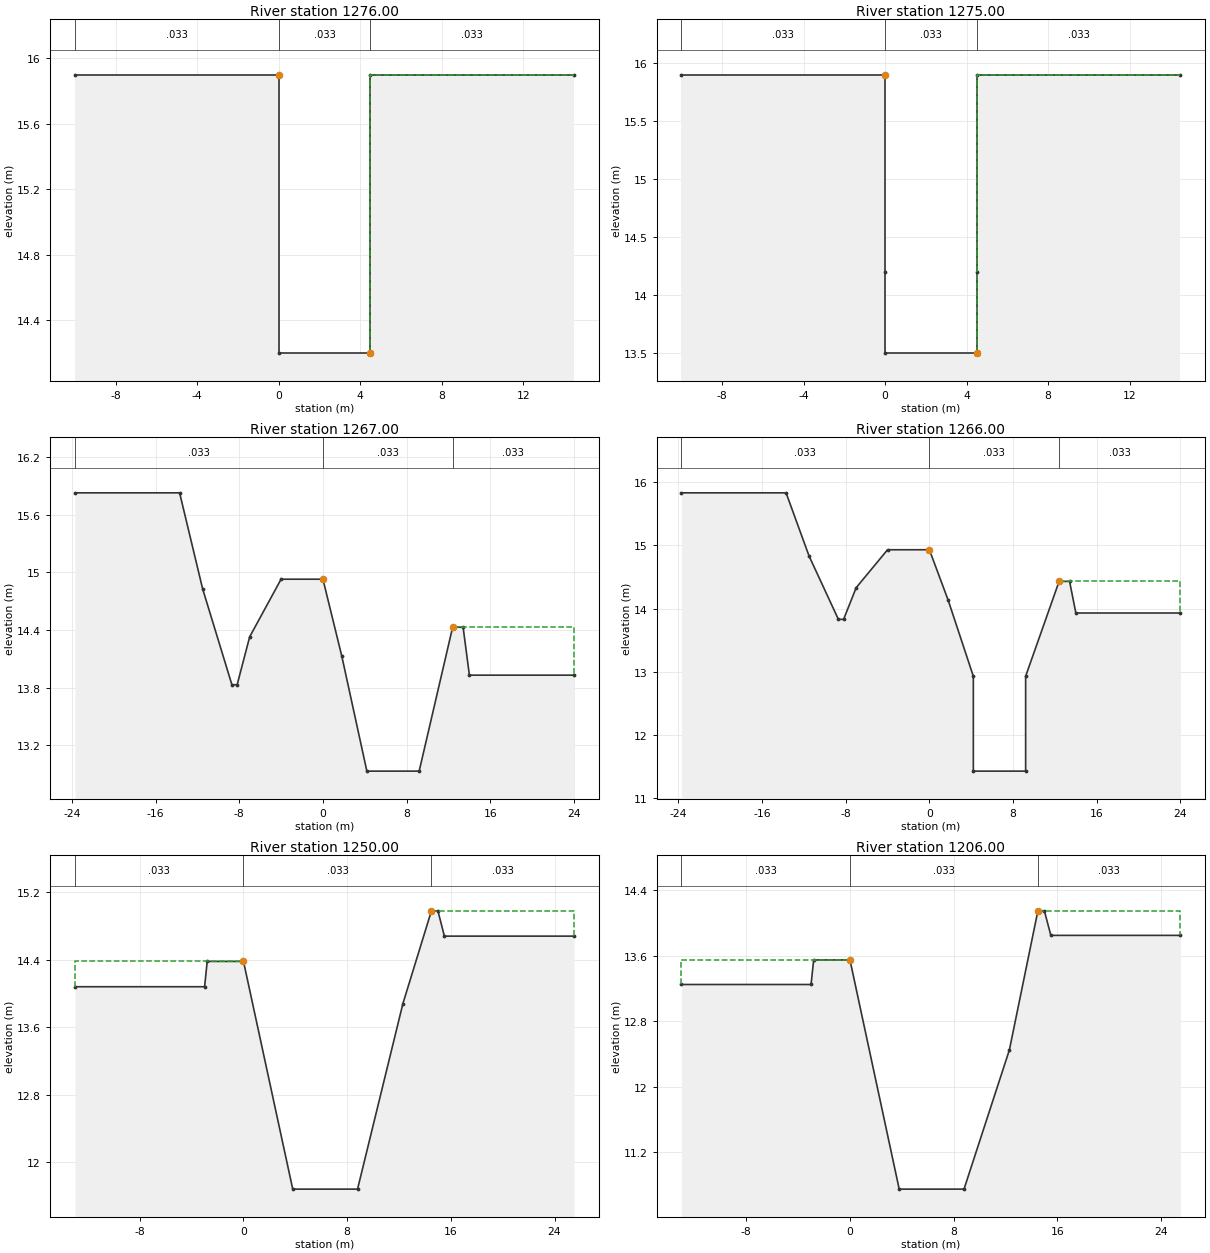
Type RM Length L Ch R = 1 ,1276.00 ,1,1,1
BEGIN DESCRIPTION:
25.026
END DESCRIPTION:
#Sta/Elev= 6
     -10    15.9       0    15.9       0    14.2     4.5    14.2     4.5    15.9
    14.5    15.9
#Mann= 3 , 0 , 0
     -10    .033       0       0    .033       0     4.5    .033       0
#XS Ineff= 2 , 0
               0    15.9     4.5            15.9
Permanent Ineff=
       F       F
Bank Sta=0,4.5
XS Rating Curve= 0
Exp/Cntr=.3,.1

Type RM Length L Ch R = 1 ,1275.00 ,8,8,8
BEGIN DESCRIPTION:
25.025
END DESCRIPTION:
#Sta/Elev= 8
     -10    15.9       0    15.9       0    14.2       0    13.5     4.5    13.5
     4.5    14.2     4.5    15.9    14.5    15.9
#Mann= 3 , 0 , 0
     -10    .033       0       0    .033       0     4.5    .033       0
#XS Ineff= 2 , 0
               0    15.9     4.5            15.9
Permanent Ineff=
       F       F
Bank Sta=0,4.5
XS Rating Curve= 0
Exp/Cntr=.3,.1

Type RM Length L Ch R = 1 ,1267.00 ,1,1,1
BEGIN DESCRIPTION:
25.017
END DESCRIPTION:
#Sta/Elev= 15
   -23.7   15.83   -13.7   15.83   -11.5   14.83    -8.7   13.83    -8.2   13.83
      -7   14.33      -4   14.93       0   14.93     1.8   14.13     4.2   12.93
     9.2   12.93    12.4   14.43    13.4   14.43      14   13.93      24   13.93
#Mann= 3 , 0 , 0
   -23.7    .033       0       0    .033       0    12.4    .033       0
#XS Ineff= 2 , 0
               0   14.93    12.4           14.43
Permanent Ineff=
       F       F
Bank Sta=0,12.4
XS Rating Curve= 0
Exp/Cntr=.3,.1

Type RM Length L Ch R = 1 ,1266.00 ,16,16,16
BEGIN DESCRIPTION:
25.016
END DESCRIPTION:
#Sta/Elev= 17
   -23.7   15.83   -13.7   15.83   -11.5   14.83    -8.7   13.83    -8.2   13.83
      -7   14.33      -4   14.93       0   14.93     1.8   14.13     4.2   12.93
     4.2   11.43     9.2   11.43     9.2   12.93    12.4   14.43    13.4   14.43
      14   13.93      24   13.93
#Mann= 3 , 0 , 0
   -23.7    .033       0       0    .033       0    12.4    .033       0
#XS Ineff= 2 , 0
               0   14.93    12.4           14.43
Permanent Ineff=
       F       F
Bank Sta=0,12.4
XS Rating Curve= 0
Exp/Cntr=.3,.1

Type RM Length L Ch R = 1 ,1250.00 ,44,44,44
BEGIN DESCRIPTION:
25
END DESCRIPTION:
#Sta/Elev= 11
     -13   14.08      -3   14.08    -2.8   14.38       0   14.38     3.8   11.68
     8.8   11.68    12.3   13.88    14.5   14.98      15   14.98    15.5   14.68
    25.5   14.68
#Mann= 3 , 0 , 0
     -13    .033       0       0    .033       0    14.5    .033       0
#XS Ineff= 2 , 0
               0   14.38    14.5           14.98
Permanent Ineff=
       F       F
Bank Sta=0,14.5
XS Rating Curve= 0
Exp/Cntr=.3,.1

Type RM Length L Ch R = 1 ,1206.00 ,1,1,1
BEGIN DESCRIPTION:
24.006
END DESCRIPTION:
#Sta/Elev= 11
     -13   13.25      -3   13.25    -2.8   13.55       0   13.55     3.8   10.75
     8.8   10.75    12.3   12.45    14.5   14.15      15   14.15    15.5   13.85
    25.5   13.85
#Mann= 3 , 0 , 0
     -13    .033       0       0    .033       0    14.5    .033       0
#XS Ineff= 2 , 0
               0   13.55    14.5           14.15
Permanent Ineff=
       F       F
Bank Sta=0,14.5
XS Rating Curve= 0
Exp/Cntr=.3,.1

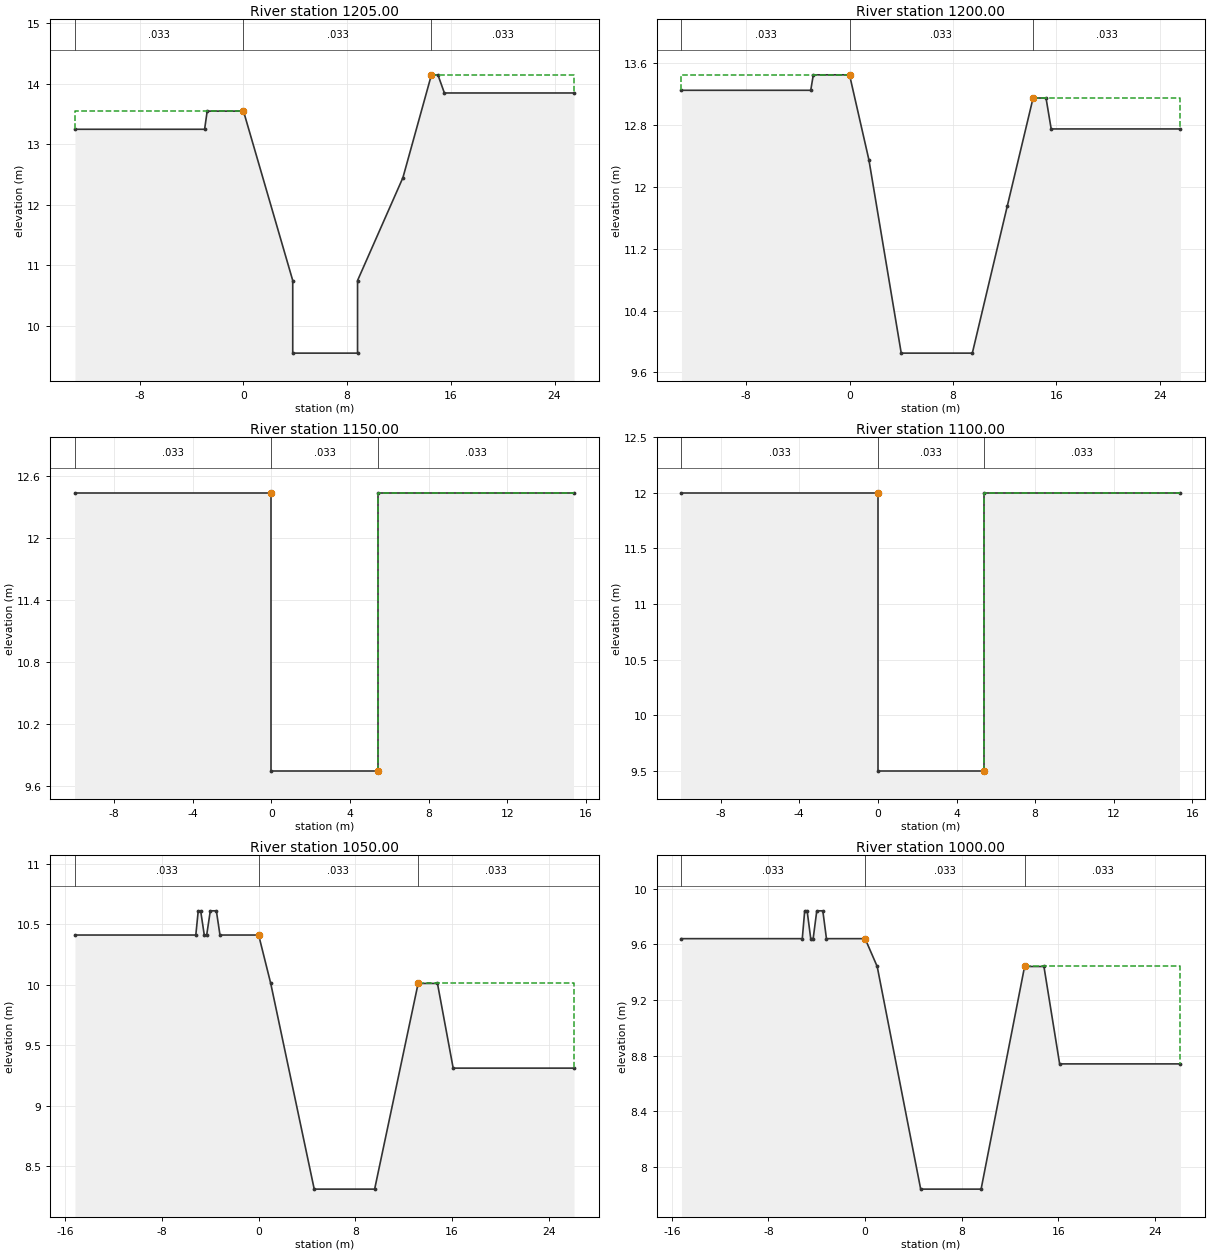
Type RM Length L Ch R = 1 ,1205.00 ,5,5,5
BEGIN DESCRIPTION:
24.005
END DESCRIPTION:
#Sta/Elev= 13
     -13   13.25      -3   13.25    -2.8   13.55       0   13.55     3.8   10.75
     3.8    9.55     8.8    9.55     8.8   10.75    12.3   12.45    14.5   14.15
      15   14.15    15.5   13.85    25.5   13.85
#Mann= 3 , 0 , 0
     -13    .033       0       0    .033       0    14.5    .033       0
#XS Ineff= 2 , 0
               0   13.55    14.5           14.15
Permanent Ineff=
       F       F
Bank Sta=0,14.5
XS Rating Curve= 0
Exp/Cntr=.3,.1

Type RM Length L Ch R = 1 ,1200.00 ,50,50,50
BEGIN DESCRIPTION:
24
END DESCRIPTION:
#Sta/Elev= 12
     -13   13.25      -3   13.25    -2.8   13.45       0   13.45     1.5   12.35
       4    9.85     9.5    9.85    12.2   11.75    14.2   13.15    15.2   13.15
    15.6   12.75    25.6   12.75
#Mann= 3 , 0 , 0
     -13    .033       0       0    .033       0    14.2    .033       0
#XS Ineff= 2 , 0
               0   13.45    14.2           13.15
Permanent Ineff=
       F       F
Bank Sta=0,14.2
XS Rating Curve= 0
Exp/Cntr=.3,.1

Type RM Length L Ch R = 1 ,1150.00 ,50,50,50
BEGIN DESCRIPTION:
23
END DESCRIPTION:
#Sta/Elev= 6
     -10   12.44       0   12.44       0    9.74     5.4    9.74     5.4   12.44
    15.4   12.44
#Mann= 3 , 0 , 0
     -10    .033       0       0    .033       0     5.4    .033       0
#XS Ineff= 2 , 0
               0   12.44     5.4           12.44
Permanent Ineff=
       F       F
Bank Sta=0,5.4
XS Rating Curve= 0
Exp/Cntr=.3,.1

Type RM Length L Ch R = 1 ,1100.00 ,50,50,50
BEGIN DESCRIPTION:
22
END DESCRIPTION:
#Sta/Elev= 6
     -10      12       0      12       0     9.5     5.4     9.5     5.4      12
    15.4      12
#Mann= 3 , 0 , 0
     -10    .033       0       0    .033       0     5.4    .033       0
#XS Ineff= 2 , 0
               0      12     5.4              12
Permanent Ineff=
       F       F
Bank Sta=0,5.4
XS Rating Curve= 0
Exp/Cntr=.3,.1

Type RM Length L Ch R = 1 ,1050.00 ,50,50,50
BEGIN DESCRIPTION:
21
END DESCRIPTION:
#Sta/Elev= 17
   -15.2   10.41    -5.2   10.41      -5   10.61    -4.8   10.61    -4.5   10.41
    -4.3   10.41      -4   10.61    -3.5   10.61    -3.2   10.41       0   10.41
       1   10.01     4.6    8.31     9.6    8.31    13.2   10.01    14.8   10.01
    16.1    9.31    26.1    9.31
#Mann= 3 , 0 , 0
   -15.2    .033       0       0    .033       0    13.2    .033       0
#XS Ineff= 2 , 0
               0   10.41    13.2           10.01
Permanent Ineff=
       F       F
Bank Sta=0,13.2
XS Rating Curve= 0
Exp/Cntr=.3,.1

Type RM Length L Ch R = 1 ,1000.00 ,1,1,1
BEGIN DESCRIPTION:
20
END DESCRIPTION:
#Sta/Elev= 17
   -15.2    9.64    -5.2    9.64      -5    9.84    -4.8    9.84    -4.5    9.64
    -4.3    9.64      -4    9.84    -3.5    9.84    -3.2    9.64       0    9.64
       1    9.44     4.6    7.84     9.6    7.84    13.2    9.44    14.8    9.44
    16.1    8.74    26.1    8.74
#Mann= 3 , 0 , 0
   -15.2    .033       0       0    .033       0    13.2    .033       0
#XS Ineff= 2 , 0
               0    9.64    13.2            9.44
Permanent Ineff=
       F       F
Bank Sta=0,13.2
XS Rating Curve= 0
Exp/Cntr=.3,.1

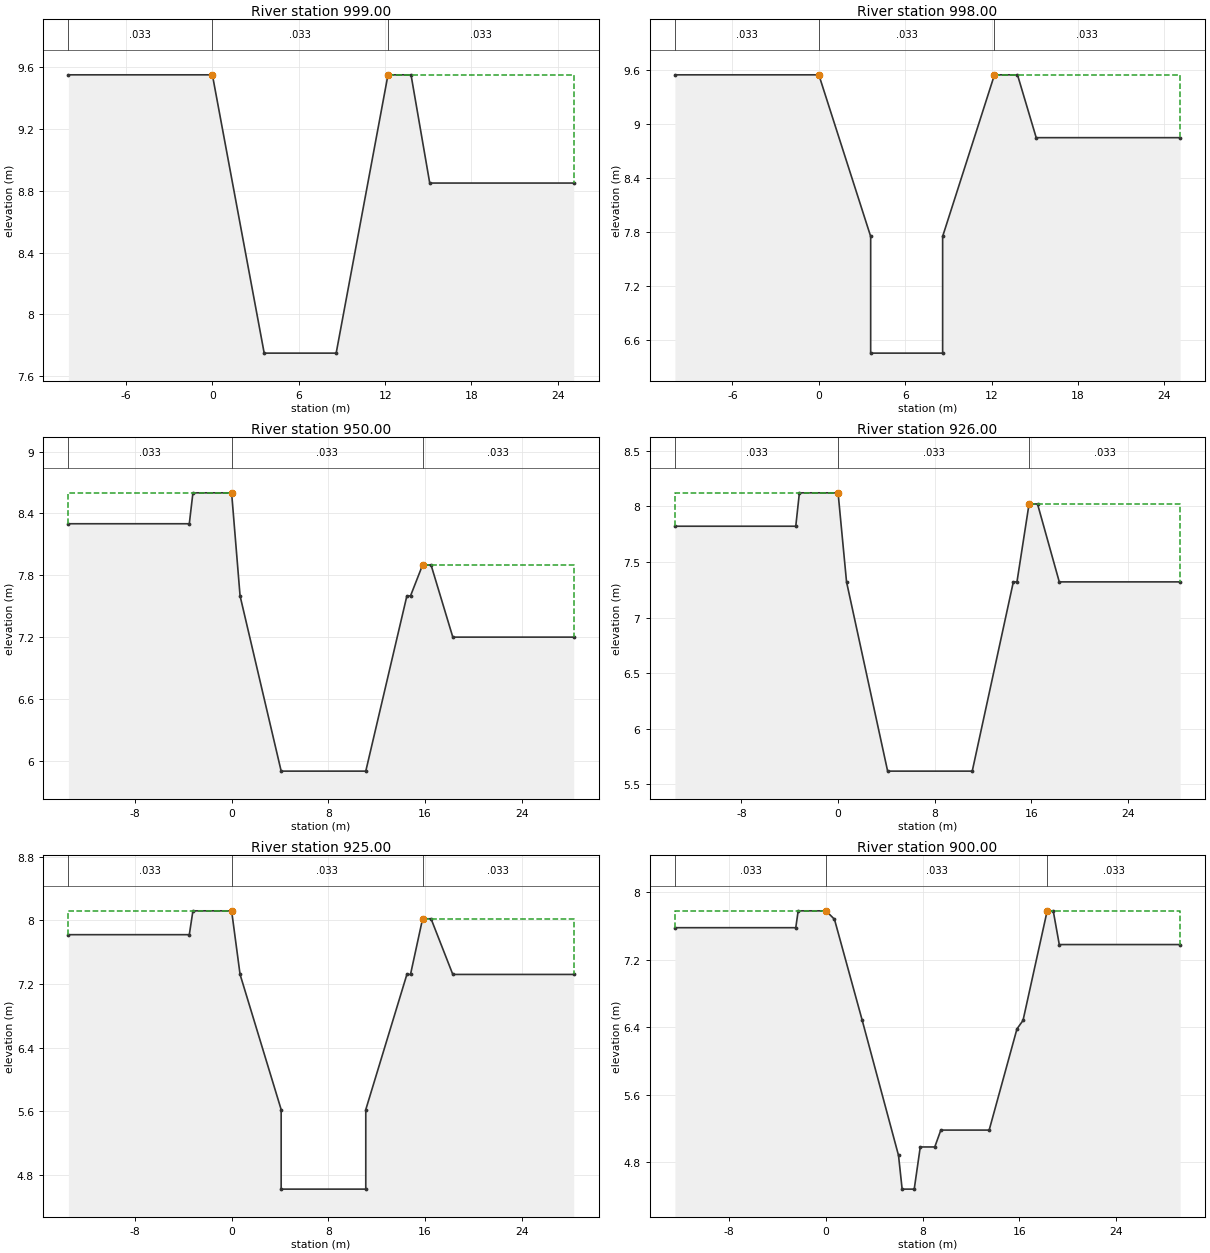
Type RM Length L Ch R = 1 ,999.00  ,1,1,1
BEGIN DESCRIPTION:
19.049
END DESCRIPTION:
#Sta/Elev= 8
     -10    9.55       0    9.55     3.6    7.75     8.6    7.75    12.2    9.55
    13.8    9.55    15.1    8.85    25.1    8.85
#Mann= 3 , 0 , 0
     -10    .033       0       0    .033       0    12.2    .033       0
#XS Ineff= 2 , 0
               0    9.55    12.2            9.55
Permanent Ineff=
       F       F
Bank Sta=0,12.2
XS Rating Curve= 0
Exp/Cntr=.3,.1

Type RM Length L Ch R = 1 ,998.00  ,48,48,48
BEGIN DESCRIPTION:
19.048
END DESCRIPTION:
#Sta/Elev= 10
     -10    9.55       0    9.55     3.6    7.75     3.6    6.45     8.6    6.45
     8.6    7.75    12.2    9.55    13.8    9.55    15.1    8.85    25.1    8.85
#Mann= 3 , 0 , 0
     -10    .033       0       0    .033       0    12.2    .033       0
#XS Ineff= 2 , 0
               0    9.55    12.2            9.55
Permanent Ineff=
       F       F
Bank Sta=0,12.2
XS Rating Curve= 0
Exp/Cntr=.3,.1

Type RM Length L Ch R = 1 ,950.00  ,24,24,24
BEGIN DESCRIPTION:
19
END DESCRIPTION:
#Sta/Elev= 13
   -13.5     8.3    -3.5     8.3    -3.2     8.6       0     8.6      .7     7.6
     4.1     5.9    11.1     5.9    14.5     7.6    14.8     7.6    15.8     7.9
    16.5     7.9    18.3     7.2    28.3     7.2
#Mann= 3 , 0 , 0
   -13.5    .033       0       0    .033       0    15.8    .033       0
#XS Ineff= 2 , 0
               0     8.6    15.8             7.9
Permanent Ineff=
       F       F
Bank Sta=0,15.8
XS Rating Curve= 0
Exp/Cntr=.3,.1

Type RM Length L Ch R = 1 ,926.00  ,1,1,1
BEGIN DESCRIPTION:
18.026
END DESCRIPTION:
#Sta/Elev= 13
   -13.5    7.82    -3.5    7.82    -3.2    8.12       0    8.12      .7    7.32
     4.1    5.62    11.1    5.62    14.5    7.32    14.8    7.32    15.8    8.02
    16.5    8.02    18.3    7.32    28.3    7.32
#Mann= 3 , 0 , 0
   -13.5    .033       0       0    .033       0    15.8    .033       0
#XS Ineff= 2 , 0
               0    8.12    15.8            8.02
Permanent Ineff=
       F       F
Bank Sta=0,15.8
XS Rating Curve= 0
Exp/Cntr=.3,.1

Type RM Length L Ch R = 1 ,925.00  ,25,25,25
BEGIN DESCRIPTION:
18.025
END DESCRIPTION:
#Sta/Elev= 15
   -13.5    7.82    -3.5    7.82    -3.2    8.12       0    8.12      .7    7.32
     4.1    5.62     4.1    4.62    11.1    4.62    11.1    5.62    14.5    7.32
    14.8    7.32    15.8    8.02    16.5    8.02    18.3    7.32    28.3    7.32
#Mann= 3 , 0 , 0
   -13.5    .033       0       0    .033       0    15.8    .033       0
#XS Ineff= 2 , 0
               0    8.12    15.8            8.02
Permanent Ineff=
       F       F
Bank Sta=0,15.8
XS Rating Curve= 0
Exp/Cntr=.3,.1

Type RM Length L Ch R = 1 ,900.00  ,21,21,21
BEGIN DESCRIPTION:
18
END DESCRIPTION:
#Sta/Elev= 19
   -12.5    7.58    -2.5    7.58    -2.3    7.78       0    7.78      .7    7.68
       3    6.48       6    4.88     6.3    4.48     7.3    4.48     7.8    4.98
       9    4.98     9.5    5.18    13.5    5.18    15.8    6.38    16.3    6.48
    18.3    7.78    18.8    7.78    19.3    7.38    29.3    7.38
#Mann= 3 , 0 , 0
   -12.5    .033       0       0    .033       0    18.3    .033       0
#XS Ineff= 2 , 0
               0    7.78    18.3            7.78
Permanent Ineff=
       F       F
Bank Sta=0,18.3
XS Rating Curve= 0
Exp/Cntr=.3,.1