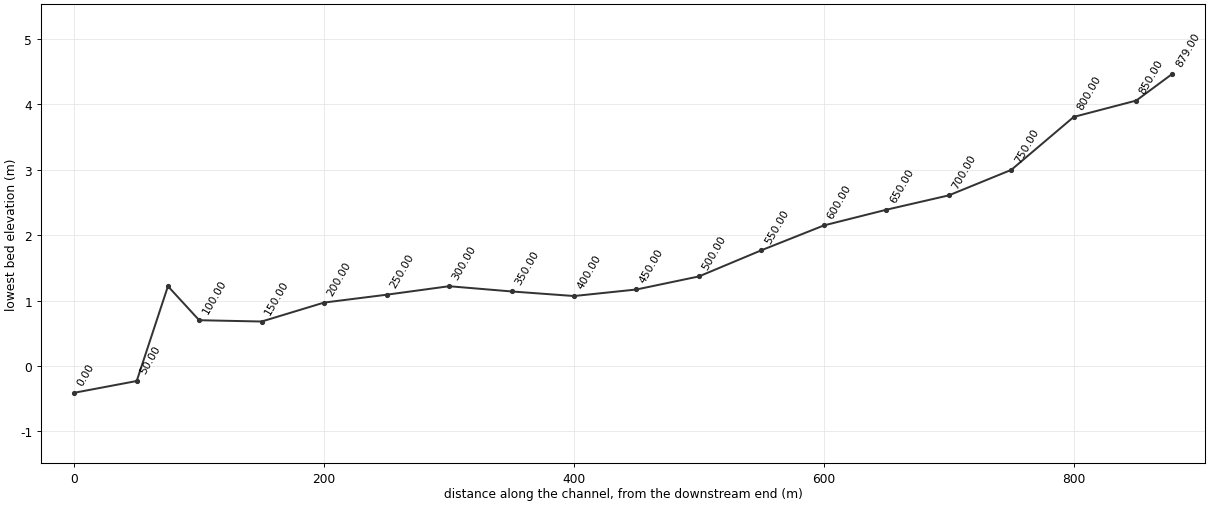
HEC-RAS study SAM.prj: SAM

--- SAM.g01 (geometry) --- (continued)

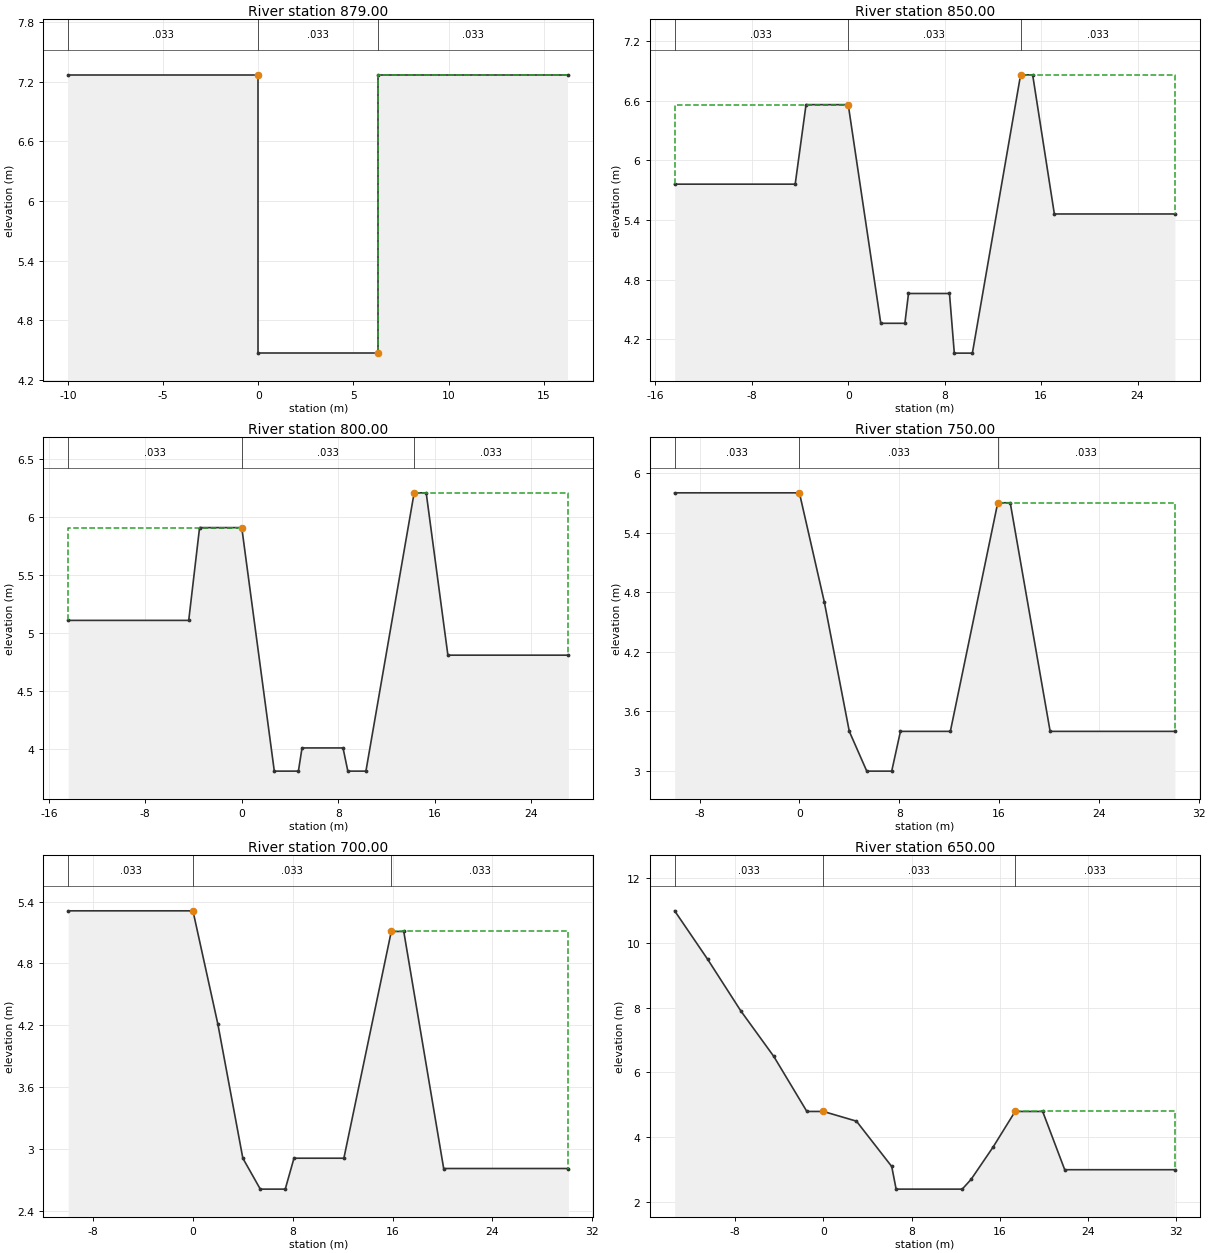
Type RM Length L Ch R = 1 ,879.00  ,29,29,29
BEGIN DESCRIPTION:
17.029
END DESCRIPTION:
#Sta/Elev= 6
     -10    7.27       0    7.27       0    4.47     6.3    4.47     6.3    7.27
    16.3    7.27
#Mann= 3 , 0 , 0
     -10    .033       0       0    .033       0     6.3    .033       0
#XS Ineff= 2 , 0
               0    7.27     6.3            7.27
Permanent Ineff=
       F       F
Bank Sta=0,6.3
XS Rating Curve= 0
Exp/Cntr=.3,.1

Type RM Length L Ch R = 1 ,850.00  ,50,50,50
BEGIN DESCRIPTION:
17
END DESCRIPTION:
#Sta/Elev= 14
   -14.4    5.76    -4.4    5.76    -3.5    6.56       0    6.56     2.7    4.36
     4.7    4.36       5    4.66     8.4    4.66     8.8    4.06    10.3    4.06
    14.3    6.86    15.3    6.86    17.1    5.46    27.1    5.46
#Mann= 3 , 0 , 0
   -14.4    .033       0       0    .033       0    14.3    .033       0
#XS Ineff= 2 , 0
               0    6.56    14.3            6.86
Permanent Ineff=
       F       F
Bank Sta=0,14.3
XS Rating Curve= 0
Exp/Cntr=.3,.1

Type RM Length L Ch R = 1 ,800.00  ,50,50,50
BEGIN DESCRIPTION:
16
END DESCRIPTION:
#Sta/Elev= 14
   -14.4    5.11    -4.4    5.11    -3.5    5.91       0    5.91     2.7    3.81
     4.7    3.81       5    4.01     8.4    4.01     8.8    3.81    10.3    3.81
    14.3    6.21    15.3    6.21    17.1    4.81    27.1    4.81
#Mann= 3 , 0 , 0
   -14.4    .033       0       0    .033       0    14.3    .033       0
#XS Ineff= 2 , 0
               0    5.91    14.3            6.21
Permanent Ineff=
       F       F
Bank Sta=0,14.3
XS Rating Curve= 0
Exp/Cntr=.3,.1

Type RM Length L Ch R = 1 ,750.00  ,50,50,50
BEGIN DESCRIPTION:
15
END DESCRIPTION:
#Sta/Elev= 12
     -10     5.8       0     5.8       2     4.7       4     3.4     5.4       3
     7.4       3     8.1     3.4    12.1     3.4    15.9     5.7    16.9     5.7
    20.1     3.4    30.1     3.4
#Mann= 3 , 0 , 0
     -10    .033       0       0    .033       0    15.9    .033       0
#XS Ineff= 2 , 0
               0     5.8    15.9             5.7
Permanent Ineff=
       F       F
Bank Sta=0,15.9
XS Rating Curve= 0
Exp/Cntr=.3,.1

Type RM Length L Ch R = 1 ,700.00  ,50,50,50
BEGIN DESCRIPTION:
14
END DESCRIPTION:
#Sta/Elev= 12
     -10    5.31       0    5.31       2    4.21       4    2.91     5.4    2.61
     7.4    2.61     8.1    2.91    12.1    2.91    15.9    5.11    16.9    5.11
    20.1    2.81    30.1    2.81
#Mann= 3 , 0 , 0
     -10    .033       0       0    .033       0    15.9    .033       0
#XS Ineff= 2 , 0
               0    5.31    15.9            5.11
Permanent Ineff=
       F       F
Bank Sta=0,15.9
XS Rating Curve= 0
Exp/Cntr=.3,.1

Type RM Length L Ch R = 1 ,650.00  ,50,50,50
BEGIN DESCRIPTION:
13
END DESCRIPTION:
#Sta/Elev= 16
   -13.5   10.99   -10.5    9.49    -7.5     7.9    -4.5    6.49    -1.5    4.79
       0    4.79       3    4.49     6.2    3.09     6.6    2.39    12.6    2.39
    13.4    2.69    15.4    3.69    17.4    4.79    19.9    4.79    21.9    2.99
    31.9    2.99
#Mann= 3 , 0 , 0
   -13.5    .033       0       0    .033       0    17.4    .033       0
#XS Ineff= 2 , 0
               0    4.79    17.4            4.79
Permanent Ineff=
       F       F
Bank Sta=0,17.4
XS Rating Curve= 0
Exp/Cntr=.3,.1

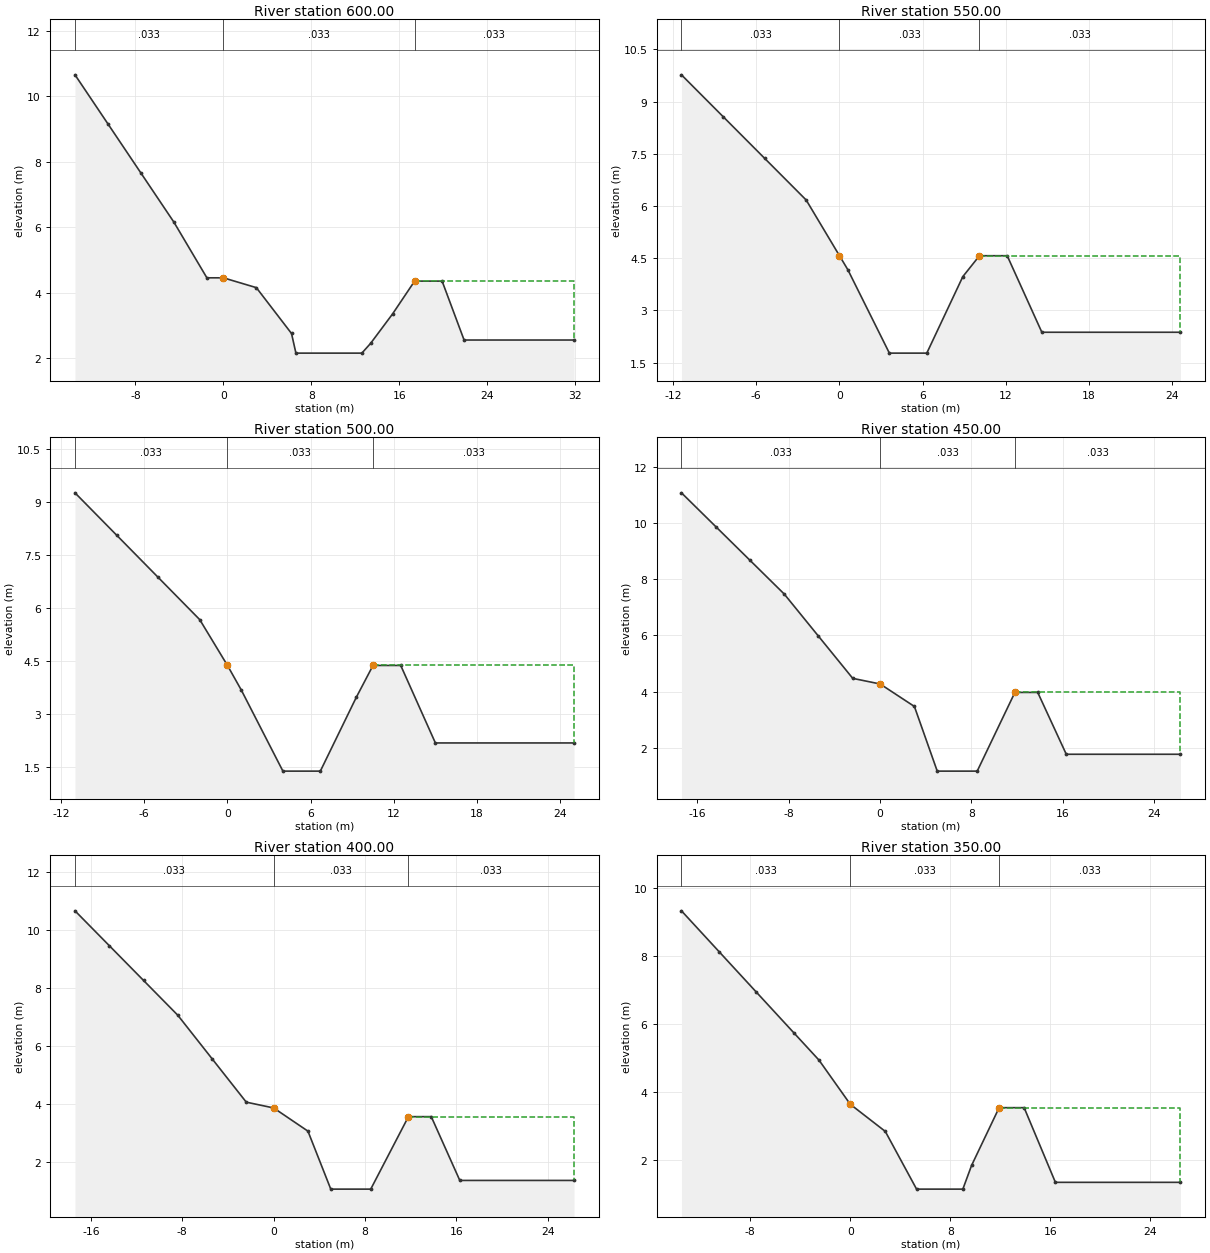
Type RM Length L Ch R = 1 ,600.00  ,50,50,50
BEGIN DESCRIPTION:
12
END DESCRIPTION:
#Sta/Elev= 16
   -13.5   10.65   -10.5    9.15    -7.5    7.65    -4.5    6.15    -1.5    4.45
       0    4.45       3    4.15     6.2    2.75     6.6    2.15    12.6    2.15
    13.4    2.45    15.4    3.35    17.4    4.35    19.9    4.35    21.9    2.55
    31.9    2.55
#Mann= 3 , 0 , 0
   -13.5    .033       0       0    .033       0    17.4    .033       0
#XS Ineff= 2 , 0
               0    4.45    17.4            4.35
Permanent Ineff=
       F       F
Bank Sta=0,17.4
XS Rating Curve= 0
Exp/Cntr=.3,.1

Type RM Length L Ch R = 1 ,550.00  ,50,50,50
BEGIN DESCRIPTION:
11
END DESCRIPTION:
#Sta/Elev= 13
   -11.4    9.77    -8.4    8.57    -5.4    7.37    -2.4    6.17       0    4.57
      .6    4.17     3.6    1.77     6.3    1.77     8.9    3.97    10.1    4.57
    12.1    4.57    14.6    2.37    24.6    2.37
#Mann= 3 , 0 , 0
   -11.4    .033       0       0    .033       0    10.1    .033       0
#XS Ineff= 2 , 0
               0    4.57    10.1            4.57
Permanent Ineff=
       F       F
Bank Sta=0,10.1
XS Rating Curve= 0
Exp/Cntr=.3,.1

Type RM Length L Ch R = 1 ,500.00  ,50,50,50
BEGIN DESCRIPTION:
10
END DESCRIPTION:
#Sta/Elev= 13
     -11    9.27      -8    8.07      -5    6.87      -2    5.67       0    4.37
       1    3.67       4    1.37     6.7    1.37     9.3    3.47    10.5    4.37
    12.5    4.37      15    2.17      25    2.17
#Mann= 3 , 0 , 0
     -11    .033       0       0    .033       0    10.5    .033       0
#XS Ineff= 2 , 0
               0    4.37    10.5            4.37
Permanent Ineff=
       F       F
Bank Sta=0,10.5
XS Rating Curve= 0
Exp/Cntr=.3,.1

Type RM Length L Ch R = 1 ,450.00  ,50,50,50
BEGIN DESCRIPTION:
9
END DESCRIPTION:
#Sta/Elev= 14
   -17.4   11.07   -14.4    9.87   -11.4    8.67    -8.4    7.47    -5.4    5.97
    -2.4    4.47       0    4.27       3    3.47       5    1.17     8.5    1.17
    11.8    3.97    13.8    3.97    16.3    1.77    26.3    1.77
#Mann= 3 , 0 , 0
   -17.4    .033       0       0    .033       0    11.8    .033       0
#XS Ineff= 2 , 0
               0    4.27    11.8            3.97
Permanent Ineff=
       F       F
Bank Sta=0,11.8
XS Rating Curve= 0
Exp/Cntr=.3,.1

Type RM Length L Ch R = 1 ,400.00  ,50,50,50
BEGIN DESCRIPTION:
8
END DESCRIPTION:
#Sta/Elev= 14
   -17.4   10.67   -14.4    9.47   -11.4    8.27    -8.4    7.07    -5.4    5.57
    -2.4    4.07       0    3.87       3    3.07       5    1.07     8.5    1.07
    11.8    3.57    13.8    3.57    16.3    1.37    26.3    1.37
#Mann= 3 , 0 , 0
   -17.4    .033       0       0    .033       0    11.8    .033       0
#XS Ineff= 2 , 0
               0    3.87    11.8            3.57
Permanent Ineff=
       F       F
Bank Sta=0,11.8
XS Rating Curve= 0
Exp/Cntr=.3,.1

Type RM Length L Ch R = 1 ,350.00  ,50,50,50
BEGIN DESCRIPTION:
7
END DESCRIPTION:
#Sta/Elev= 14
   -13.5    9.34   -10.5    8.14    -7.5    6.94    -4.5    5.74    -2.5    4.94
       0    3.64     2.8    2.84     5.3    1.14       9    1.14     9.7    1.84
    11.9    3.54    13.9    3.54    16.4    1.34    26.4    1.34
#Mann= 3 , 0 , 0
   -13.5    .033       0       0    .033       0    11.9    .033       0
#XS Ineff= 2 , 0
               0    3.64    11.9            3.54
Permanent Ineff=
       F       F
Bank Sta=0,11.9
XS Rating Curve= 0
Exp/Cntr=.3,.1

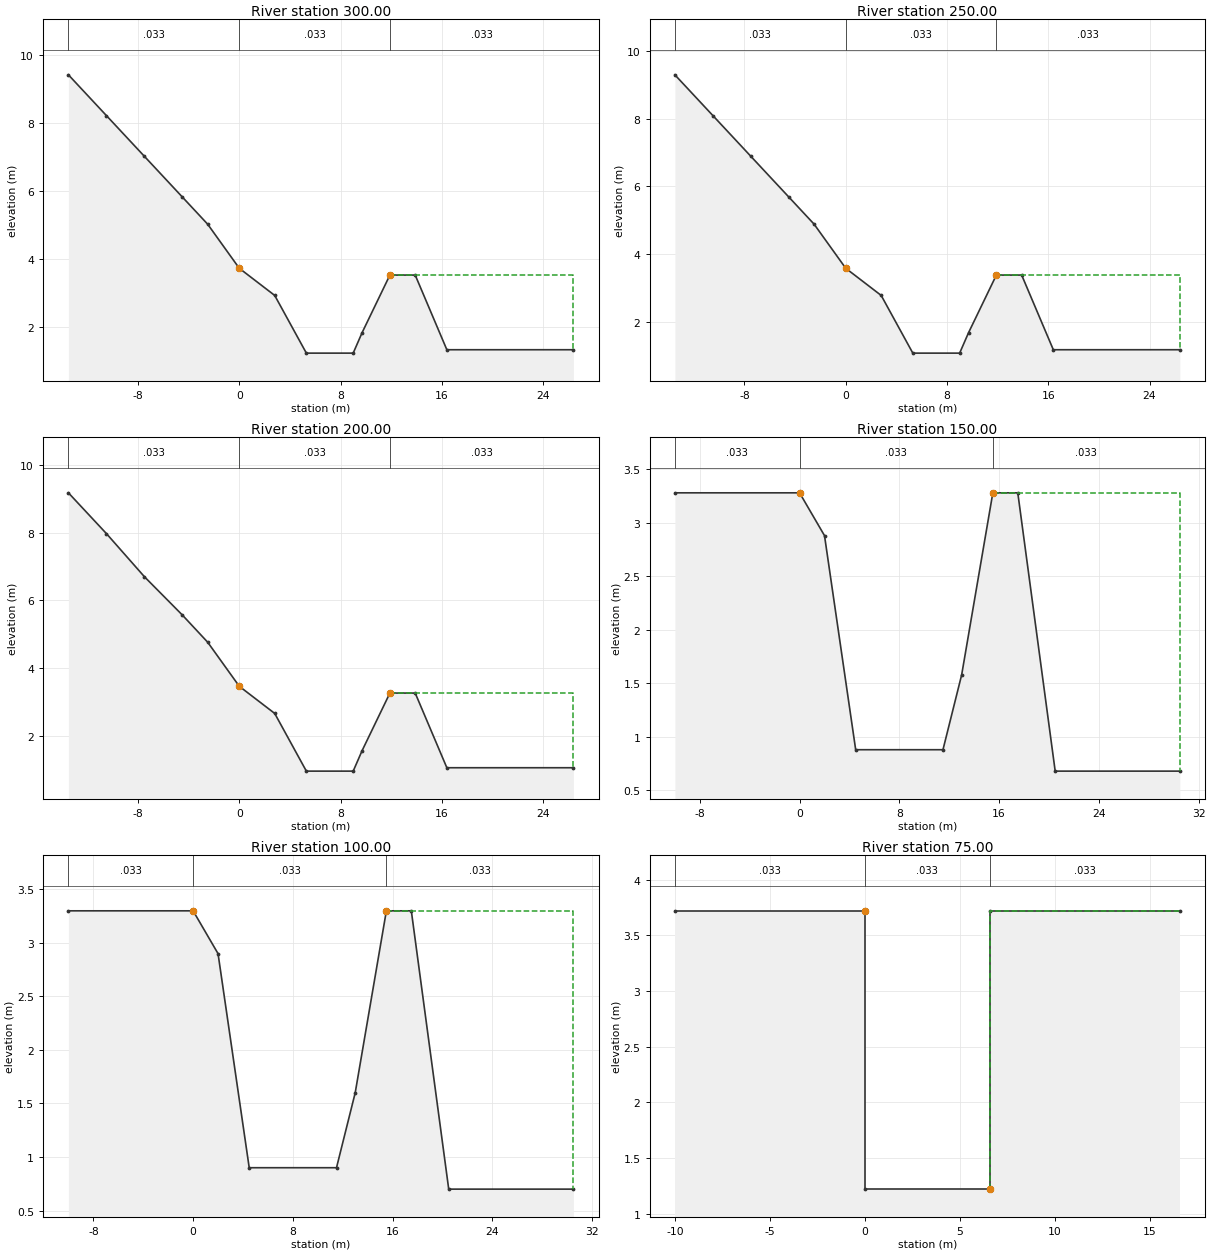
Type RM Length L Ch R = 1 ,300.00  ,50,50,50
BEGIN DESCRIPTION:
6
END DESCRIPTION:
#Sta/Elev= 14
   -13.5    9.42   -10.5    8.22    -7.5    7.02    -4.5    5.82    -2.5    5.02
       0    3.72     2.8    2.92     5.3    1.22       9    1.22     9.7    1.82
    11.9    3.52    13.9    3.52    16.4    1.32    26.4    1.32
#Mann= 3 , 0 , 0
   -13.5    .033       0       0    .033       0    11.9    .033       0
#XS Ineff= 2 , 0
               0    3.72    11.9            3.52
Permanent Ineff=
       F       F
Bank Sta=0,11.9
XS Rating Curve= 0
Exp/Cntr=.3,.1

Type RM Length L Ch R = 1 ,250.00  ,50,50,50
BEGIN DESCRIPTION:
5
END DESCRIPTION:
#Sta/Elev= 14
   -13.5    9.29   -10.5    8.09    -7.5    6.89    -4.5    5.69    -2.5    4.89
       0    3.59     2.8    2.79     5.3    1.09       9    1.09     9.7    1.69
    11.9    3.39    13.9    3.39    16.4    1.19    26.4    1.19
#Mann= 3 , 0 , 0
   -13.5    .033       0       0    .033       0    11.9    .033       0
#XS Ineff= 2 , 0
               0    3.59    11.9            3.39
Permanent Ineff=
       F       F
Bank Sta=0,11.9
XS Rating Curve= 0
Exp/Cntr=.3,.1

Type RM Length L Ch R = 1 ,200.00  ,50,50,50
BEGIN DESCRIPTION:
4
END DESCRIPTION:
#Sta/Elev= 14
   -13.5    9.17   -10.5    7.97    -7.5     6.7    -4.5    5.57    -2.5    4.77
       0    3.47     2.8    2.67     5.3     .97       9     .97     9.7    1.57
    11.9    3.27    13.9    3.27    16.4    1.07    26.4    1.07
#Mann= 3 , 0 , 0
   -13.5    .033       0       0    .033       0    11.9    .033       0
#XS Ineff= 2 , 0
               0    3.47    11.9            3.27
Permanent Ineff=
       F       F
Bank Sta=0,11.9
XS Rating Curve= 0
Exp/Cntr=.3,.1

Type RM Length L Ch R = 1 ,150.00  ,50,50,50
BEGIN DESCRIPTION:
3
END DESCRIPTION:
#Sta/Elev= 10
     -10    3.28       0    3.28       2    2.88     4.5     .88    11.5     .88
      13    1.58    15.5    3.28    17.5    3.28    20.5     .68    30.5     .68
#Mann= 3 , 0 , 0
     -10    .033       0       0    .033       0    15.5    .033       0
#XS Ineff= 2 , 0
               0    3.28    15.5            3.28
Permanent Ineff=
       F       F
Bank Sta=0,15.5
XS Rating Curve= 0
Exp/Cntr=.3,.1

Type RM Length L Ch R = 1 ,100.00  ,25,25,25
BEGIN DESCRIPTION:
2
END DESCRIPTION:
#Sta/Elev= 10
     -10     3.3       0     3.3       2     2.9     4.5      .9    11.5      .9
      13     1.6    15.5     3.3    17.5     3.3    20.5      .7    30.5      .7
#Mann= 3 , 0 , 0
     -10    .033       0       0    .033       0    15.5    .033       0
#XS Ineff= 2 , 0
               0     3.3    15.5             3.3
Permanent Ineff=
       F       F
Bank Sta=0,15.5
XS Rating Curve= 0
Exp/Cntr=.3,.1

Type RM Length L Ch R = 1 ,75.00   ,25,25,25
BEGIN DESCRIPTION:
1.025
END DESCRIPTION:
#Sta/Elev= 6
     -10    3.72       0    3.72       0    1.22     6.6    1.22     6.6    3.72
    16.6    3.72
#Mann= 3 , 0 , 0
     -10    .033       0       0    .033       0     6.6    .033       0
#XS Ineff= 2 , 0
               0    3.72     6.6            3.72
Permanent Ineff=
       F       F
Bank Sta=0,6.6
XS Rating Curve= 0
Exp/Cntr=.3,.1

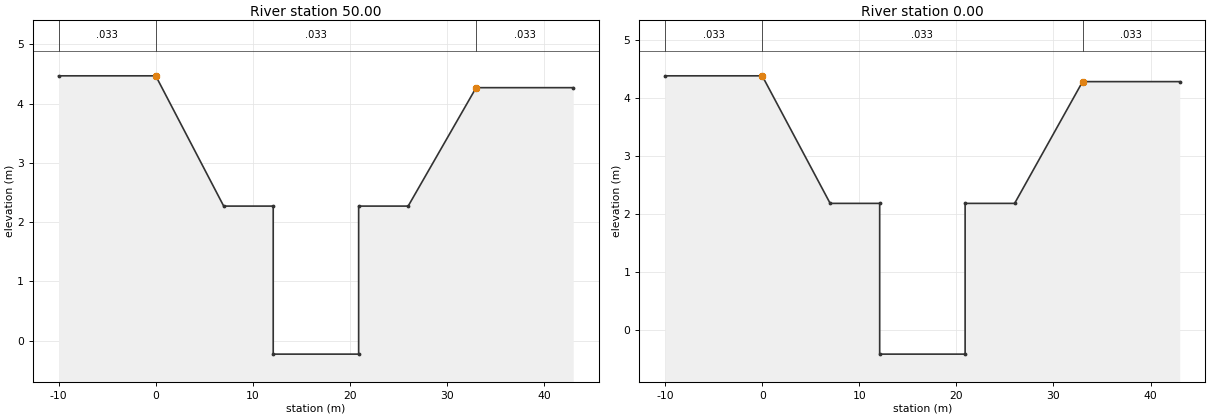
Type RM Length L Ch R = 1 ,50.00   ,50,50,50
BEGIN DESCRIPTION:
1
END DESCRIPTION:
#Sta/Elev= 10
     -10    4.47       0    4.47       7    2.27    12.1    2.27    12.1    -.23
    20.9    -.23    20.9    2.27      26    2.27      33    4.27      43    4.27
#Mann= 3 , 0 , 0
     -10    .033       0       0    .033       0      33    .033       0
#XS Ineff= 2 , 0
               0    4.47      33            4.27
Permanent Ineff=
       F       F
Bank Sta=0,33
XS Rating Curve= 0
Exp/Cntr=.3,.1

Type RM Length L Ch R = 1 ,0.00    ,0,0,0
BEGIN DESCRIPTION:
0
END DESCRIPTION:
#Sta/Elev= 10
     -10    4.39       0    4.39       7    2.19    12.1    2.19    12.1    -.41
    20.9    -.41    20.9    2.19      26    2.19      33    4.29      43    4.29
#Mann= 3 , 0 , 0
     -10    .033       0       0    .033       0      33    .033       0
#XS Ineff= 2 , 0
               0    4.39      33            4.29
Permanent Ineff=
       F       F
Bank Sta=0,33
XS Rating Curve= 0
Exp/Cntr=.3,.1

Chan Stop Cuts=-1