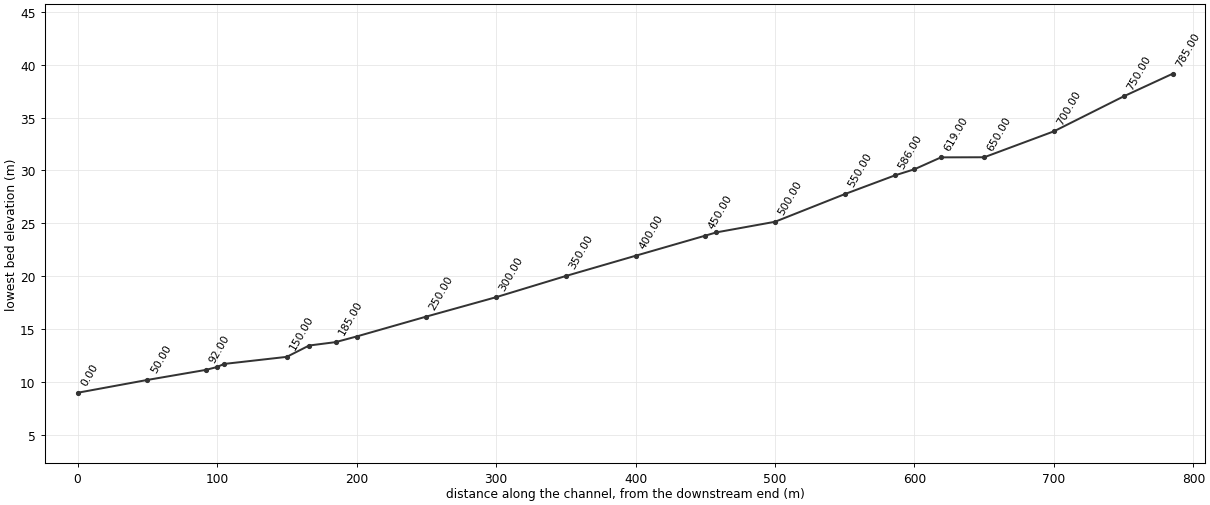
--- CHANG.prj (project) ---

Proj Title=CHANG
Current Plan=p01
Default Exp/Contr=.3,.1
SI Units
Geom File=g01
Flow File=f01
Plan File=p01
Y Axis Title=Elevation
X Axis Title(PF)=Main Channel Distance
X Axis Title(XS)=Station
BEGIN DESCRIPTION:
           BACK WATER COMPUTATION
      APPLICATION OF HEC-2 BY Samju Construction Engineering
      CANGCHON-STREEM : 30 YR
END DESCRIPTION:
DSS Export Rating Curves= 0
DSS Export Rating Curve Sorted= 0
DSS Export Volume Flow Curves= 0
DXF OffsetX= 0
DXF OffsetY= 0
DXF ScaleX= 1
DXF ScaleY= 10

--- CHANG.p01 (plan) ---

Plan Title=Imported Plan 01
Version=Version 3.0.1  Mar 2001
Short Identifier=Imported Pla
Geom File=g01
Flow File=f01
Subcritical Flow
K Sum by GR= 0
Std Step Tol= 0.003
Critical Tol= 0.003
Num of Std Step Trials= 20
Max Error Tol= 0.1
Flow Tol Ratio= 0.001
Split Flow NTrial= 30
Split Flow Tol= 0.02
Split Flow Ratio= 0.02
Log Output Level= 0
Friction Slope Method= 1
Unsteady Friction Slope Method= 2
Parabolic Critical Depth
Global Vel Dist= 0 , 0 , 0
Global Log Level= 0
CheckData=True
Encroach Param=-1 ,0,0, 0
Computation Interval=1HOUR
Output Interval=1HOUR
Run HTab= 0
Run UNet= 0
Run PostProcess= 0
UNET Theta= 1
UNET ZTol= 0.02
UNET ZSATol= 0.1
UNET MxIter= 20
UNET MaxInSteps= 20
UNET DtIC= 0
UNET DtMin= 0
UNET MaxCRTS= 20
UNET WFStab= 2
UNET SFStab= 1
UNET WFX= 1
UNET SFX= 1
UNET Convert EG Bridges=-1
UNET Use Existing IB Tables=-1
Instantaneous Interval=1HOUR
Write IC File= 0
Write Velocity= 0
Write Detailed= 0

--- CHANG.f01 (steady flow) ---

Flow Title=Imported Flow 01
Version=Version 3.0.1  Mar 2001
Number of Profiles= 5
Profile Names=10YR,20YR,30YR,50YR,80YR
River Rch & RM=RIVER-1,Reach-1         ,785.00
    5.24    5.77    6.08    6.47    6.83
Boundary for River Rch & Prof#=RIVER-1,Reach-1         , 1
Up Type= 0
Dn Type= 3
Dn Slope=.034
Boundary for River Rch & Prof#=RIVER-1,Reach-1         , 2
Up Type= 0
Dn Type= 3
Dn Slope=.034
Boundary for River Rch & Prof#=RIVER-1,Reach-1         , 3
Up Type= 0
Dn Type= 3
Dn Slope=.034
Boundary for River Rch & Prof#=RIVER-1,Reach-1         , 4
Up Type= 0
Dn Type= 3
Dn Slope=.034
Boundary for River Rch & Prof#=RIVER-1,Reach-1         , 5
Up Type= 0
Dn Type= 3
Dn Slope=.034
DSS Import GetInterval= 0
DSS Import GetPeak= 0
DSS Import FillOption= 0

--- CHANG.g01 (geometry) ---

Geom Title=Imported Geom 01
Version=Version 3.0.1  Mar 2001

River Reach=RIVER-1         ,Reach-1
Reach XY= 2
              .5             .95              .5             .05

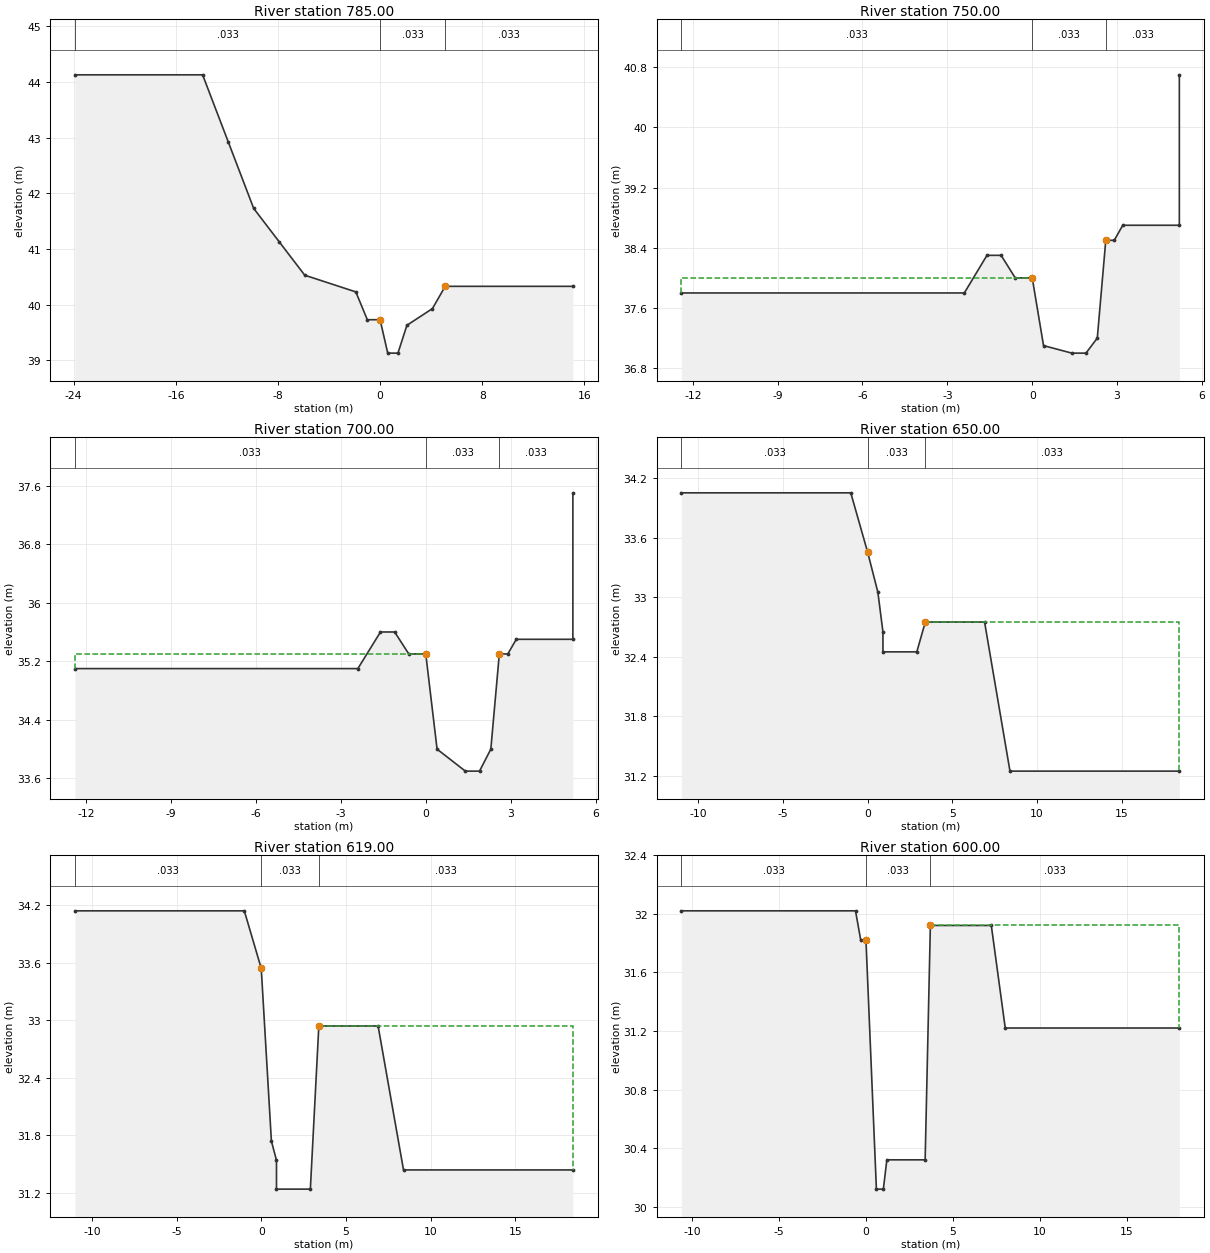
Type RM Length L Ch R = 1 ,785.00  ,35,35,35
BEGIN DESCRIPTION:
15.035
END DESCRIPTION:
#Sta/Elev= 15
   -23.9   44.13   -13.9   44.13   -11.9   42.93    -9.9   41.73    -7.9   41.13
    -5.9   40.53    -1.9   40.23      -1   39.73       0   39.73      .6   39.13
     1.4   39.13     2.1   39.63     4.1   39.93     5.1   40.33    15.1   40.33
#Mann= 3 , 0 , 0
   -23.9    .033       0       0    .033       0     5.1    .033       0
#XS Ineff= 2 , 0
               0   39.73     5.1           40.33
Permanent Ineff=
       F       F
Bank Sta=0,5.1
XS Rating Curve= 0
Exp/Cntr=.3,.1

Type RM Length L Ch R = 1 ,750.00  ,50,50,50
BEGIN DESCRIPTION:
15
END DESCRIPTION:
#Sta/Elev= 15
   -12.4    37.8    -2.4    37.8    -1.6    38.3    -1.1    38.3     -.6      38
       0      38      .4    37.1     1.4      37     1.9      37     2.3    37.2
     2.6    38.5     2.9    38.5     3.2    38.7     5.2    38.7     5.2    40.7
#Mann= 3 , 0 , 0
   -12.4    .033       0       0    .033       0     2.6    .033       0
#XS Ineff= 2 , 0
               0      38     2.6            38.5
Permanent Ineff=
       F       F
Bank Sta=0,2.6
XS Rating Curve= 0
Exp/Cntr=.3,.1

Type RM Length L Ch R = 1 ,700.00  ,50,50,50
BEGIN DESCRIPTION:
14
END DESCRIPTION:
#Sta/Elev= 15
   -12.4    35.1    -2.4    35.1    -1.6    35.6    -1.1    35.6     -.6    35.3
       0    35.3      .4      34     1.4    33.7     1.9    33.7     2.3      34
     2.6    35.3     2.9    35.3     3.2    35.5     5.2    35.5     5.2    37.5
#Mann= 3 , 0 , 0
   -12.4    .033       0       0    .033       0     2.6    .033       0
#XS Ineff= 2 , 0
               0    35.3     2.6            35.3
Permanent Ineff=
       F       F
Bank Sta=0,2.6
XS Rating Curve= 0
Exp/Cntr=.3,.1

Type RM Length L Ch R = 1 ,650.00  ,31,31,31
BEGIN DESCRIPTION:
13
END DESCRIPTION:
#Sta/Elev= 11
     -11   34.05      -1   34.05       0   33.45      .6   33.05      .9   32.65
      .9   32.45     2.9   32.45     3.4   32.75     6.9   32.75     8.4   31.25
    18.4   31.25
#Mann= 3 , 0 , 0
     -11    .033       0       0    .033       0     3.4    .033       0
#XS Ineff= 2 , 0
               0   33.45     3.4           32.75
Permanent Ineff=
       F       F
Bank Sta=0,3.4
XS Rating Curve= 0
Exp/Cntr=.3,.1

Type RM Length L Ch R = 1 ,619.00  ,19,19,19
BEGIN DESCRIPTION:
12.019
END DESCRIPTION:
#Sta/Elev= 11
     -11   34.14      -1   34.14       0   33.54      .6   31.74      .9   31.54
      .9   31.24     2.9   31.24     3.4   32.94     6.9   32.94     8.4   31.44
    18.4   31.44
#Mann= 3 , 0 , 0
     -11    .033       0       0    .033       0     3.4    .033       0
#XS Ineff= 2 , 0
               0   33.54     3.4           32.94
Permanent Ineff=
       F       F
Bank Sta=0,3.4
XS Rating Curve= 0
Exp/Cntr=.3,.1

Type RM Length L Ch R = 1 ,600.00  ,14,14,14
BEGIN DESCRIPTION:
12
END DESCRIPTION:
#Sta/Elev= 12
   -10.6   32.02     -.6   32.02     -.3   31.82       0   31.82      .6   30.12
       1   30.12     1.2   30.32     3.4   30.32     3.7   31.92     7.2   31.92
       8   31.22      18   31.22
#Mann= 3 , 0 , 0
   -10.6    .033       0       0    .033       0     3.7    .033       0
#XS Ineff= 2 , 0
               0   31.82     3.7           31.92
Permanent Ineff=
       F       F
Bank Sta=0,3.7
XS Rating Curve= 0
Exp/Cntr=.3,.1

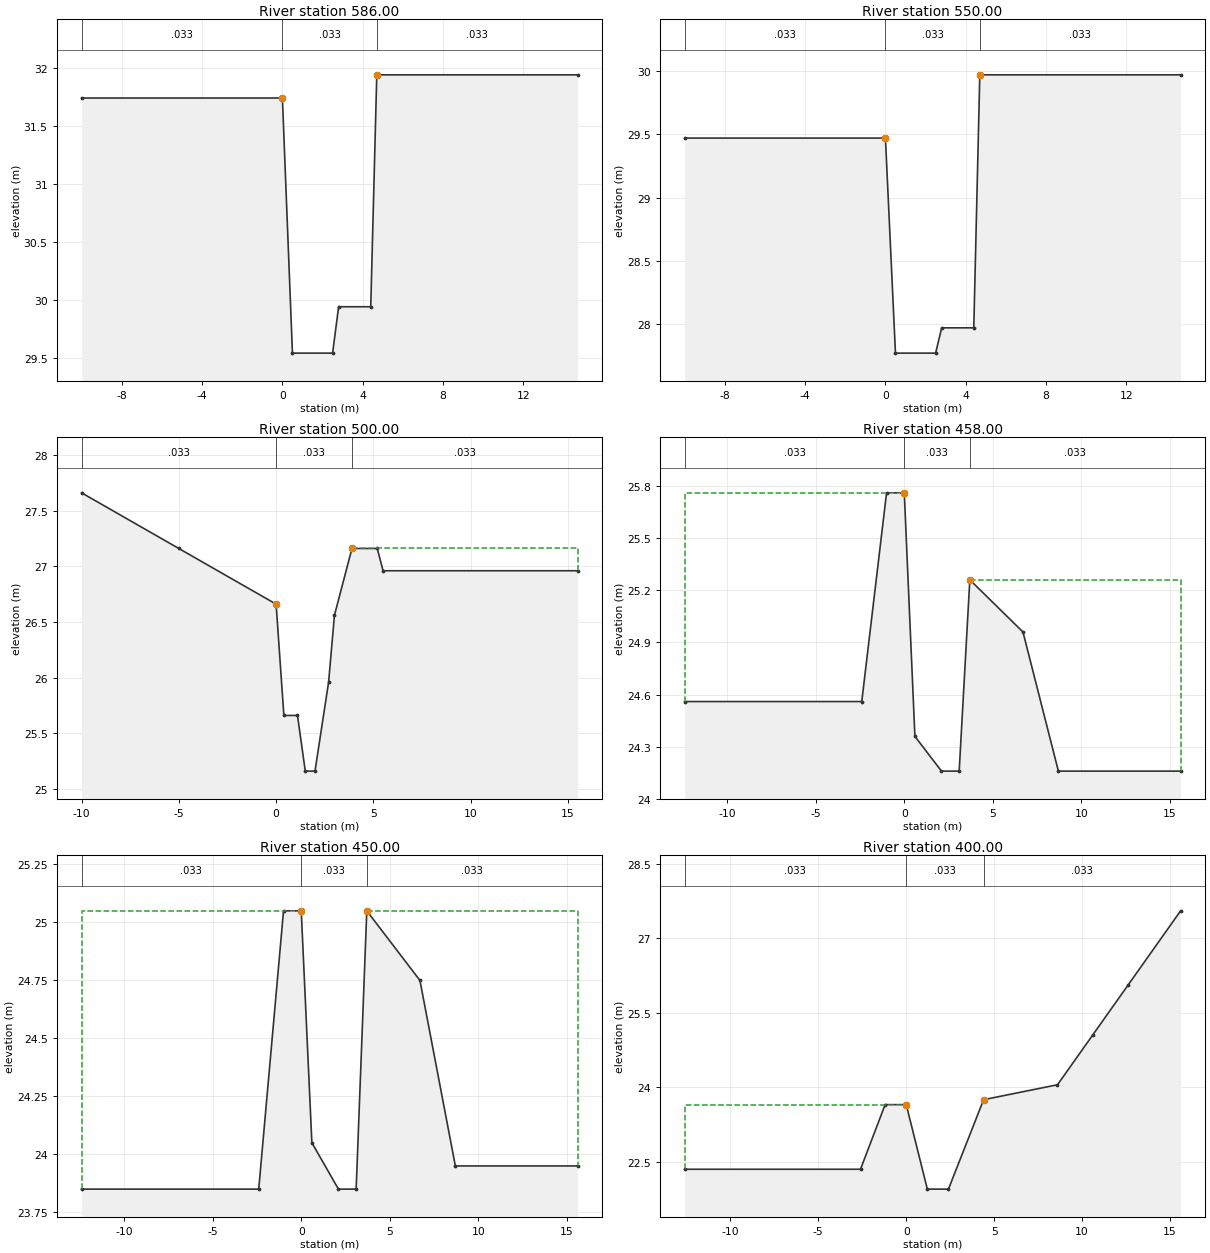
Type RM Length L Ch R = 1 ,586.00  ,36,36,36
BEGIN DESCRIPTION:
11.036
END DESCRIPTION:
#Sta/Elev= 8
     -10   31.74       0   31.74      .5   29.54     2.5   29.54     2.8   29.94
     4.4   29.94     4.7   31.94    14.7   31.94
#Mann= 3 , 0 , 0
     -10    .033       0       0    .033       0     4.7    .033       0
#XS Ineff= 2 , 0
               0   31.74     4.7           31.94
Permanent Ineff=
       F       F
Bank Sta=0,4.7
XS Rating Curve= 0
Exp/Cntr=.3,.1

Type RM Length L Ch R = 1 ,550.00  ,50,50,50
BEGIN DESCRIPTION:
11
END DESCRIPTION:
#Sta/Elev= 8
     -10   29.47       0   29.47      .5   27.77     2.5   27.77     2.8   27.97
     4.4   27.97     4.7   29.97    14.7   29.97
#Mann= 3 , 0 , 0
     -10    .033       0       0    .033       0     4.7    .033       0
#XS Ineff= 2 , 0
               0   29.47     4.7           29.97
Permanent Ineff=
       F       F
Bank Sta=0,4.7
XS Rating Curve= 0
Exp/Cntr=.3,.1

Type RM Length L Ch R = 1 ,500.00  ,42,42,42
BEGIN DESCRIPTION:
10
END DESCRIPTION:
#Sta/Elev= 13
     -10   27.66      -5   27.16       0   26.66      .4   25.66     1.1   25.66
     1.5   25.16       2   25.16     2.7   25.96       3   26.56     3.9   27.16
     5.2   27.16     5.5   26.96    15.5   26.96
#Mann= 3 , 0 , 0
     -10    .033       0       0    .033       0     3.9    .033       0
#XS Ineff= 2 , 0
               0   26.66     3.9           27.16
Permanent Ineff=
       F       F
Bank Sta=0,3.9
XS Rating Curve= 0
Exp/Cntr=.3,.1

Type RM Length L Ch R = 1 ,458.00  ,8,8,8
BEGIN DESCRIPTION:
9.008
END DESCRIPTION:
#Sta/Elev= 11
   -12.4   24.56    -2.4   24.56      -1   25.76       0   25.76      .6   24.36
     2.1   24.16     3.1   24.16     3.7   25.26     6.7   24.96     8.7   24.16
    15.6   24.16
#Mann= 3 , 0 , 0
   -12.4    .033       0       0    .033       0     3.7    .033       0
#XS Ineff= 2 , 0
               0   25.76     3.7           25.26
Permanent Ineff=
       F       F
Bank Sta=0,3.7
XS Rating Curve= 0
Exp/Cntr=.3,.1

Type RM Length L Ch R = 1 ,450.00  ,50,50,50
BEGIN DESCRIPTION:
9
END DESCRIPTION:
#Sta/Elev= 11
   -12.4   23.85    -2.4   23.85      -1   25.05       0   25.05      .6   24.05
     2.1   23.85     3.1   23.85     3.7   25.05     6.7   24.75     8.7   23.95
    15.6   23.95
#Mann= 3 , 0 , 0
   -12.4    .033       0       0    .033       0     3.7    .033       0
#XS Ineff= 2 , 0
               0   25.05     3.7           25.05
Permanent Ineff=
       F       F
Bank Sta=0,3.7
XS Rating Curve= 0
Exp/Cntr=.3,.1

Type RM Length L Ch R = 1 ,400.00  ,50,50,50
BEGIN DESCRIPTION:
8
END DESCRIPTION:
#Sta/Elev= 11
   -12.6   22.35    -2.6   22.35    -1.2   23.65       0   23.65     1.2   21.95
     2.4   21.95     4.4   23.75     8.6   24.05    10.6   25.05    12.6   26.05
    15.6   27.55
#Mann= 3 , 0 , 0
   -12.6    .033       0       0    .033       0     4.4    .033       0
#XS Ineff= 2 , 0
               0   23.65     4.4           23.75
Permanent Ineff=
       F       F
Bank Sta=0,4.4
XS Rating Curve= 0
Exp/Cntr=.3,.1

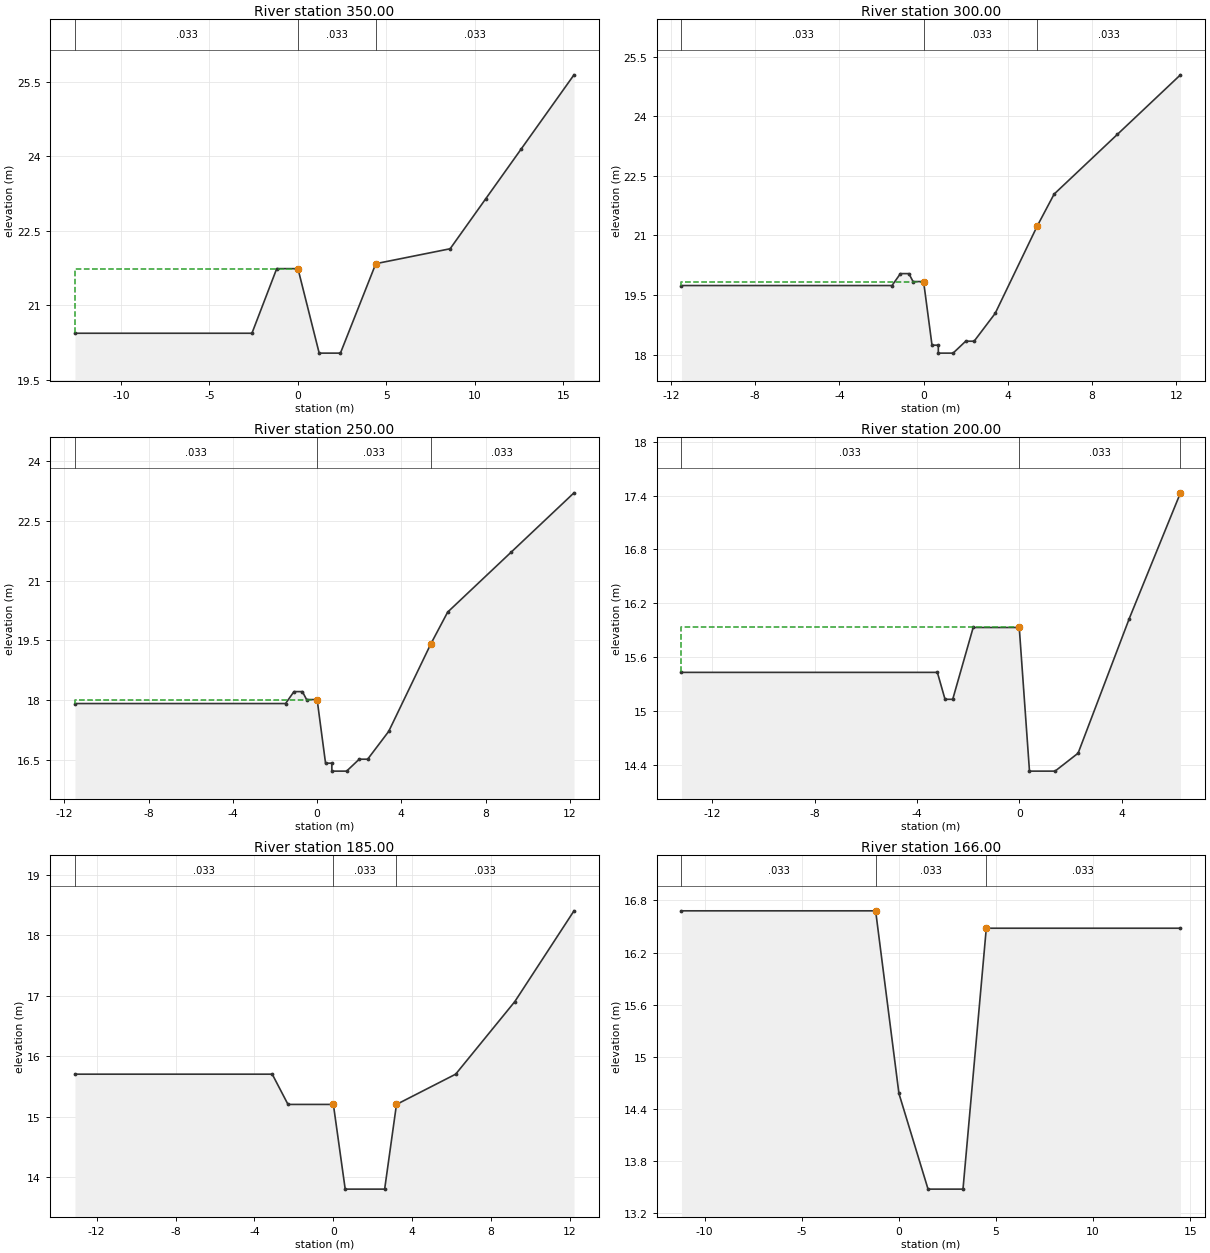
Type RM Length L Ch R = 1 ,350.00  ,50,50,50
BEGIN DESCRIPTION:
7
END DESCRIPTION:
#Sta/Elev= 11
   -12.6   20.44    -2.6   20.44    -1.2   21.74       0   21.74     1.2   20.04
     2.4   20.04     4.4   21.84     8.6   22.14    10.6   23.14    12.6   24.14
    15.6   25.64
#Mann= 3 , 0 , 0
   -12.6    .033       0       0    .033       0     4.4    .033       0
#XS Ineff= 2 , 0
               0   21.74     4.4           21.84
Permanent Ineff=
       F       F
Bank Sta=0,4.4
XS Rating Curve= 0
Exp/Cntr=.3,.1

Type RM Length L Ch R = 1 ,300.00  ,50,50,50
BEGIN DESCRIPTION:
6
END DESCRIPTION:
#Sta/Elev= 17
   -11.5   19.74    -1.5   19.74    -1.1   20.04     -.7   20.04     -.5   19.84
       0   19.84      .4   18.24      .7   18.24      .7   18.04     1.4   18.04
       2   18.34     2.4   18.34     3.4   19.04     5.4   21.24     6.2   22.04
     9.2   23.54    12.2   25.04
#Mann= 3 , 0 , 0
   -11.5    .033       0       0    .033       0     5.4    .033       0
#XS Ineff= 2 , 0
               0   19.84     5.4           21.24
Permanent Ineff=
       F       F
Bank Sta=0,5.4
XS Rating Curve= 0
Exp/Cntr=.3,.1

Type RM Length L Ch R = 1 ,250.00  ,50,50,50
BEGIN DESCRIPTION:
5
END DESCRIPTION:
#Sta/Elev= 17
   -11.5   17.91    -1.5   17.91    -1.1   18.21     -.7   18.21     -.5   18.01
       0   18.01      .4   16.41      .7   16.41      .7   16.21     1.4   16.21
       2   16.51     2.4   16.51     3.4   17.21     5.4   19.41     6.2   20.21
     9.2   21.71    12.2   23.21
#Mann= 3 , 0 , 0
   -11.5    .033       0       0    .033       0     5.4    .033       0
#XS Ineff= 2 , 0
               0   18.01     5.4           19.41
Permanent Ineff=
       F       F
Bank Sta=0,5.4
XS Rating Curve= 0
Exp/Cntr=.3,.1

Type RM Length L Ch R = 1 ,200.00  ,15,15,15
BEGIN DESCRIPTION:
4
END DESCRIPTION:
#Sta/Elev= 11
   -13.2   15.43    -3.2   15.43    -2.9   15.13    -2.6   15.13    -1.8   15.93
       0   15.93      .4   14.33     1.4   14.33     2.3   14.53     4.3   16.03
     6.3   17.43
#Mann= 3 , 0 , 0
   -13.2    .033       0       0    .033       0     6.3    .033       0
#XS Ineff= 2 , 0
               0   15.93     6.3           17.43
Permanent Ineff=
       F       F
Bank Sta=0,6.3
XS Rating Curve= 0
Exp/Cntr=.3,.1

Type RM Length L Ch R = 1 ,185.00  ,19,19,19
BEGIN DESCRIPTION:
3.035
END DESCRIPTION:
#Sta/Elev= 10
   -13.1    15.7    -3.1    15.7    -2.3    15.2       0    15.2      .6    13.8
     2.6    13.8     3.2    15.2     6.2    15.7     9.2    16.9    12.2    18.4
#Mann= 3 , 0 , 0
   -13.1    .033       0       0    .033       0     3.2    .033       0
#XS Ineff= 2 , 0
               0    15.2     3.2            15.2
Permanent Ineff=
       F       F
Bank Sta=0,3.2
XS Rating Curve= 0
Exp/Cntr=.3,.1

Type RM Length L Ch R = 1 ,166.00  ,16,16,16
BEGIN DESCRIPTION:
3.016
END DESCRIPTION:
#Sta/Elev= 7
   -11.2   16.68    -1.2   16.68       0   14.58     1.5   13.48     3.3   13.48
     4.5   16.48    14.5   16.48
#Mann= 3 , 0 , 0
   -11.2    .033       0    -1.2    .033       0     4.5    .033       0
#XS Ineff= 2 , 0
            -1.2   16.68     4.5           16.48
Permanent Ineff=
       F       F
Bank Sta=-1.2,4.5
XS Rating Curve= 0
Exp/Cntr=.3,.1

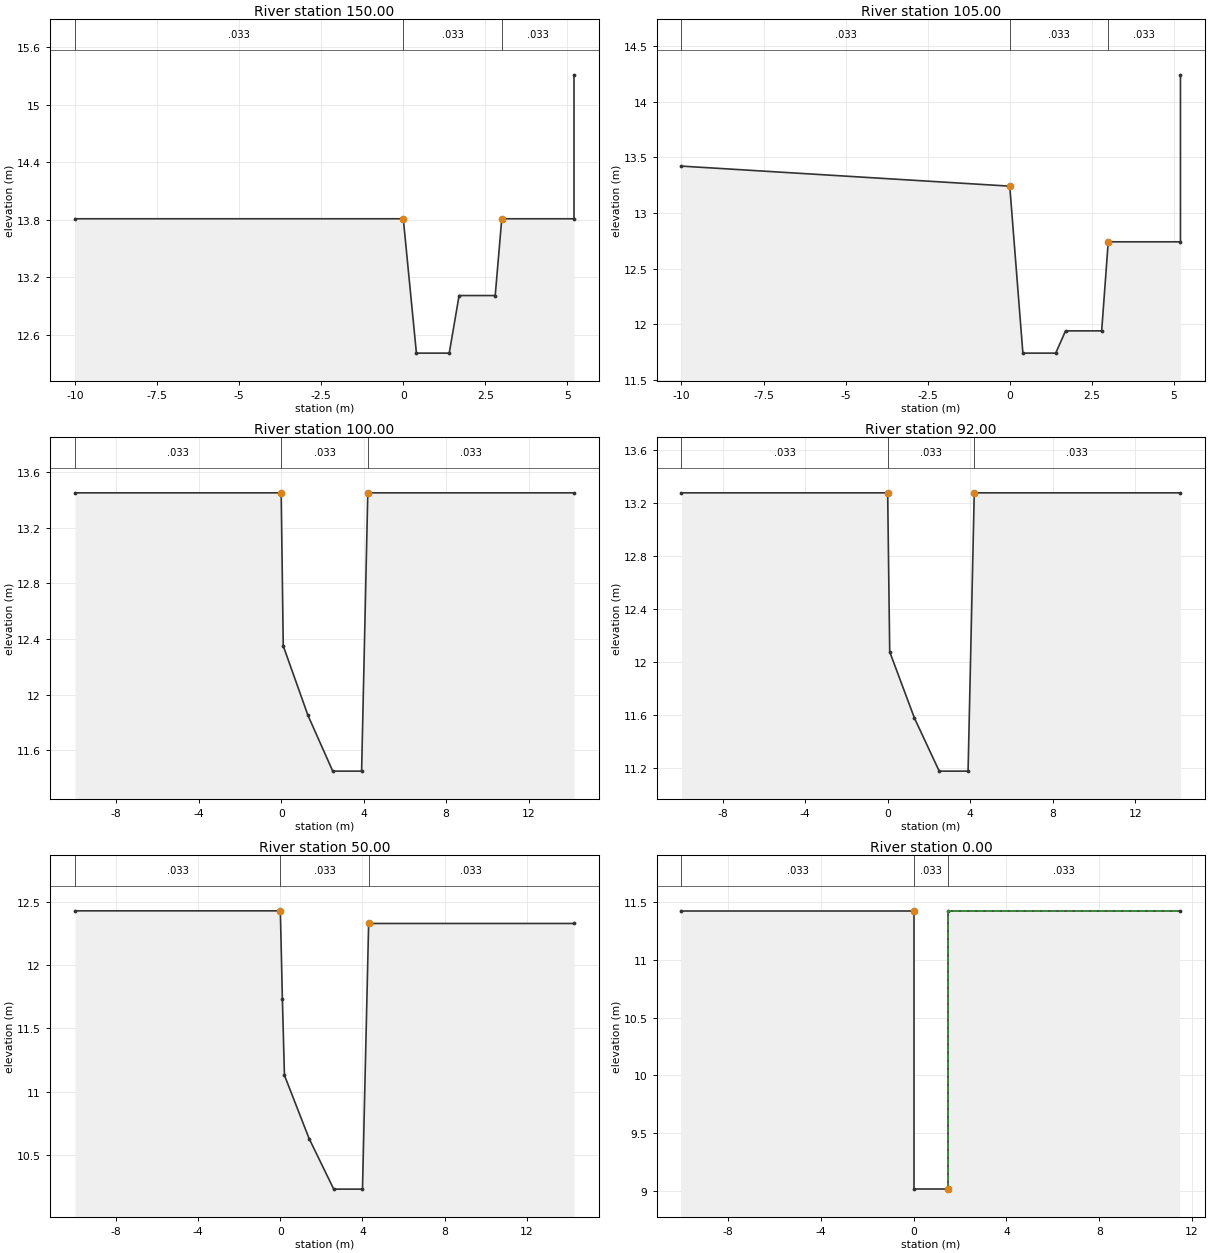
Type RM Length L Ch R = 1 ,150.00  ,45,45,45
BEGIN DESCRIPTION:
3
END DESCRIPTION:
#Sta/Elev= 9
     -10   13.81       0   13.81      .4   12.41     1.4   12.41     1.7   13.01
     2.8   13.01       3   13.81     5.2   13.81     5.2   15.31
#Mann= 3 , 0 , 0
     -10    .033       0       0    .033       0       3    .033       0
#XS Ineff= 2 , 0
               0   13.81       3           13.81
Permanent Ineff=
       F       F
Bank Sta=0,3
XS Rating Curve= 0
Exp/Cntr=.3,.1

Type RM Length L Ch R = 1 ,105.00  ,5,5,5
BEGIN DESCRIPTION:
2.005
END DESCRIPTION:
#Sta/Elev= 9
     -10   13.42       0   13.24      .4   11.74     1.4   11.74     1.7   11.94
     2.8   11.94       3   12.74     5.2   12.74     5.2   14.24
#Mann= 3 , 0 , 0
     -10    .033       0       0    .033       0       3    .033       0
#XS Ineff= 2 , 0
               0   13.24       3           12.74
Permanent Ineff=
       F       F
Bank Sta=0,3
XS Rating Curve= 0
Exp/Cntr=.3,.1

Type RM Length L Ch R = 1 ,100.00  ,8,8,8
BEGIN DESCRIPTION:
2
END DESCRIPTION:
#Sta/Elev= 8
     -10   13.45       0   13.45      .1   12.35     1.3   11.85     2.5   11.45
     3.9   11.45     4.2   13.45    14.2   13.45
#Mann= 3 , 0 , 0
     -10    .033       0       0    .033       0     4.2    .033       0
#XS Ineff= 2 , 0
               0   13.45     4.2           13.45
Permanent Ineff=
       F       F
Bank Sta=0,4.2
XS Rating Curve= 0
Exp/Cntr=.3,.1

Type RM Length L Ch R = 1 ,92.00   ,42,42,42
BEGIN DESCRIPTION:
1.042
END DESCRIPTION:
#Sta/Elev= 8
     -10   13.28       0   13.28      .1   12.08     1.3   11.58     2.5   11.18
     3.9   11.18     4.2   13.28    14.2   13.28
#Mann= 3 , 0 , 0
     -10    .033       0       0    .033       0     4.2    .033       0
#XS Ineff= 2 , 0
               0   13.28     4.2           13.28
Permanent Ineff=
       F       F
Bank Sta=0,4.2
XS Rating Curve= 0
Exp/Cntr=.3,.1

Type RM Length L Ch R = 1 ,50.00   ,50,50,50
BEGIN DESCRIPTION:
1
END DESCRIPTION:
#Sta/Elev= 9
     -10   12.43       0   12.43      .1   11.73      .2   11.13     1.4   10.63
     2.6   10.23       4   10.23     4.3   12.33    14.3   12.33
#Mann= 3 , 0 , 0
     -10    .033       0       0    .033       0     4.3    .033       0
#XS Ineff= 2 , 0
               0   12.43     4.3           12.33
Permanent Ineff=
       F       F
Bank Sta=0,4.3
XS Rating Curve= 0
Exp/Cntr=.3,.1

Type RM Length L Ch R = 1 ,0.00    ,0,0,0
BEGIN DESCRIPTION:
0
END DESCRIPTION:
#Sta/Elev= 6
     -10   11.42       0   11.42       0    9.02     1.5    9.02     1.5   11.42
    11.5   11.42
#Mann= 3 , 0 , 0
     -10    .033       0       0    .033       0     1.5    .033       0
#XS Ineff= 2 , 0
               0   11.42     1.5           11.42
Permanent Ineff=
       F       F
Bank Sta=0,1.5
XS Rating Curve= 0
Exp/Cntr=.3,.1

Chan Stop Cuts=-1