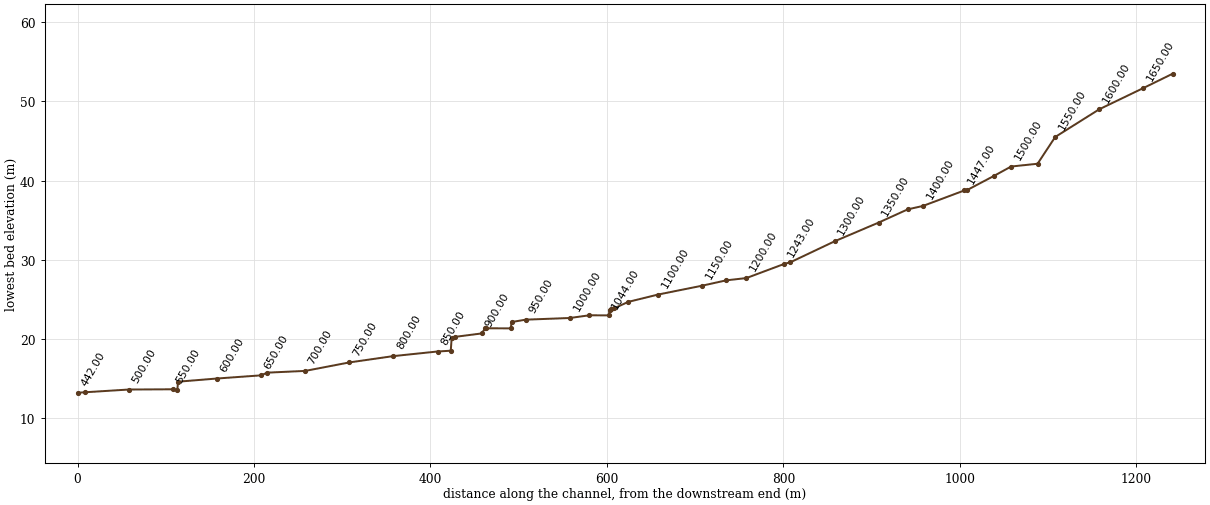
--- NAM.prj (project) ---

Proj Title=NAMJUN
Current Plan=p01
Default Exp/Contr=.3,.1
SI Units
Geom File=g01
Flow File=f01
Plan File=p01
Y Axis Title=Elevation
X Axis Title(PF)=Main Channel Distance
X Axis Title(XS)=Station
BEGIN DESCRIPTION:
           BACK WATER COMPUTATION
      APPLICATION OF HEC-2 BY Samju Construction Engineering
      NAMJUN-STREEM : 30 YR
END DESCRIPTION:
DSS Export Rating Curves= 0
DSS Export Rating Curve Sorted= 0
DSS Export Volume Flow Curves= 0
DXF OffsetX= 0
DXF OffsetY= 0
DXF ScaleX= 1
DXF ScaleY= 10

--- NAM.p01 (plan) ---

Plan Title=Imported Plan 01
Version=Version 3.0.1  Mar 2001
Short Identifier=Imported Pla
Geom File=g01
Flow File=f01
Subcritical Flow
K Sum by GR= 0
Std Step Tol= 0.003
Critical Tol= 0.003
Num of Std Step Trials= 20
Max Error Tol= 0.1
Flow Tol Ratio= 0.001
Split Flow NTrial= 30
Split Flow Tol= 0.02
Split Flow Ratio= 0.02
Log Output Level= 0
Friction Slope Method= 1
Unsteady Friction Slope Method= 2
Parabolic Critical Depth
Global Vel Dist= 0 , 0 , 0
Global Log Level= 0
CheckData=True
Encroach Param=-1 ,0,0, 0
Computation Interval=1HOUR
Output Interval=1HOUR
Run HTab= 0
Run UNet= 0
Run PostProcess= 0
UNET Theta= 1
UNET ZTol= 0.02
UNET ZSATol= 0.1
UNET MxIter= 20
UNET MaxInSteps= 20
UNET DtIC= 0
UNET DtMin= 0
UNET MaxCRTS= 20
UNET WFStab= 2
UNET SFStab= 1
UNET WFX= 1
UNET SFX= 1
UNET Convert EG Bridges=-1
UNET Use Existing IB Tables=-1
Instantaneous Interval=1HOUR
Write IC File= 0
Write Velocity= 0
Write Detailed= 0

--- NAM.f01 (steady flow) ---

Flow Title=Imported Flow 01
Version=Version 3.0.1  Mar 2001
Number of Profiles= 5
Profile Names=10YR,20YR,30YR,50YR,80YR
River Rch & RM=RIVER-1,Reach-1         ,1683.00
   16.55   18.22   19.21   20.44   21.58
River Rch & RM=RIVER-1,Reach-1         ,1000.00
   26.39   29.09   30.66   32.64   34.47
Boundary for River Rch & Prof#=RIVER-1,Reach-1         , 1
Up Type= 0
Dn Type= 3
Dn Slope=.038
Boundary for River Rch & Prof#=RIVER-1,Reach-1         , 2
Up Type= 0
Dn Type= 3
Dn Slope=.038
Boundary for River Rch & Prof#=RIVER-1,Reach-1         , 3
Up Type= 0
Dn Type= 3
Dn Slope=.038
Boundary for River Rch & Prof#=RIVER-1,Reach-1         , 4
Up Type= 0
Dn Type= 3
Dn Slope=.038
Boundary for River Rch & Prof#=RIVER-1,Reach-1         , 5
Up Type= 0
Dn Type= 3
Dn Slope=.038
DSS Import GetInterval= 0
DSS Import GetPeak= 0
DSS Import FillOption= 0

--- NAM.g01 (geometry) ---

Geom Title=Imported Geom 01
Version=Version 3.0.1  Mar 2001

River Reach=RIVER-1         ,Reach-1
Reach XY= 2
              .5             .95              .5             .05

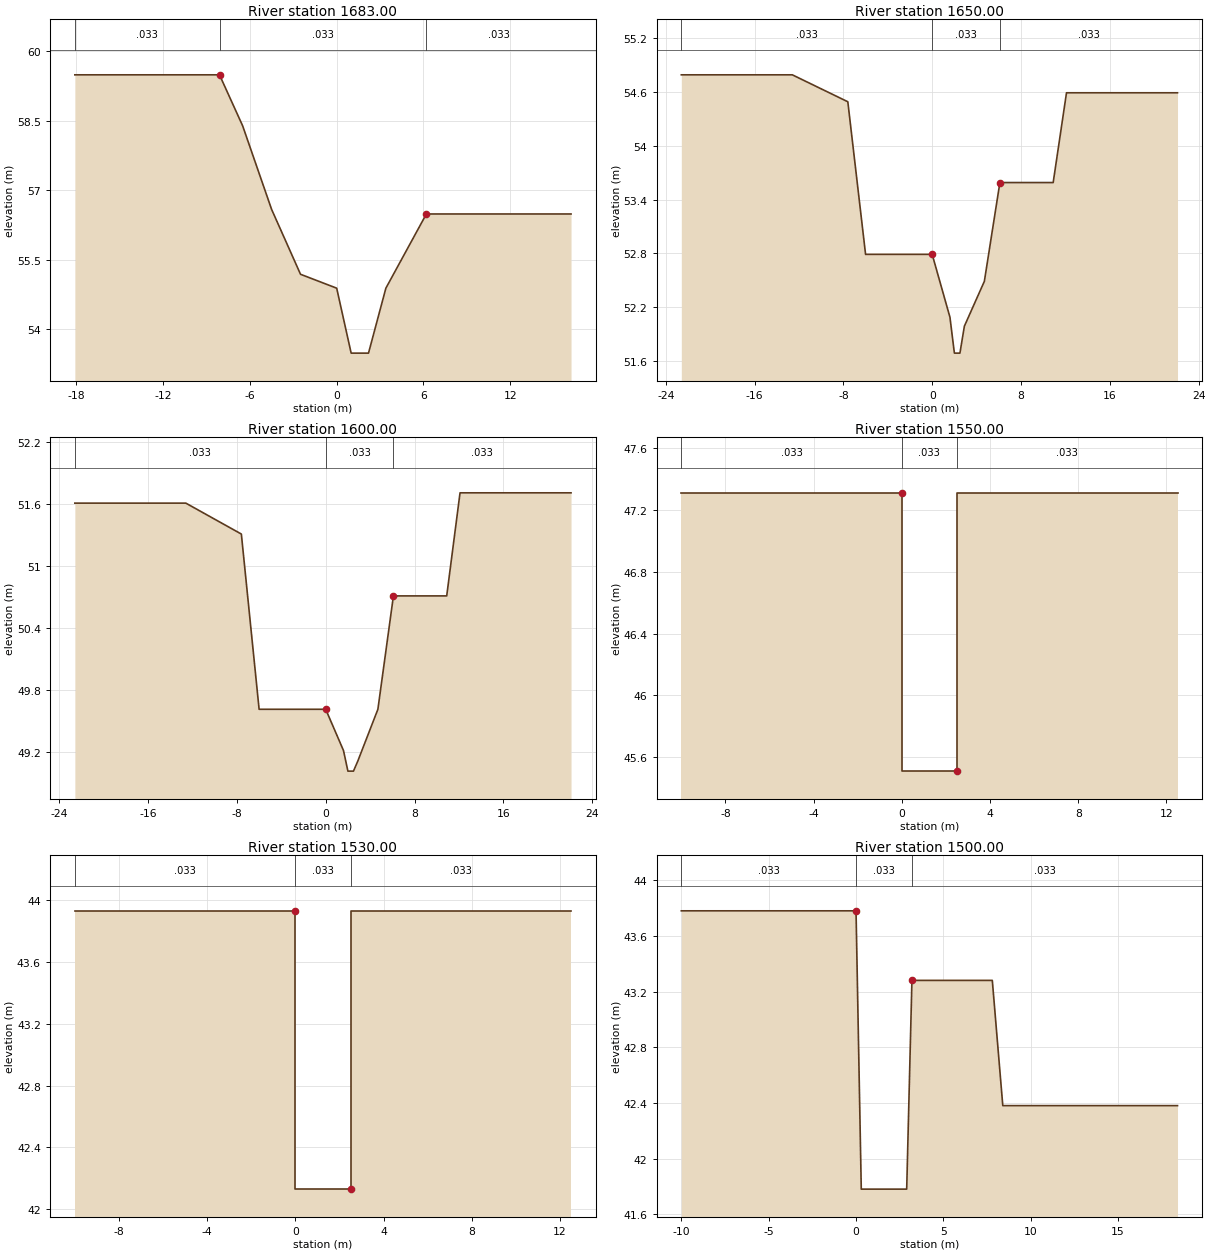
Type RM Length L Ch R = 1 ,1683.00 ,33,33,33
BEGIN DESCRIPTION:
33.033
END DESCRIPTION:
#Sta/Elev= 11
   -18.1   59.49    -8.1   59.49    -6.5   58.39    -4.5   56.59    -2.5   55.19
       0   54.89       1   53.49     2.2   53.49     3.4   54.89     6.2   56.49
    16.2   56.49
#Mann= 3 , 0 , 0
   -18.1    .033       0    -8.1    .033       0     6.2    .033       0
Bank Sta=-8.1,6.2
XS Rating Curve= 0
Exp/Cntr=.3,.1

Type RM Length L Ch R = 1 ,1650.00 ,50,50,50
BEGIN DESCRIPTION:
33
END DESCRIPTION:
#Sta/Elev= 14
   -22.6   54.79   -12.6   54.79    -7.6   54.49      -6   52.79       0   52.79
     1.6   52.09       2   51.69     2.5   51.69     2.9   51.99     4.7   52.49
     6.1   53.59    10.9   53.59    12.1   54.59    22.1   54.59
#Mann= 3 , 0 , 0
   -22.6    .033       0       0    .033       0     6.1    .033       0
Bank Sta=0,6.1
XS Rating Curve= 0
Exp/Cntr=.3,.1

Type RM Length L Ch R = 1 ,1600.00 ,50,50,50
BEGIN DESCRIPTION:
32
END DESCRIPTION:
#Sta/Elev= 14
   -22.6   51.61   -12.6   51.61    -7.6   51.31      -6   49.61       0   49.61
     1.6   49.21       2   49.01     2.5   49.01     2.9   49.11     4.7   49.61
     6.1   50.71    10.9   50.71    12.1   51.71    22.1   51.71
#Mann= 3 , 0 , 0
   -22.6    .033       0       0    .033       0     6.1    .033       0
Bank Sta=0,6.1
XS Rating Curve= 0
Exp/Cntr=.3,.1

Type RM Length L Ch R = 1 ,1550.00 ,20,20,20
BEGIN DESCRIPTION:
31
END DESCRIPTION:
#Sta/Elev= 6
     -10   47.31       0   47.31       0   45.51     2.5   45.51     2.5   47.31
    12.5   47.31
#Mann= 3 , 0 , 0
     -10    .033       0       0    .033       0     2.5    .033       0
Bank Sta=0,2.5
XS Rating Curve= 0
Exp/Cntr=.3,.1

Type RM Length L Ch R = 1 ,1530.00 ,30,30,30
BEGIN DESCRIPTION:
30.03
END DESCRIPTION:
#Sta/Elev= 8
     -10   43.93      -5   43.93       0   43.93       0   42.13     2.5   42.13
     2.5   43.93     7.5   43.93    12.5   43.93
#Mann= 3 , 0 , 0
     -10    .033       0       0    .033       0     2.5    .033       0
Bank Sta=0,2.5
XS Rating Curve= 0
Exp/Cntr=.3,.1

Type RM Length L Ch R = 1 ,1500.00 ,19,19,19
BEGIN DESCRIPTION:
30
END DESCRIPTION:
#Sta/Elev= 8
     -10   43.78       0   43.78      .3   41.78     2.9   41.78     3.2   43.28
     7.8   43.28     8.4   42.38    18.4   42.38
#Mann= 3 , 0 , 0
     -10    .033       0       0    .033       0     3.2    .033       0
Bank Sta=0,3.2
XS Rating Curve= 0
Exp/Cntr=.3,.1

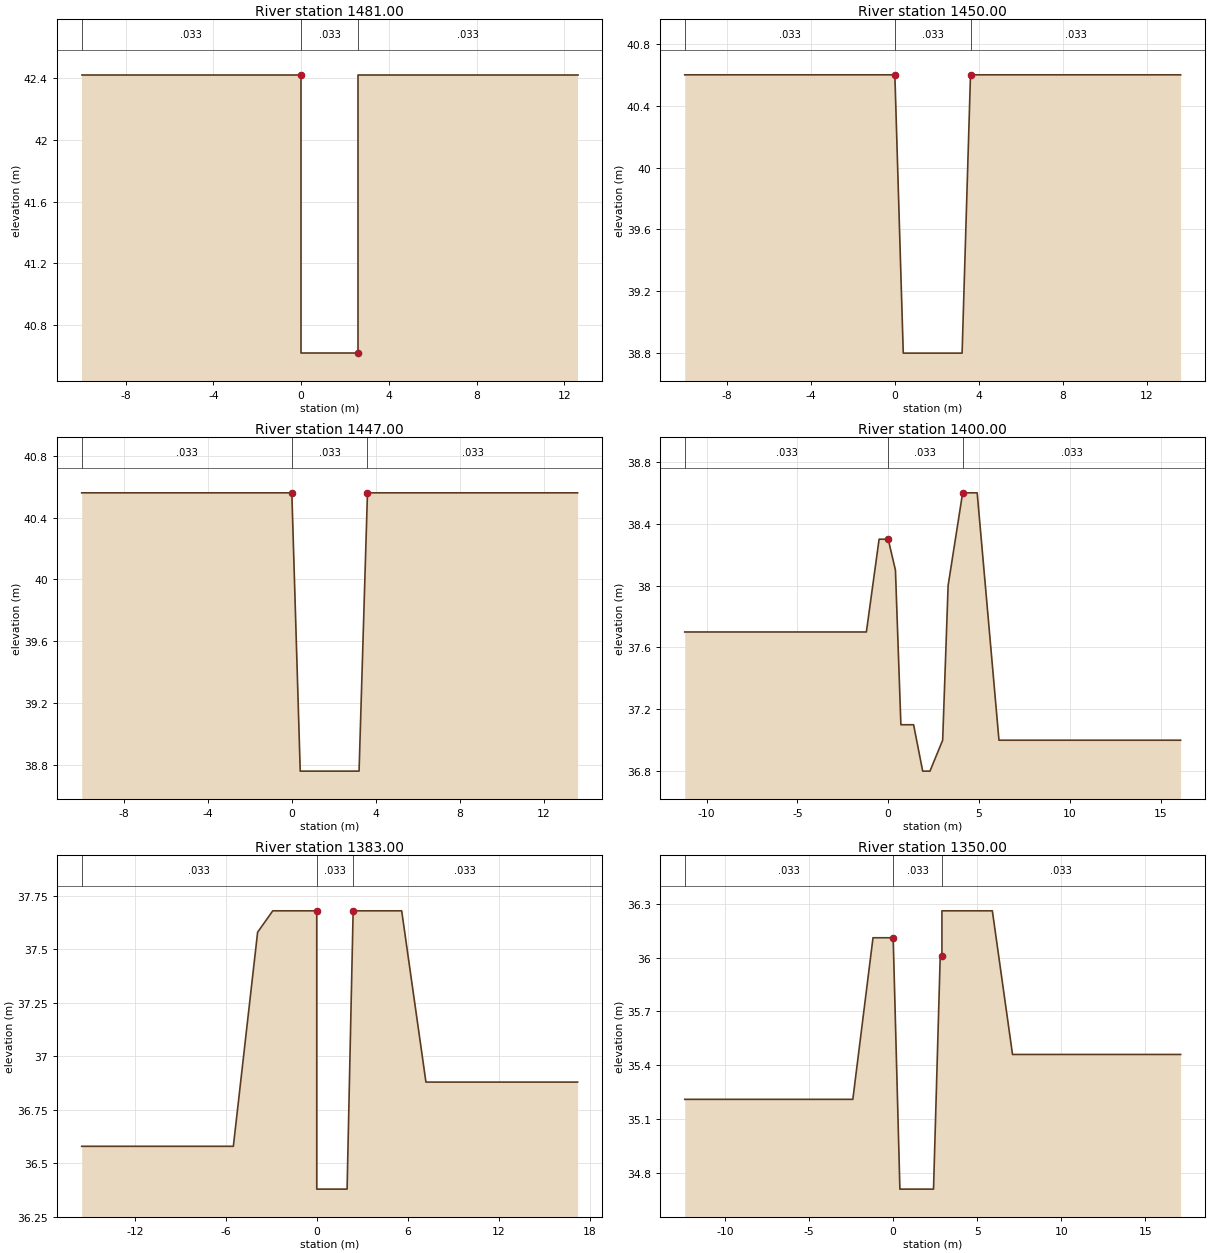
Type RM Length L Ch R = 1 ,1481.00 ,31,31,31
BEGIN DESCRIPTION:
29.031
END DESCRIPTION:
#Sta/Elev= 6
     -10   42.42       0   42.42       0   40.62     2.6   40.62     2.6   42.42
    12.6   42.42
#Mann= 3 , 0 , 0
     -10    .033       0       0    .033       0     2.6    .033       0
Bank Sta=0,2.6
XS Rating Curve= 0
Exp/Cntr=.3,.1

Type RM Length L Ch R = 1 ,1450.00 ,3,3,3
BEGIN DESCRIPTION:
29
END DESCRIPTION:
#Sta/Elev= 6
     -10    40.6       0    40.6      .4    38.8     3.2    38.8     3.6    40.6
    13.6    40.6
#Mann= 3 , 0 , 0
     -10    .033       0       0    .033       0     3.6    .033       0
Bank Sta=0,3.6
XS Rating Curve= 0
Exp/Cntr=.3,.1

Type RM Length L Ch R = 1 ,1447.00 ,47,47,47
BEGIN DESCRIPTION:
28.047
END DESCRIPTION:
#Sta/Elev= 6
     -10   40.56       0   40.56      .4   38.76     3.2   38.76     3.6   40.56
    13.6   40.56
#Mann= 3 , 0 , 0
     -10    .033       0       0    .033       0     3.6    .033       0
Bank Sta=0,3.6
XS Rating Curve= 0
Exp/Cntr=.3,.1

Type RM Length L Ch R = 1 ,1400.00 ,17,17,17
BEGIN DESCRIPTION:
28
END DESCRIPTION:
#Sta/Elev= 15
   -11.2    37.7    -1.2    37.7     -.5    38.3       0    38.3      .4    38.1
      .7    37.1     1.4    37.1     1.9    36.8     2.3    36.8       3      37
     3.3      38     4.1    38.6     4.9    38.6     6.1      37    16.1      37
#Mann= 3 , 0 , 0
   -11.2    .033       0       0    .033       0     4.1    .033       0
Bank Sta=0,4.1
XS Rating Curve= 0
Exp/Cntr=.3,.1

Type RM Length L Ch R = 1 ,1383.00 ,33,33,33
BEGIN DESCRIPTION:
27.033
END DESCRIPTION:
#Sta/Elev= 11
   -15.5   36.58    -5.5   36.58    -3.9   37.58    -2.9   37.68       0   37.68
       0   36.38       2   36.38     2.4   37.68     5.6   37.68     7.2   36.88
    17.2   36.88
#Mann= 3 , 0 , 0
   -15.5    .033       0       0    .033       0     2.4    .033       0
Bank Sta=0,2.4
XS Rating Curve= 0
Exp/Cntr=.3,.1

Type RM Length L Ch R = 1 ,1350.00 ,50,50,50
BEGIN DESCRIPTION:
27
END DESCRIPTION:
#Sta/Elev= 12
   -12.4   35.21    -2.4   35.21    -1.2   36.11       0   36.11      .4   34.71
     2.4   34.71     2.8   36.01     2.9   36.01     2.9   36.26     5.9   36.26
     7.1   35.46    17.1   35.46
#Mann= 3 , 0 , 0
   -12.4    .033       0       0    .033       0     2.9    .033       0
Bank Sta=0,2.9
XS Rating Curve= 0
Exp/Cntr=.3,.1

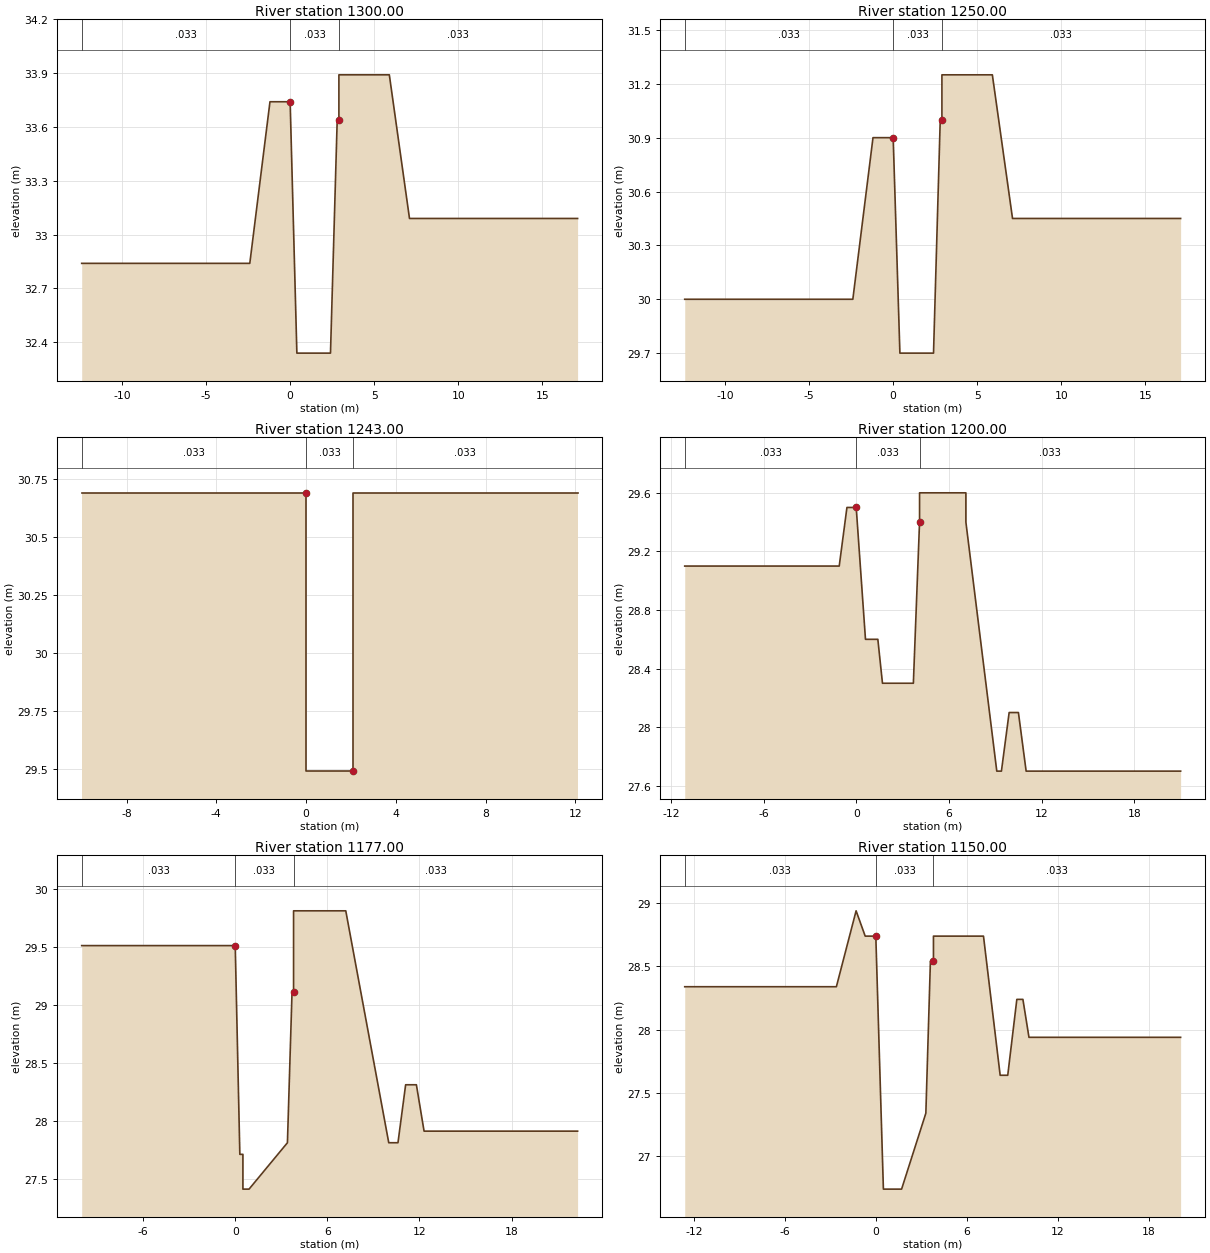
Type RM Length L Ch R = 1 ,1300.00 ,50,50,50
BEGIN DESCRIPTION:
26
END DESCRIPTION:
#Sta/Elev= 12
   -12.4   32.84    -2.4   32.84    -1.2   33.74       0   33.74      .4   32.34
     2.4   32.34     2.8   33.64     2.9   33.64     2.9   33.89     5.9   33.89
     7.1   33.09    17.1   33.09
#Mann= 3 , 0 , 0
   -12.4    .033       0       0    .033       0     2.9    .033       0
Bank Sta=0,2.9
XS Rating Curve= 0
Exp/Cntr=.3,.1

Type RM Length L Ch R = 1 ,1250.00 ,7,7,7
BEGIN DESCRIPTION:
25
END DESCRIPTION:
#Sta/Elev= 12
   -12.4      30    -2.4      30    -1.2    30.9       0    30.9      .4    29.7
     2.4    29.7     2.8      31     2.9      31     2.9   31.25     5.9   31.25
     7.1   30.45    17.1   30.45
#Mann= 3 , 0 , 0
   -12.4    .033       0       0    .033       0     2.9    .033       0
Bank Sta=0,2.9
XS Rating Curve= 0
Exp/Cntr=.3,.1

Type RM Length L Ch R = 1 ,1243.00 ,43,43,43
BEGIN DESCRIPTION:
24.043
END DESCRIPTION:
#Sta/Elev= 8
     -10   30.69      -5   30.69       0   30.69       0   29.49     2.1   29.49
     2.1   30.69     7.1   30.69    12.1   30.69
#Mann= 3 , 0 , 0
     -10    .033       0       0    .033       0     2.1    .033       0
Bank Sta=0,2.1
XS Rating Curve= 0
Exp/Cntr=.3,.1

Type RM Length L Ch R = 1 ,1200.00 ,23,23,23
BEGIN DESCRIPTION:
24
END DESCRIPTION:
#Sta/Elev= 18
   -11.1    29.1    -1.1    29.1     -.6    29.5       0    29.5      .6    28.6
     1.4    28.6     1.7    28.3     3.7    28.3     4.1    29.4     4.1    29.6
     7.1    29.6     7.1    29.4     9.1    27.7     9.4    27.7     9.9    28.1
    10.5    28.1      11    27.7      21    27.7
#Mann= 3 , 0 , 0
   -11.1    .033       0       0    .033       0     4.1    .033       0
Bank Sta=0,4.1
XS Rating Curve= 0
Exp/Cntr=.3,.1

Type RM Length L Ch R = 1 ,1177.00 ,27,27,27
BEGIN DESCRIPTION:
23.027
END DESCRIPTION:
#Sta/Elev= 17
     -10   29.51       0   29.51      .3   27.71      .5   27.71      .5   27.41
      .9   27.41     3.4   27.81     3.7   29.11     3.8   29.11     3.8   29.81
     7.2   29.81      10   27.81    10.6   27.81    11.1   28.31    11.8   28.31
    12.3   27.91    22.3   27.91
#Mann= 3 , 0 , 0
     -10    .033       0       0    .033       0     3.8    .033       0
Bank Sta=0,3.8
XS Rating Curve= 0
Exp/Cntr=.3,.1

Type RM Length L Ch R = 1 ,1150.00 ,50,50,50
BEGIN DESCRIPTION:
23
END DESCRIPTION:
#Sta/Elev= 18
   -12.6   28.34    -2.6   28.34    -1.3   28.94     -.7   28.74       0   28.74
      .5   26.74     1.7   26.74     3.3   27.34     3.6   28.54     3.8   28.54
     3.8   28.74     7.1   28.74     8.2   27.64     8.7   27.64     9.3   28.24
     9.7   28.24    10.1   27.94    20.1   27.94
#Mann= 3 , 0 , 0
   -12.6    .033       0       0    .033       0     3.8    .033       0
Bank Sta=0,3.8
XS Rating Curve= 0
Exp/Cntr=.3,.1

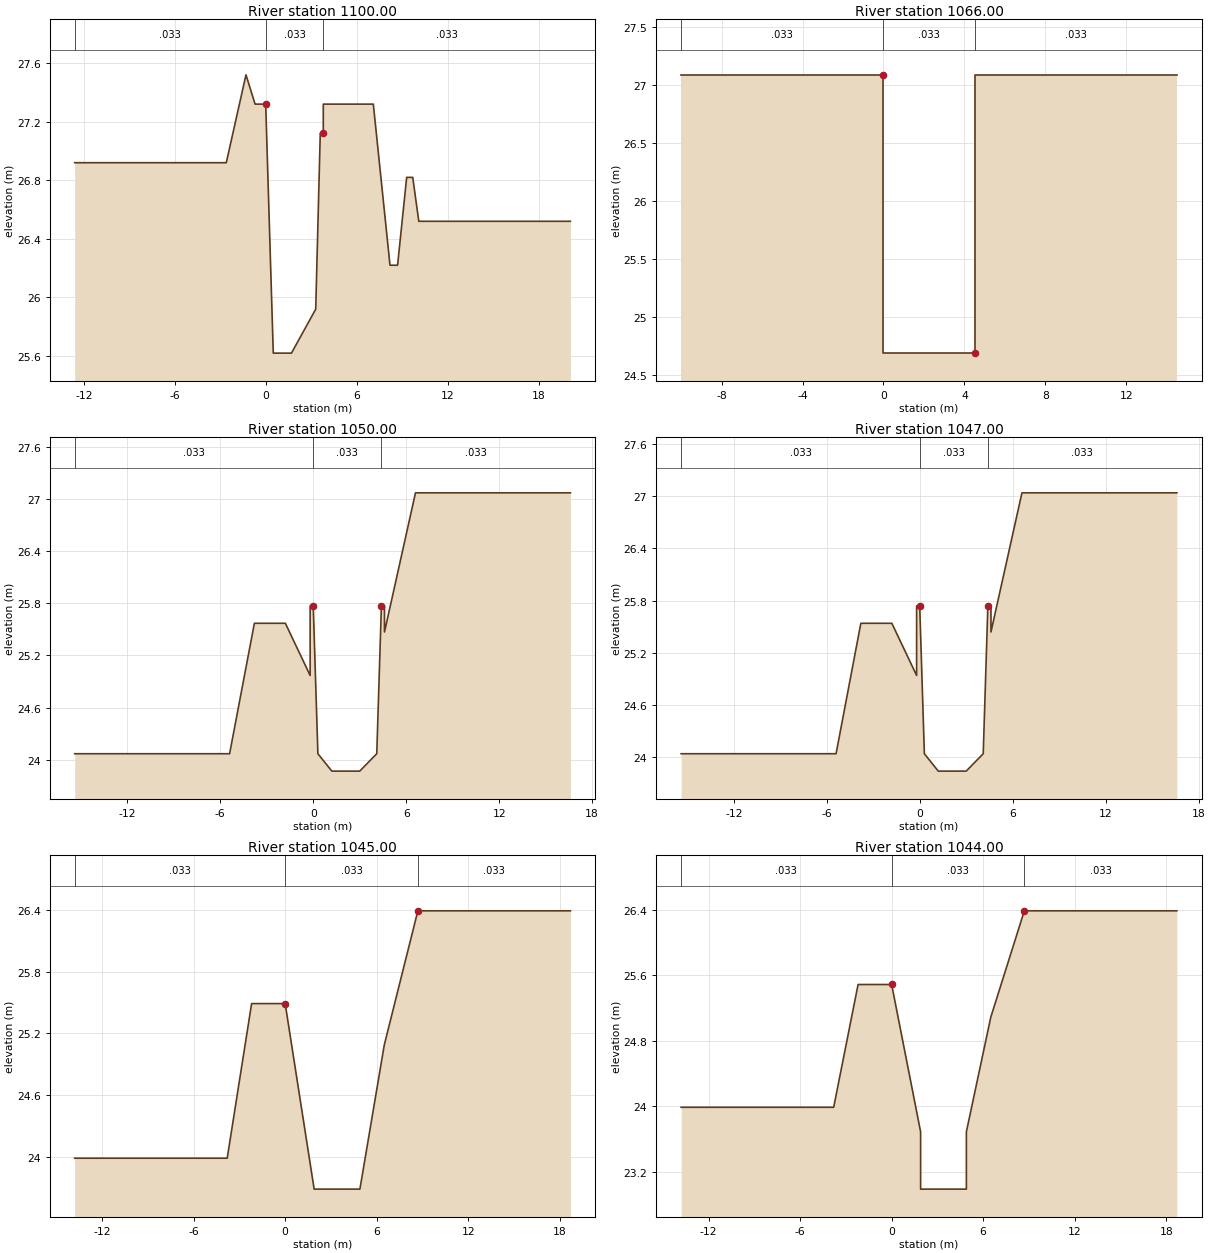
Type RM Length L Ch R = 1 ,1100.00 ,34,34,34
BEGIN DESCRIPTION:
22
END DESCRIPTION:
#Sta/Elev= 18
   -12.6   26.92    -2.6   26.92    -1.3   27.52     -.7   27.32       0   27.32
      .5   25.62     1.7   25.62     3.3   25.92     3.6   27.12     3.8   27.12
     3.8   27.32     7.1   27.32     8.2   26.22     8.7   26.22     9.3   26.82
     9.7   26.82    10.1   26.52    20.1   26.52
#Mann= 3 , 0 , 0
   -12.6    .033       0       0    .033       0     3.8    .033       0
Bank Sta=0,3.8
XS Rating Curve= 0
Exp/Cntr=.3,.1

Type RM Length L Ch R = 1 ,1066.00 ,16,16,16
BEGIN DESCRIPTION:
21.016
END DESCRIPTION:
#Sta/Elev= 6
     -10   27.09       0   27.09       0   24.69     4.5   24.69     4.5   27.09
    14.5   27.09
#Mann= 3 , 0 , 0
     -10    .033       0       0    .033       0     4.5    .033       0
Bank Sta=0,4.5
XS Rating Curve= 0
Exp/Cntr=.3,.1

Type RM Length L Ch R = 1 ,1050.00 ,3,3,3
BEGIN DESCRIPTION:
21
END DESCRIPTION:
#Sta/Elev= 16
   -15.4   24.07    -5.4   24.07    -3.8   25.57    -1.8   25.57     -.2   24.97
     -.2   25.77       0   25.77      .3   24.07     1.2   23.87       3   23.87
     4.1   24.07     4.4   25.77     4.6   25.77     4.6   25.47     6.6   27.07
    16.6   27.07
#Mann= 3 , 0 , 0
   -15.4    .033       0       0    .033       0     4.4    .033       0
Bank Sta=0,4.4
XS Rating Curve= 0
Exp/Cntr=.3,.1

Type RM Length L Ch R = 1 ,1047.00 ,2,2,2
BEGIN DESCRIPTION:
20.047
END DESCRIPTION:
#Sta/Elev= 16
   -15.4   24.04    -5.4   24.04    -3.8   25.54    -1.8   25.54     -.2   24.94
     -.2   25.74       0   25.74      .3   24.04     1.2   23.84       3   23.84
     4.1   24.04     4.4   25.74     4.6   25.74     4.6   25.44     6.6   27.04
    16.6   27.04
#Mann= 3 , 0 , 0
   -15.4    .033       0       0    .033       0     4.4    .033       0
Bank Sta=0,4.4
XS Rating Curve= 0
Exp/Cntr=.3,.1

Type RM Length L Ch R = 1 ,1045.00 ,1,1,1
BEGIN DESCRIPTION:
20.045
END DESCRIPTION:
#Sta/Elev= 9
   -13.8   23.99    -3.8   23.99    -2.2   25.49       0   25.49     1.9   23.69
     4.9   23.69     6.5   25.09     8.7   26.39    18.7   26.39
#Mann= 3 , 0 , 0
   -13.8    .033       0       0    .033       0     8.7    .033       0
Bank Sta=0,8.7
XS Rating Curve= 0
Exp/Cntr=.3,.1

Type RM Length L Ch R = 1 ,1044.00 ,22,22,22
BEGIN DESCRIPTION:
20.044
END DESCRIPTION:
#Sta/Elev= 11
   -13.8   23.99    -3.8   23.99    -2.2   25.49       0   25.49     1.9   23.69
     1.9   22.99     4.9   22.99     4.9   23.69     6.5   25.09     8.7   26.39
    18.7   26.39
#Mann= 3 , 0 , 0
   -13.8    .033       0       0    .033       0     8.7    .033       0
Bank Sta=0,8.7
XS Rating Curve= 0
Exp/Cntr=.3,.1

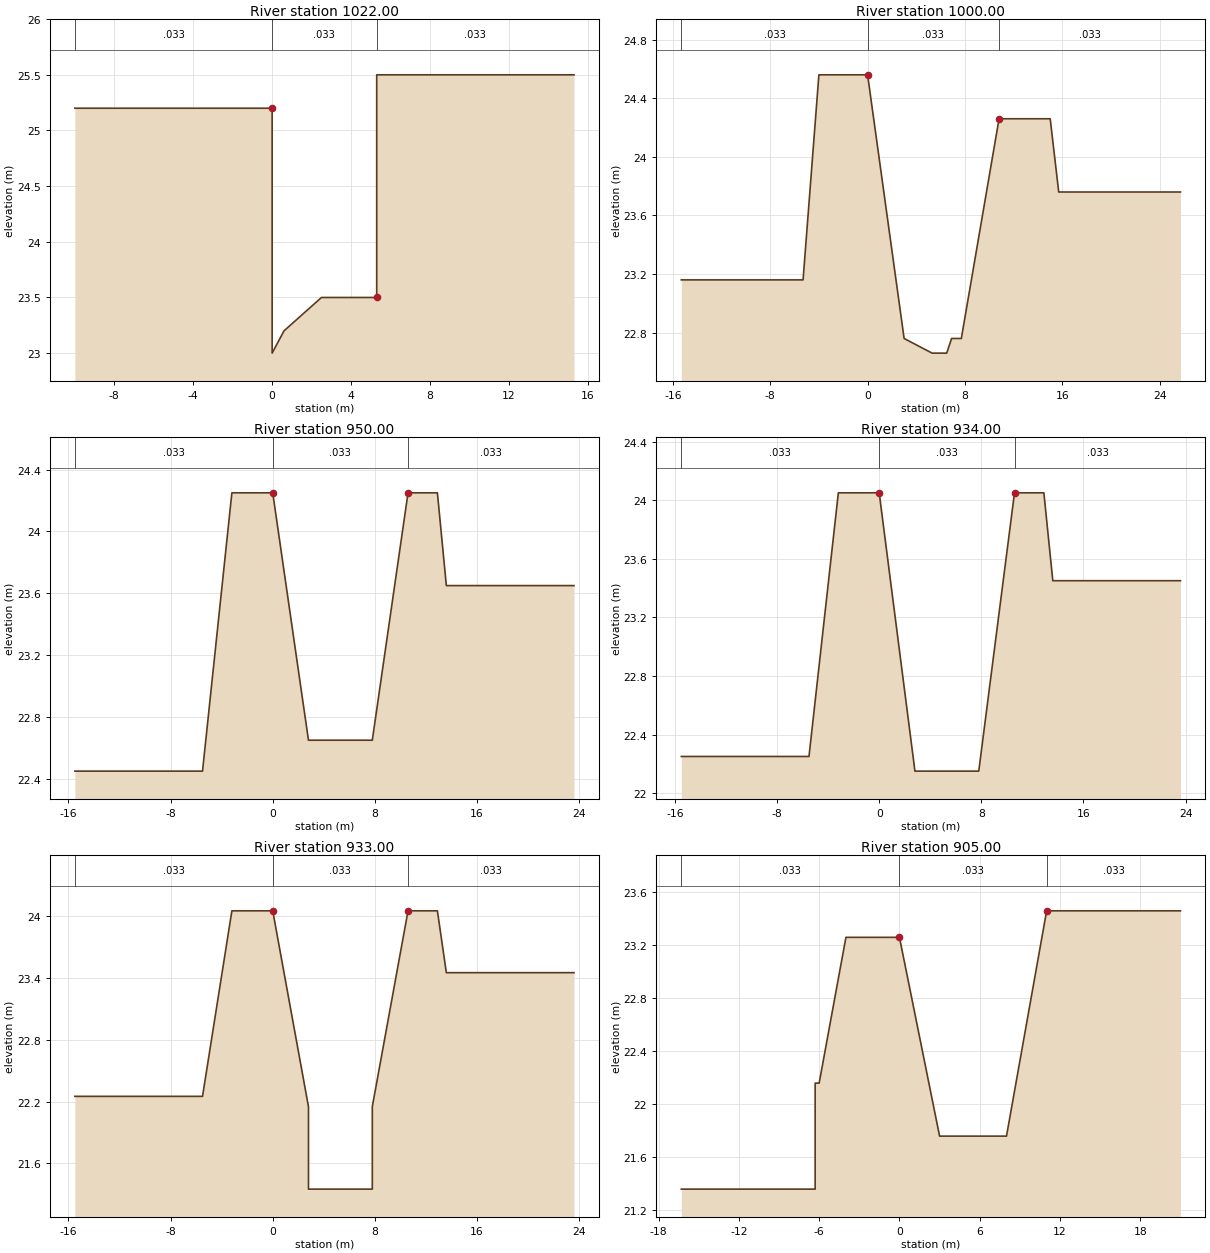
Type RM Length L Ch R = 1 ,1022.00 ,22,22,22
BEGIN DESCRIPTION:
20.022
END DESCRIPTION:
#Sta/Elev= 10
     -10    25.2      -5    25.2       0    25.2       0      23      .6    23.2
     2.5    23.5     5.3    23.5     5.3    25.5    10.3    25.5    15.3    25.5
#Mann= 3 , 0 , 0
     -10    .033       0       0    .033       0     5.3    .033       0
Bank Sta=0,5.3
XS Rating Curve= 0
Exp/Cntr=.3,.1

Type RM Length L Ch R = 1 ,1000.00 ,50,50,50
BEGIN DESCRIPTION:
20
END DESCRIPTION:
#Sta/Elev= 13
   -15.3   23.16    -5.3   23.16      -4   24.56       0   24.56       3   22.76
     5.3   22.66     6.5   22.66     6.9   22.76     7.7   22.76    10.8   24.26
      15   24.26    15.7   23.76    25.7   23.76
#Mann= 3 , 0 , 0
   -15.3    .033       0       0    .033       0    10.8    .033       0
Bank Sta=0,10.8
XS Rating Curve= 0
Exp/Cntr=.3,.1

Type RM Length L Ch R = 1 ,950.00  ,16,16,16
BEGIN DESCRIPTION:
19
END DESCRIPTION:
#Sta/Elev= 10
   -15.5   22.45    -5.5   22.45    -3.2   24.25       0   24.25     2.8   22.65
     7.8   22.65    10.6   24.25    12.9   24.25    13.6   23.65    23.6   23.65
#Mann= 3 , 0 , 0
   -15.5    .033       0       0    .033       0    10.6    .033       0
Bank Sta=0,10.6
XS Rating Curve= 0
Exp/Cntr=.3,.1

Type RM Length L Ch R = 1 ,934.00  ,1,1,1
BEGIN DESCRIPTION:
18.034
END DESCRIPTION:
#Sta/Elev= 10
   -15.5   22.25    -5.5   22.25    -3.2   24.05       0   24.05     2.8   22.15
     7.8   22.15    10.6   24.05    12.9   24.05    13.6   23.45    23.6   23.45
#Mann= 3 , 0 , 0
   -15.5    .033       0       0    .033       0    10.6    .033       0
Bank Sta=0,10.6
XS Rating Curve= 0
Exp/Cntr=.3,.1

Type RM Length L Ch R = 1 ,933.00  ,28,28,28
BEGIN DESCRIPTION:
18.033
END DESCRIPTION:
#Sta/Elev= 12
   -15.5   22.25    -5.5   22.25    -3.2   24.05       0   24.05     2.8   22.15
     2.8   21.35     7.8   21.35     7.8   22.15    10.6   24.05    12.9   24.05
    13.6   23.45    23.6   23.45
#Mann= 3 , 0 , 0
   -15.5    .033       0       0    .033       0    10.6    .033       0
Bank Sta=0,10.6
XS Rating Curve= 0
Exp/Cntr=.3,.1

Type RM Length L Ch R = 1 ,905.00  ,1,1,1
BEGIN DESCRIPTION:
18.005
END DESCRIPTION:
#Sta/Elev= 10
   -16.3   21.36    -6.3   21.36    -6.3   22.16      -6   22.16      -4   23.26
       0   23.26       3   21.76       8   21.76      11   23.46      21   23.46
#Mann= 3 , 0 , 0
   -16.3    .033       0       0    .033       0      11    .033       0
Bank Sta=0,11
XS Rating Curve= 0
Exp/Cntr=.3,.1

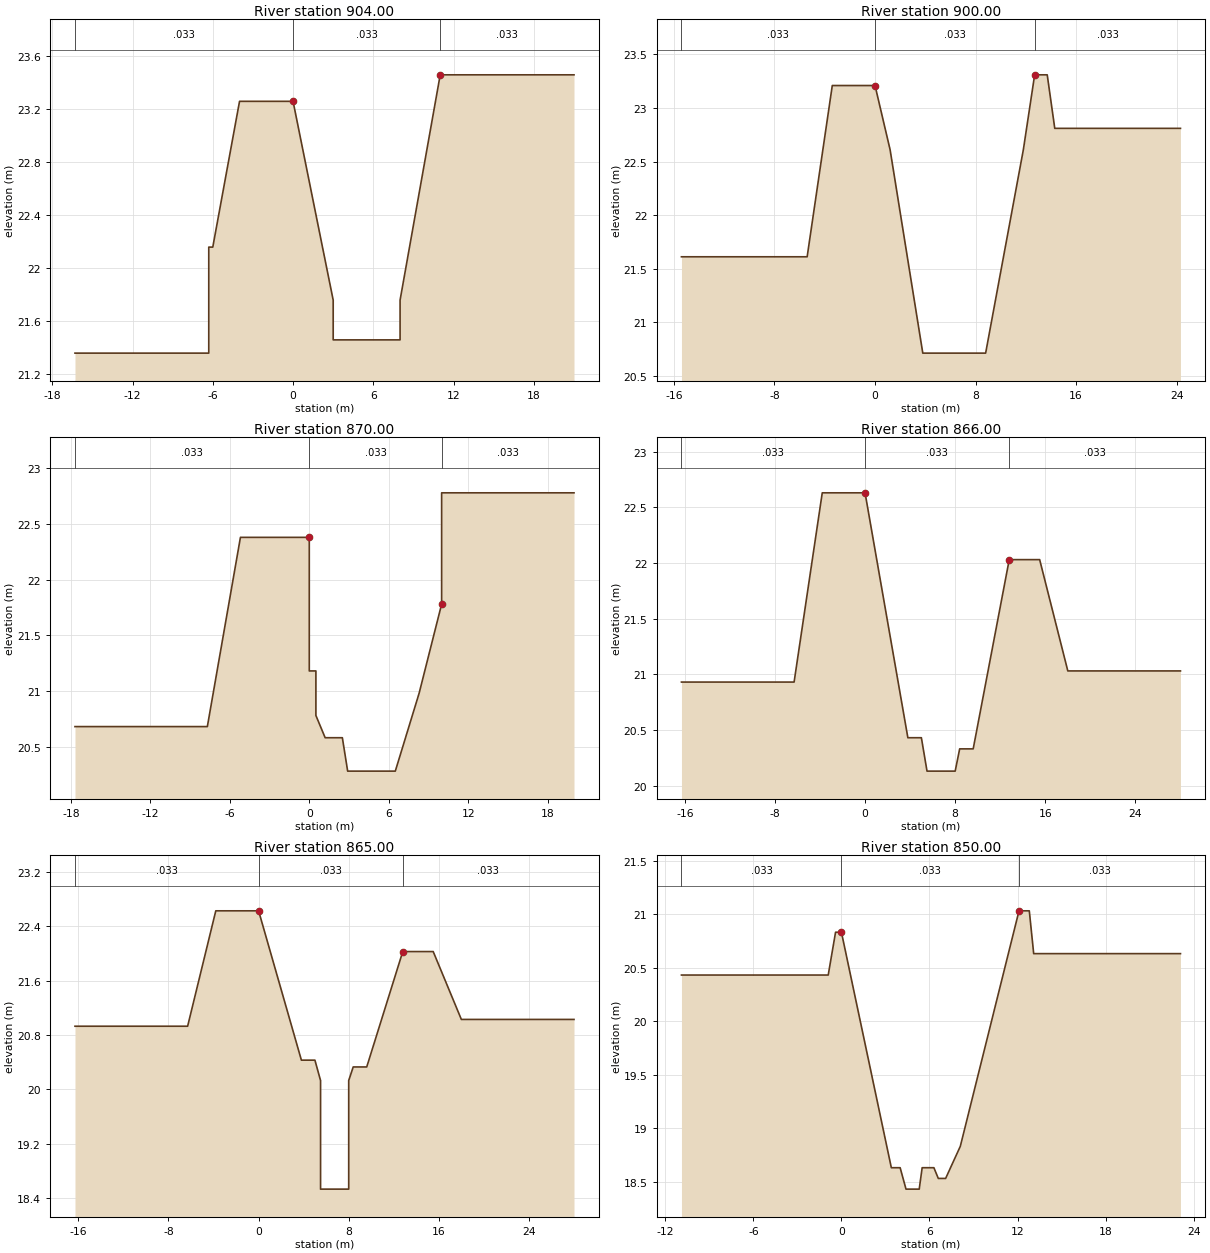
Type RM Length L Ch R = 1 ,904.00  ,4,4,4
BEGIN DESCRIPTION:
18.004
END DESCRIPTION:
#Sta/Elev= 12
   -16.3   21.36    -6.3   21.36    -6.3   22.16      -6   22.16      -4   23.26
       0   23.26       3   21.76       3   21.46       8   21.46       8   21.76
      11   23.46      21   23.46
#Mann= 3 , 0 , 0
   -16.3    .033       0       0    .033       0      11    .033       0
Bank Sta=0,11
XS Rating Curve= 0
Exp/Cntr=.3,.1

Type RM Length L Ch R = 1 ,900.00  ,30,30,30
BEGIN DESCRIPTION:
18
END DESCRIPTION:
#Sta/Elev= 12
   -15.4   21.61    -5.4   21.61    -3.4   23.21       0   23.21     1.2   22.61
     3.8   20.71     8.8   20.71    11.8   22.61    12.7   23.31    13.7   23.31
    14.3   22.81    24.3   22.81
#Mann= 3 , 0 , 0
   -15.4    .033       0       0    .033       0    12.7    .033       0
Bank Sta=0,12.7
XS Rating Curve= 0
Exp/Cntr=.3,.1

Type RM Length L Ch R = 1 ,870.00  ,4,4,4
BEGIN DESCRIPTION:
17.02
END DESCRIPTION:
#Sta/Elev= 15
   -17.7   20.68    -7.7   20.68    -5.2   22.38       0   22.38       0   21.18
      .5   21.18      .5   20.78     1.2   20.58     2.5   20.58     2.9   20.28
     6.5   20.28     8.3   20.98      10   21.78      10   22.78      20   22.78
#Mann= 3 , 0 , 0
   -17.7    .033       0       0    .033       0      10    .033       0
Bank Sta=0,10
XS Rating Curve= 0
Exp/Cntr=.3,.1

Type RM Length L Ch R = 1 ,866.00  ,1,1,1
BEGIN DESCRIPTION:
17.016
END DESCRIPTION:
#Sta/Elev= 14
   -16.3   20.93    -6.3   20.93    -3.8   22.63       0   22.63     3.8   20.43
       5   20.43     5.5   20.13       8   20.13     8.4   20.33     9.6   20.33
    12.8   22.03    15.5   22.03      18   21.03      28   21.03
#Mann= 3 , 0 , 0
   -16.3    .033       0       0    .033       0    12.8    .033       0
Bank Sta=0,12.8
XS Rating Curve= 0
Exp/Cntr=.3,.1

Type RM Length L Ch R = 1 ,865.00  ,15,15,15
BEGIN DESCRIPTION:
17.015
END DESCRIPTION:
#Sta/Elev= 16
   -16.3   20.93    -6.3   20.93    -3.8   22.63       0   22.63     3.8   20.43
       5   20.43     5.5   20.13     5.5   18.53       8   18.53       8   20.13
     8.4   20.33     9.6   20.33    12.8   22.03    15.5   22.03      18   21.03
      28   21.03
#Mann= 3 , 0 , 0
   -16.3    .033       0       0    .033       0    12.8    .033       0
Bank Sta=0,12.8
XS Rating Curve= 0
Exp/Cntr=.3,.1

Type RM Length L Ch R = 1 ,850.00  ,50,50,50
BEGIN DESCRIPTION:
17
END DESCRIPTION:
#Sta/Elev= 17
   -10.9   20.43     -.9   20.43     -.4   20.83       0   20.83     3.4   18.63
       4   18.63     4.4   18.43     5.3   18.43     5.5   18.63     6.3   18.63
     6.6   18.53     7.1   18.53     8.1   18.83    12.1   21.03    12.8   21.03
    13.1   20.63    23.1   20.63
#Mann= 3 , 0 , 0
   -10.9    .033       0       0    .033       0    12.1    .033       0
Bank Sta=0,12.1
XS Rating Curve= 0
Exp/Cntr=.3,.1

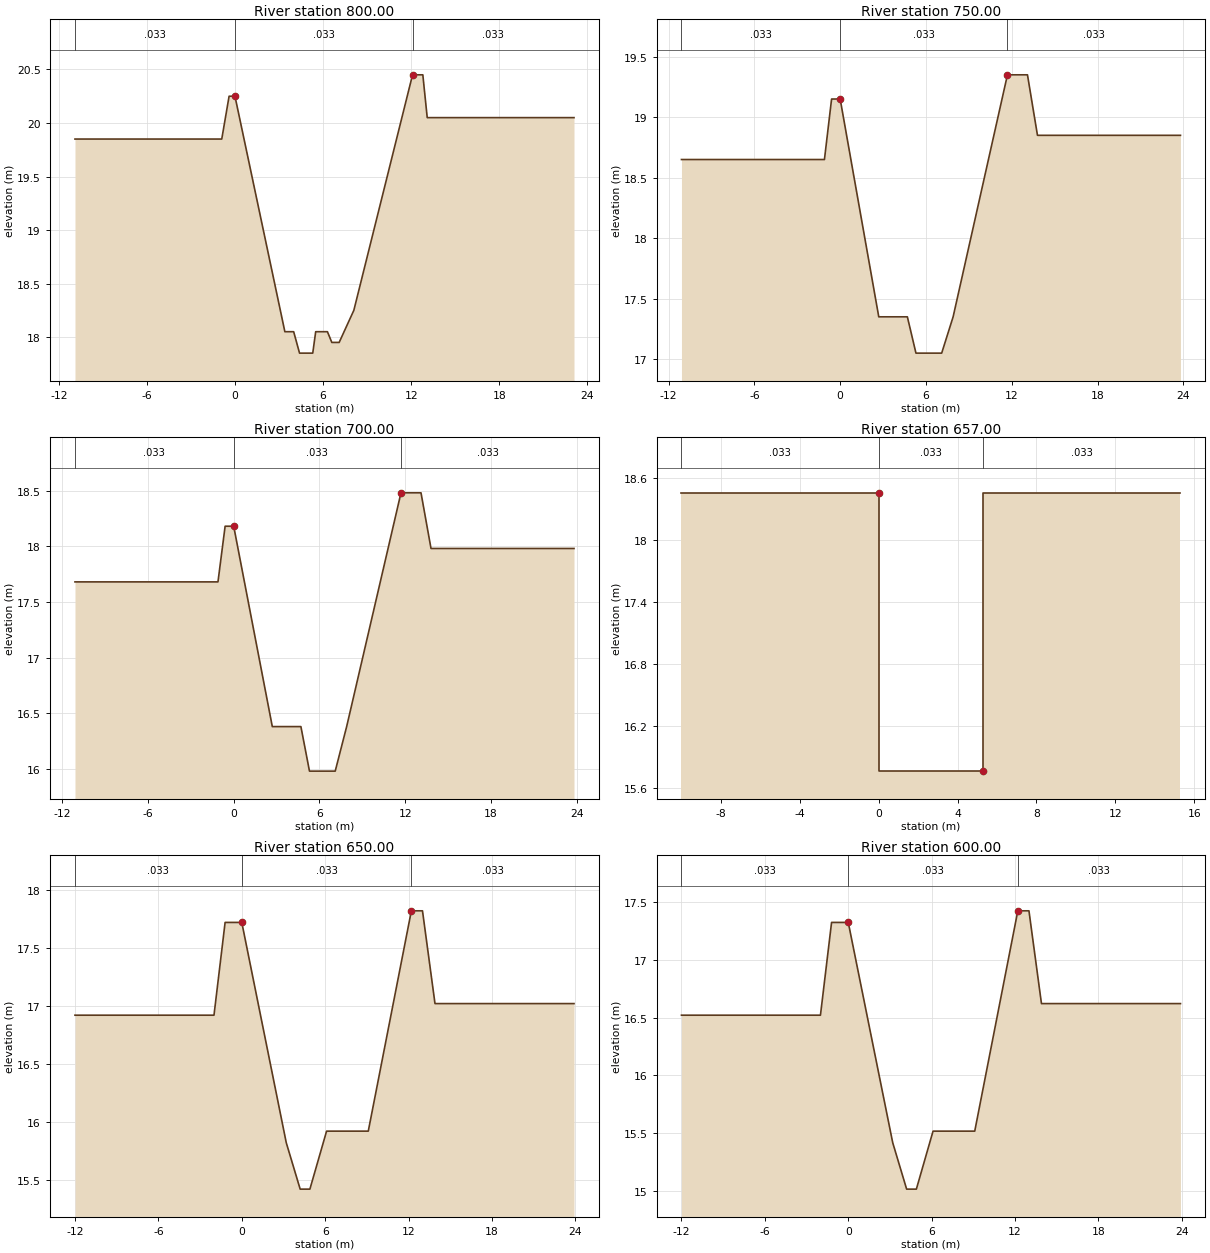
Type RM Length L Ch R = 1 ,800.00  ,50,50,50
BEGIN DESCRIPTION:
16
END DESCRIPTION:
#Sta/Elev= 17
   -10.9   19.85     -.9   19.85     -.4   20.25       0   20.25     3.4   18.05
       4   18.05     4.4   17.85     5.3   17.85     5.5   18.05     6.3   18.05
     6.6   17.95     7.1   17.95     8.1   18.25    12.1   20.45    12.8   20.45
    13.1   20.05    23.1   20.05
#Mann= 3 , 0 , 0
   -10.9    .033       0       0    .033       0    12.1    .033       0
Bank Sta=0,12.1
XS Rating Curve= 0
Exp/Cntr=.3,.1

Type RM Length L Ch R = 1 ,750.00  ,50,50,50
BEGIN DESCRIPTION:
15
END DESCRIPTION:
#Sta/Elev= 13
   -11.1   18.65    -1.1   18.65     -.6   19.15       0   19.15     2.7   17.35
     4.7   17.35     5.3   17.05     7.1   17.05     7.9   17.35    11.7   19.35
    13.1   19.35    13.8   18.85    23.8   18.85
#Mann= 3 , 0 , 0
   -11.1    .033       0       0    .033       0    11.7    .033       0
Bank Sta=0,11.7
XS Rating Curve= 0
Exp/Cntr=.3,.1

Type RM Length L Ch R = 1 ,700.00  ,43,43,43
BEGIN DESCRIPTION:
14
END DESCRIPTION:
#Sta/Elev= 13
   -11.1   17.68    -1.1   17.68     -.6   18.18       0   18.18     2.7   16.38
     4.7   16.38     5.3   15.98     7.1   15.98     7.9   16.38    11.7   18.48
    13.1   18.48    13.8   17.98    23.8   17.98
#Mann= 3 , 0 , 0
   -11.1    .033       0       0    .033       0    11.7    .033       0
Bank Sta=0,11.7
XS Rating Curve= 0
Exp/Cntr=.3,.1

Type RM Length L Ch R = 1 ,657.00  ,7,7,7
BEGIN DESCRIPTION:
13.007
END DESCRIPTION:
#Sta/Elev= 8
     -10   18.46      -5   18.46       0   18.46       0   15.76     5.3   15.76
     5.3   18.46    10.3   18.46    15.3   18.46
#Mann= 3 , 0 , 0
     -10    .033       0       0    .033       0     5.3    .033       0
Bank Sta=0,5.3
XS Rating Curve= 0
Exp/Cntr=.3,.1

Type RM Length L Ch R = 1 ,650.00  ,50,50,50
BEGIN DESCRIPTION:
13
END DESCRIPTION:
#Sta/Elev= 13
     -12   16.92      -2   16.92    -1.2   17.72       0   17.72     3.2   15.82
     4.2   15.42     4.9   15.42     6.1   15.92     9.1   15.92    12.2   17.82
      13   17.82    13.9   17.02    23.9   17.02
#Mann= 3 , 0 , 0
     -12    .033       0       0    .033       0    12.2    .033       0
Bank Sta=0,12.2
XS Rating Curve= 0
Exp/Cntr=.3,.1

Type RM Length L Ch R = 1 ,600.00  ,44,44,44
BEGIN DESCRIPTION:
12
END DESCRIPTION:
#Sta/Elev= 13
     -12   16.52      -2   16.52    -1.2   17.32       0   17.32     3.2   15.42
     4.2   15.02     4.9   15.02     6.1   15.52     9.1   15.52    12.2   17.42
      13   17.42    13.9   16.62    23.9   16.62
#Mann= 3 , 0 , 0
     -12    .033       0       0    .033       0    12.2    .033       0
Bank Sta=0,12.2
XS Rating Curve= 0
Exp/Cntr=.3,.1

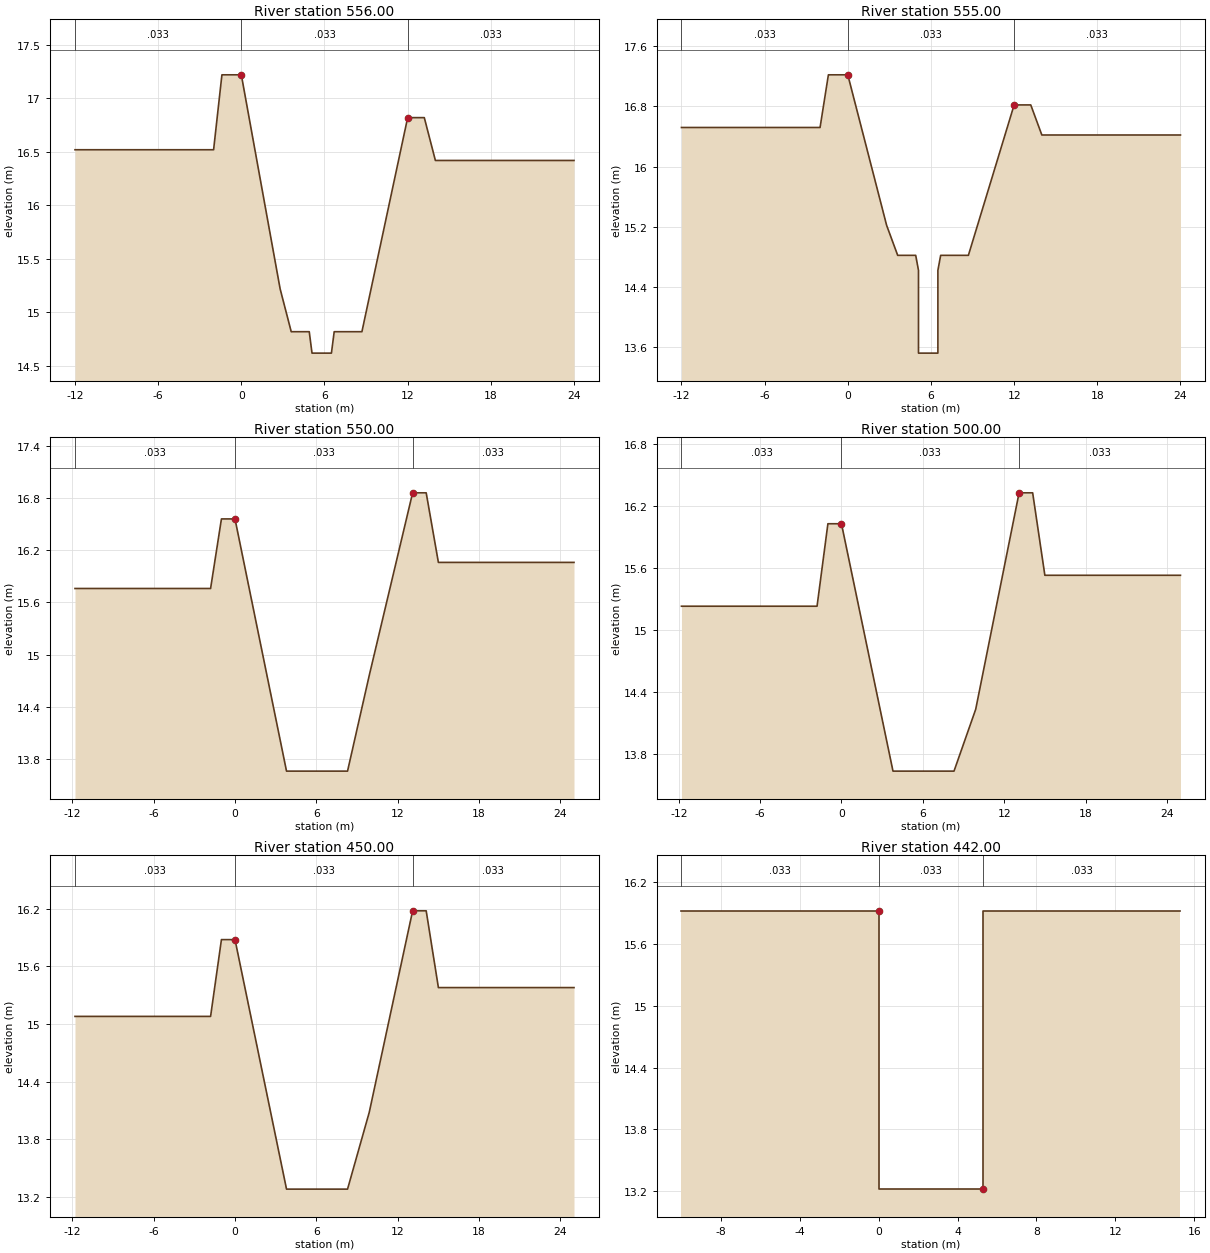
Type RM Length L Ch R = 1 ,556.00  ,1,1,1
BEGIN DESCRIPTION:
11.006
END DESCRIPTION:
#Sta/Elev= 15
     -12   16.52      -2   16.52    -1.4   17.22       0   17.22     2.8   15.22
     3.6   14.82     4.9   14.82     5.1   14.62     6.5   14.62     6.7   14.82
     8.7   14.82      12   16.82    13.2   16.82      14   16.42      24   16.42
#Mann= 3 , 0 , 0
     -12    .033       0       0    .033       0      12    .033       0
Bank Sta=0,12
XS Rating Curve= 0
Exp/Cntr=.3,.1

Type RM Length L Ch R = 1 ,555.00  ,5,5,5
BEGIN DESCRIPTION:
11.005
END DESCRIPTION:
#Sta/Elev= 17
     -12   16.52      -2   16.52    -1.4   17.22       0   17.22     2.8   15.22
     3.6   14.82     4.9   14.82     5.1   14.62     5.1   13.52     6.5   13.52
     6.5   14.62     6.7   14.82     8.7   14.82      12   16.82    13.2   16.82
      14   16.42      24   16.42
#Mann= 3 , 0 , 0
     -12    .033       0       0    .033       0      12    .033       0
Bank Sta=0,12
XS Rating Curve= 0
Exp/Cntr=.3,.1

Type RM Length L Ch R = 1 ,550.00  ,50,50,50
BEGIN DESCRIPTION:
11
END DESCRIPTION:
#Sta/Elev= 11
   -11.8   15.76    -1.8   15.76      -1   16.56       0   16.56     3.8   13.66
     8.3   13.66     9.9   14.76    13.1   16.86    14.1   16.86      15   16.06
      25   16.06
#Mann= 3 , 0 , 0
   -11.8    .033       0       0    .033       0    13.1    .033       0
Bank Sta=0,13.1
XS Rating Curve= 0
Exp/Cntr=.3,.1

Type RM Length L Ch R = 1 ,500.00  ,50,50,50
BEGIN DESCRIPTION:
10
END DESCRIPTION:
#Sta/Elev= 11
   -11.8   15.23    -1.8   15.23      -1   16.03       0   16.03     3.8   13.63
     8.3   13.63     9.9   14.23    13.1   16.33    14.1   16.33      15   15.53
      25   15.53
#Mann= 3 , 0 , 0
   -11.8    .033       0       0    .033       0    13.1    .033       0
Bank Sta=0,13.1
XS Rating Curve= 0
Exp/Cntr=.3,.1

Type RM Length L Ch R = 1 ,450.00  ,8,8,8
BEGIN DESCRIPTION:
9
END DESCRIPTION:
#Sta/Elev= 11
   -11.8   15.08    -1.8   15.08      -1   15.88       0   15.88     3.8   13.28
     8.3   13.28     9.9   14.08    13.1   16.18    14.1   16.18      15   15.38
      25   15.38
#Mann= 3 , 0 , 0
   -11.8    .033       0       0    .033       0    13.1    .033       0
Bank Sta=0,13.1
XS Rating Curve= 0
Exp/Cntr=.3,.1

Type RM Length L Ch R = 1 ,442.00  ,42,42,42
BEGIN DESCRIPTION:
8.042
END DESCRIPTION:
#Sta/Elev= 8
     -10   15.92      -5   15.92       0   15.92       0   13.22     5.3   13.22
     5.3   15.92    10.3   15.92    15.3   15.92
#Mann= 3 , 0 , 0
     -10    .033       0       0    .033       0     5.3    .033       0
Bank Sta=0,5.3
XS Rating Curve= 0
Exp/Cntr=.3,.1