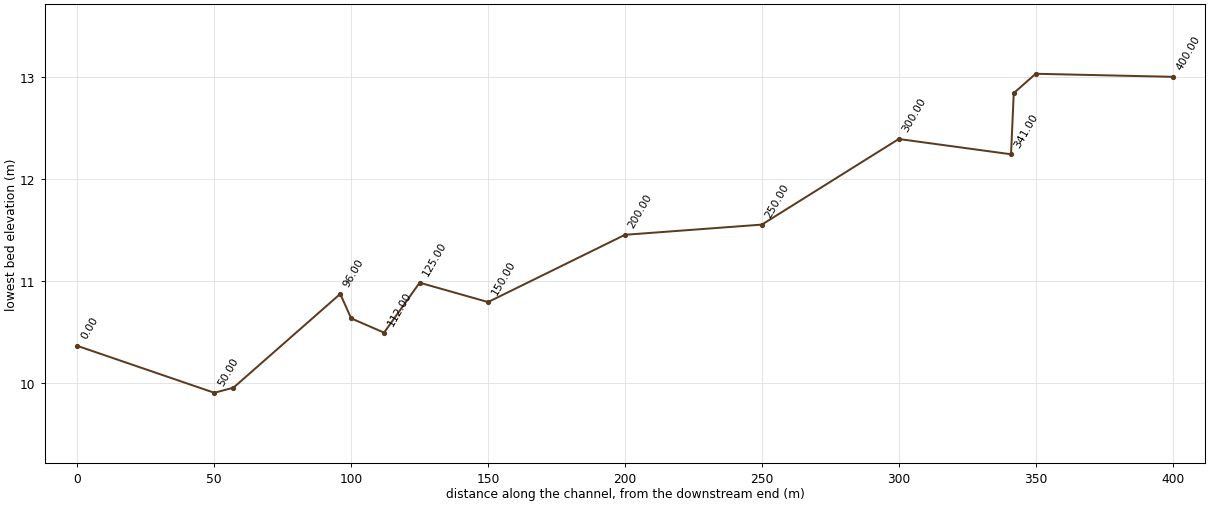
HEC-RAS study NAM.prj: NAMJUN

--- NAM.g01 (geometry) --- (continued)

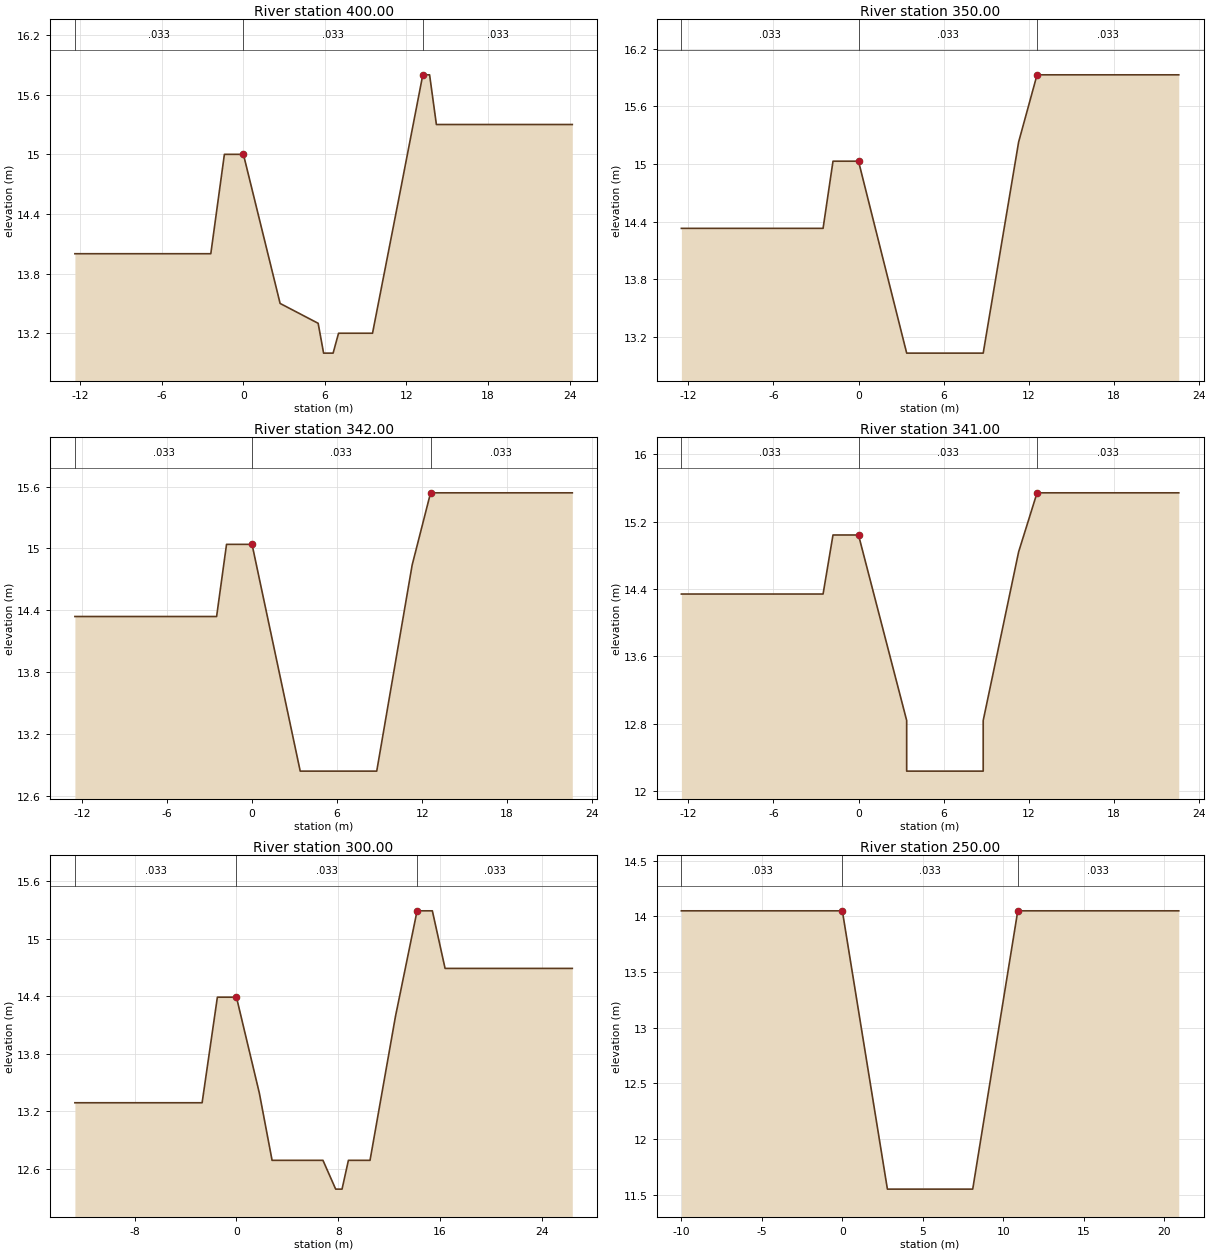
Type RM Length L Ch R = 1 ,400.00  ,50,50,50
BEGIN DESCRIPTION:
8
END DESCRIPTION:
#Sta/Elev= 15
   -12.4      14    -2.4      14    -1.4      15       0      15     2.7    13.5
     5.5    13.3     5.9      13     6.6      13       7    13.2     9.5    13.2
    11.5    14.6    13.2    15.8    13.7    15.8    14.2    15.3    24.2    15.3
#Mann= 3 , 0 , 0
   -12.4    .033       0       0    .033       0    13.2    .033       0
Bank Sta=0,13.2
XS Rating Curve= 0
Exp/Cntr=.3,.1

Type RM Length L Ch R = 1 ,350.00  ,8,8,8
BEGIN DESCRIPTION:
7
END DESCRIPTION:
#Sta/Elev= 9
   -12.5   14.33    -2.5   14.33    -1.8   15.03       0   15.03     3.4   13.03
     8.8   13.03    11.3   15.23    12.6   15.93    22.6   15.93
#Mann= 3 , 0 , 0
   -12.5    .033       0       0    .033       0    12.6    .033       0
Bank Sta=0,12.6
XS Rating Curve= 0
Exp/Cntr=.3,.1

Type RM Length L Ch R = 1 ,342.00  ,1,1,1
BEGIN DESCRIPTION:
6.042
END DESCRIPTION:
#Sta/Elev= 9
   -12.5   14.34    -2.5   14.34    -1.8   15.04       0   15.04     3.4   12.84
     8.8   12.84    11.3   14.84    12.6   15.54    22.6   15.54
#Mann= 3 , 0 , 0
   -12.5    .033       0       0    .033       0    12.6    .033       0
Bank Sta=0,12.6
XS Rating Curve= 0
Exp/Cntr=.3,.1

Type RM Length L Ch R = 1 ,341.00  ,41,41,41
BEGIN DESCRIPTION:
6.041
END DESCRIPTION:
#Sta/Elev= 11
   -12.5   14.34    -2.5   14.34    -1.8   15.04       0   15.04     3.4   12.84
     3.4   12.24     8.8   12.24     8.8   12.84    11.3   14.84    12.6   15.54
    22.6   15.54
#Mann= 3 , 0 , 0
   -12.5    .033       0       0    .033       0    12.6    .033       0
Bank Sta=0,12.6
XS Rating Curve= 0
Exp/Cntr=.3,.1

Type RM Length L Ch R = 1 ,300.00  ,50,50,50
BEGIN DESCRIPTION:
6
END DESCRIPTION:
#Sta/Elev= 16
   -12.7   13.29    -2.7   13.29    -1.5   14.39       0   14.39     1.8   13.39
     2.8   12.69     6.8   12.69     7.8   12.39     8.3   12.39     8.8   12.69
    10.5   12.69    12.5   14.19    14.2   15.29    15.4   15.29    16.4   14.69
    26.4   14.69
#Mann= 3 , 0 , 0
   -12.7    .033       0       0    .033       0    14.2    .033       0
Bank Sta=0,14.2
XS Rating Curve= 0
Exp/Cntr=.3,.1

Type RM Length L Ch R = 1 ,250.00  ,50,50,50
BEGIN DESCRIPTION:
5
END DESCRIPTION:
#Sta/Elev= 6
     -10   14.05       0   14.05     2.8   11.55     8.1   11.55    10.9   14.05
    20.9   14.05
#Mann= 3 , 0 , 0
     -10    .033       0       0    .033       0    10.9    .033       0
Bank Sta=0,10.9
XS Rating Curve= 0
Exp/Cntr=.3,.1

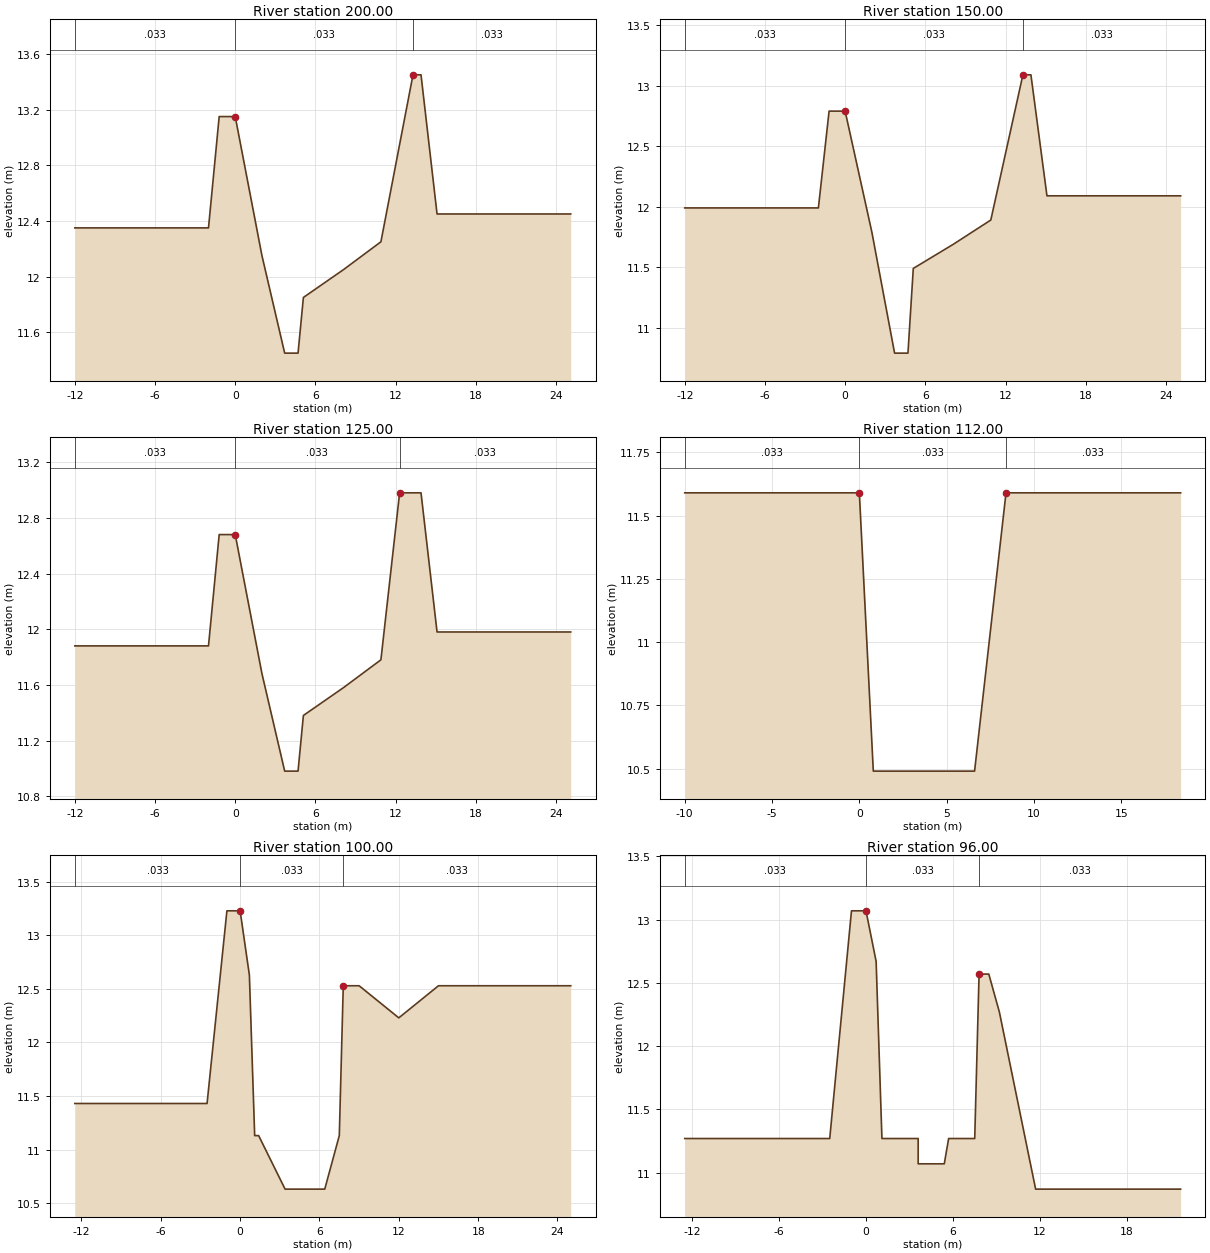
Type RM Length L Ch R = 1 ,200.00  ,50,50,50
BEGIN DESCRIPTION:
4
END DESCRIPTION:
#Sta/Elev= 14
     -12   12.35      -2   12.35    -1.2   13.15       0   13.15       2   12.15
     3.7   11.45     4.7   11.45     5.1   11.85     8.1   12.05    10.9   12.25
    13.3   13.45    13.9   13.45    15.1   12.45    25.1   12.45
#Mann= 3 , 0 , 0
     -12    .033       0       0    .033       0    13.3    .033       0
Bank Sta=0,13.3
XS Rating Curve= 0
Exp/Cntr=.3,.1

Type RM Length L Ch R = 1 ,150.00  ,25,25,25
BEGIN DESCRIPTION:
3
END DESCRIPTION:
#Sta/Elev= 14
     -12   11.99      -2   11.99    -1.2   12.79       0   12.79       2   11.79
     3.7   10.79     4.7   10.79     5.1   11.49     8.1   11.69    10.9   11.89
    13.3   13.09    13.9   13.09    15.1   12.09    25.1   12.09
#Mann= 3 , 0 , 0
     -12    .033       0       0    .033       0    13.3    .033       0
Bank Sta=0,13.3
XS Rating Curve= 0
Exp/Cntr=.3,.1

Type RM Length L Ch R = 1 ,125.00  ,13,13,13
BEGIN DESCRIPTION:
2.025
END DESCRIPTION:
#Sta/Elev= 14
     -12   11.88      -2   11.88    -1.2   12.68       0   12.68       2   11.68
     3.7   10.98     4.7   10.98     5.1   11.38     8.1   11.58    10.9   11.78
    12.3   12.98    13.9   12.98    15.1   11.98    25.1   11.98
#Mann= 3 , 0 , 0
     -12    .033       0       0    .033       0    12.3    .033       0
Bank Sta=0,12.3
XS Rating Curve= 0
Exp/Cntr=.3,.1

Type RM Length L Ch R = 1 ,112.00  ,12,12,12
BEGIN DESCRIPTION:
2.012
END DESCRIPTION:
#Sta/Elev= 6
     -10   11.59       0   11.59      .8   10.49     6.6   10.49     8.4   11.59
    18.4   11.59
#Mann= 3 , 0 , 0
     -10    .033       0       0    .033       0     8.4    .033       0
Bank Sta=0,8.4
XS Rating Curve= 0
Exp/Cntr=.3,.1

Type RM Length L Ch R = 1 ,100.00  ,4,4,4
BEGIN DESCRIPTION:
2
END DESCRIPTION:
#Sta/Elev= 15
   -12.5   11.43    -2.5   11.43      -1   13.23       0   13.23      .7   12.63
     1.1   11.13     1.4   11.13     3.4   10.63     6.4   10.63     7.5   11.13
     7.8   12.53       9   12.53      12   12.23      15   12.53      25   12.53
#Mann= 3 , 0 , 0
   -12.5    .033       0       0    .033       0     7.8    .033       0
Bank Sta=0,7.8
XS Rating Curve= 0
Exp/Cntr=.3,.1

Type RM Length L Ch R = 1 ,96.00   ,39,39,39
BEGIN DESCRIPTION:
1.046
END DESCRIPTION:
#Sta/Elev= 16
   -12.5   11.27    -2.5   11.27      -1   13.07       0   13.07      .7   12.67
     1.1   11.27     3.6   11.27     3.6   11.07     5.4   11.07     5.7   11.27
     7.5   11.27     7.8   12.57    8.47   12.57     9.2   12.27    11.7   10.87
    21.7   10.87
#Mann= 3 , 0 , 0
   -12.5    .033       0       0    .033       0     7.8    .033       0
Bank Sta=0,7.8
XS Rating Curve= 0
Exp/Cntr=.3,.1

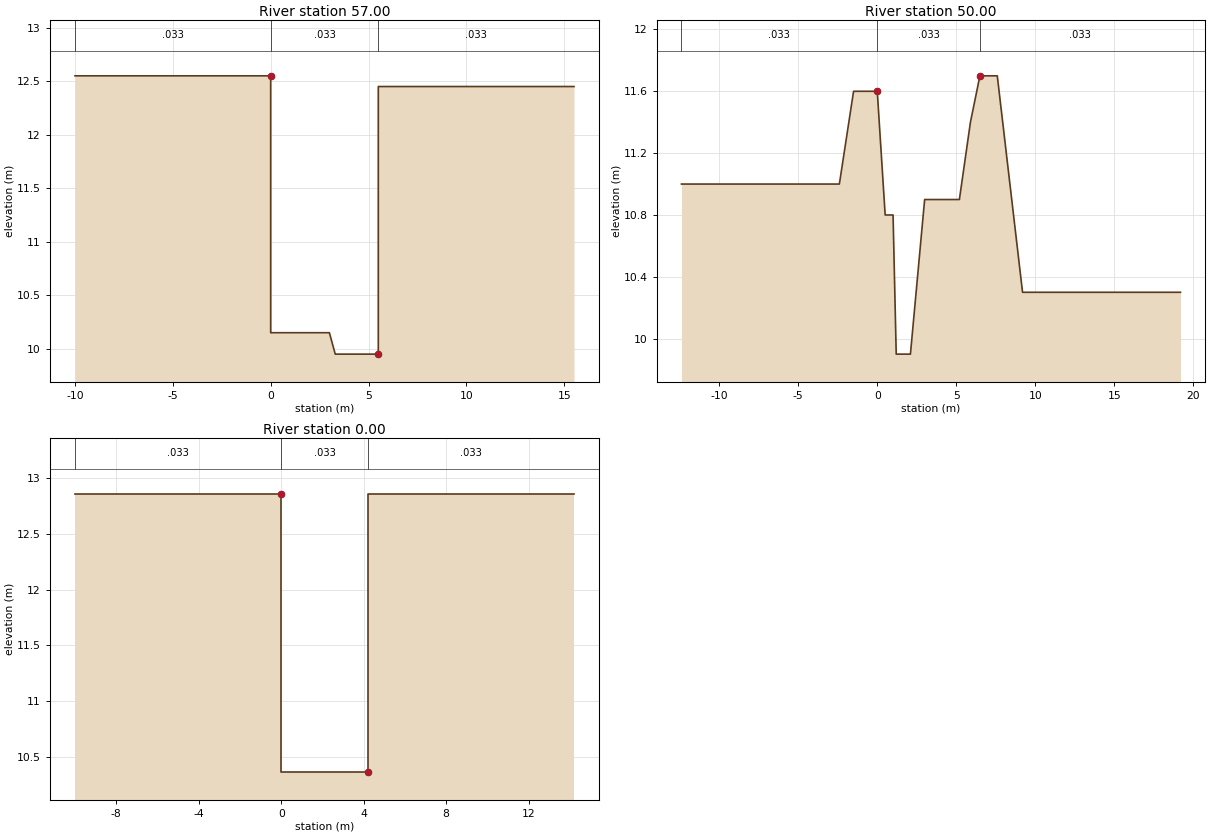
Type RM Length L Ch R = 1 ,57.00   ,7,7,7
BEGIN DESCRIPTION:
1.007
END DESCRIPTION:
#Sta/Elev= 10
     -10   12.55      -5   12.55       0   12.55       0   10.15       3   10.15
     3.3    9.95     5.5    9.95     5.5   12.45    10.5   12.45    15.5   12.45
#Mann= 3 , 0 , 0
     -10    .033       0       0    .033       0     5.5    .033       0
Bank Sta=0,5.5
XS Rating Curve= 0
Exp/Cntr=.3,.1

Type RM Length L Ch R = 1 ,50.00   ,50,50,50
BEGIN DESCRIPTION:
1
END DESCRIPTION:
#Sta/Elev= 15
   -12.4      11    -2.4      11    -1.5    11.6       0    11.6      .5    10.8
       1    10.8     1.2     9.9     2.1     9.9       3    10.9     5.2    10.9
     5.9    11.4     6.5    11.7     7.6    11.7     9.2    10.3    19.2    10.3
#Mann= 3 , 0 , 0
   -12.4    .033       0       0    .033       0     6.5    .033       0
Bank Sta=0,6.5
XS Rating Curve= 0
Exp/Cntr=.3,.1

Type RM Length L Ch R = 1 ,0.00    ,0,0,0
BEGIN DESCRIPTION:
0
END DESCRIPTION:
#Sta/Elev= 6
     -10   12.86       0   12.86       0   10.36     4.2   10.36     4.2   12.86
    14.2   12.86
#Mann= 3 , 0 , 0
     -10    .033       0       0    .033       0     4.2    .033       0
Bank Sta=0,4.2
XS Rating Curve= 0
Exp/Cntr=.3,.1

Chan Stop Cuts=-1