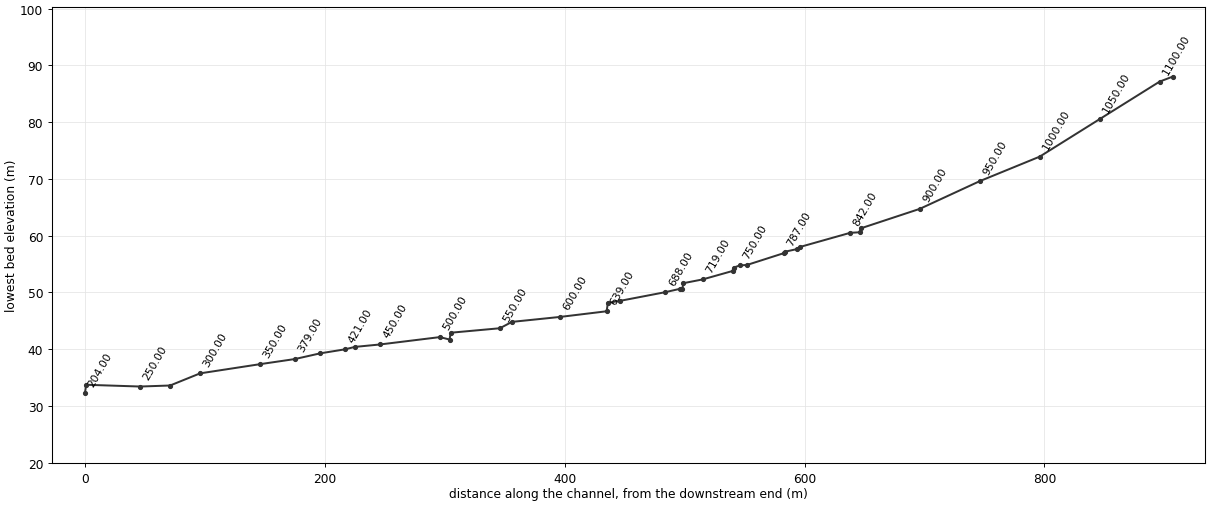
--- WDC.prj (project) ---

Proj Title=WDC
Current Plan=p01
Default Exp/Contr=.3,.1
SI Units
Geom File=g01
Flow File=f01
Plan File=p01
Y Axis Title=Elevation
X Axis Title(PF)=Main Channel Distance
X Axis Title(XS)=Station
BEGIN DESCRIPTION:
           BACK WATER COMPUTATION
      APPLICATION OF HEC-2 BY Samju Construction Engineering
      WOONGDONG-STREEM : 30 YR
END DESCRIPTION:
DSS Export Rating Curves= 0
DSS Export Rating Curve Sorted= 0
DSS Export Volume Flow Curves= 0
DXF OffsetX= 0
DXF OffsetY= 0
DXF ScaleX= 1
DXF ScaleY= 10

--- WDC.p01 (plan) ---

Plan Title=Imported Plan 01
Version=Version 3.0.1  Mar 2001
Short Identifier=Imported Pla
Geom File=g01
Flow File=f01
Subcritical Flow
K Sum by GR= 0
Std Step Tol= 0.003
Critical Tol= 0.003
Num of Std Step Trials= 20
Max Error Tol= 0.1
Flow Tol Ratio= 0.001
Split Flow NTrial= 30
Split Flow Tol= 0.02
Split Flow Ratio= 0.02
Log Output Level= 0
Friction Slope Method= 1
Unsteady Friction Slope Method= 2
Parabolic Critical Depth
Global Vel Dist= 0 , 0 , 0
Global Log Level= 0
CheckData=True
Encroach Param=-1 ,0,0, 0
Computation Interval=1HOUR
Output Interval=1HOUR
Run HTab= 0
Run UNet= 0
Run PostProcess= 0
UNET Theta= 1
UNET ZTol= 0.02
UNET ZSATol= 0.1
UNET MxIter= 20
UNET MaxInSteps= 20
UNET DtIC= 0
UNET DtMin= 0
UNET MaxCRTS= 20
UNET WFStab= 2
UNET SFStab= 1
UNET WFX= 1
UNET SFX= 1
UNET Convert EG Bridges=-1
UNET Use Existing IB Tables=-1
Instantaneous Interval=1HOUR
Write IC File= 0
Write Velocity= 0
Write Detailed= 0

--- WDC.f01 (steady flow) ---

Flow Title=Imported Flow 01
Version=Version 3.0.1  Mar 2001
Number of Profiles= 5
Profile Names=10YR,20YR,30YR,50YR,80YR
River Rch & RM=RIVER-1,Reach-1         ,1111.00
    8.71    9.59   10.11   10.76   11.36
Boundary for River Rch & Prof#=RIVER-1,Reach-1         , 1
Up Type= 0
Dn Type= 3
Dn Slope=.03
Boundary for River Rch & Prof#=RIVER-1,Reach-1         , 2
Up Type= 0
Dn Type= 3
Dn Slope=.03
Boundary for River Rch & Prof#=RIVER-1,Reach-1         , 3
Up Type= 0
Dn Type= 3
Dn Slope=.03
Boundary for River Rch & Prof#=RIVER-1,Reach-1         , 4
Up Type= 0
Dn Type= 3
Dn Slope=.03
Boundary for River Rch & Prof#=RIVER-1,Reach-1         , 5
Up Type= 0
Dn Type= 3
Dn Slope=.03
DSS Import GetInterval= 0
DSS Import GetPeak= 0
DSS Import FillOption= 0

--- WDC.g01 (geometry) ---

Geom Title=Imported Geom 01
Version=Version 3.0.1  Mar 2001

River Reach=RIVER-1         ,Reach-1
Reach XY= 2
              .5             .95              .5             .05

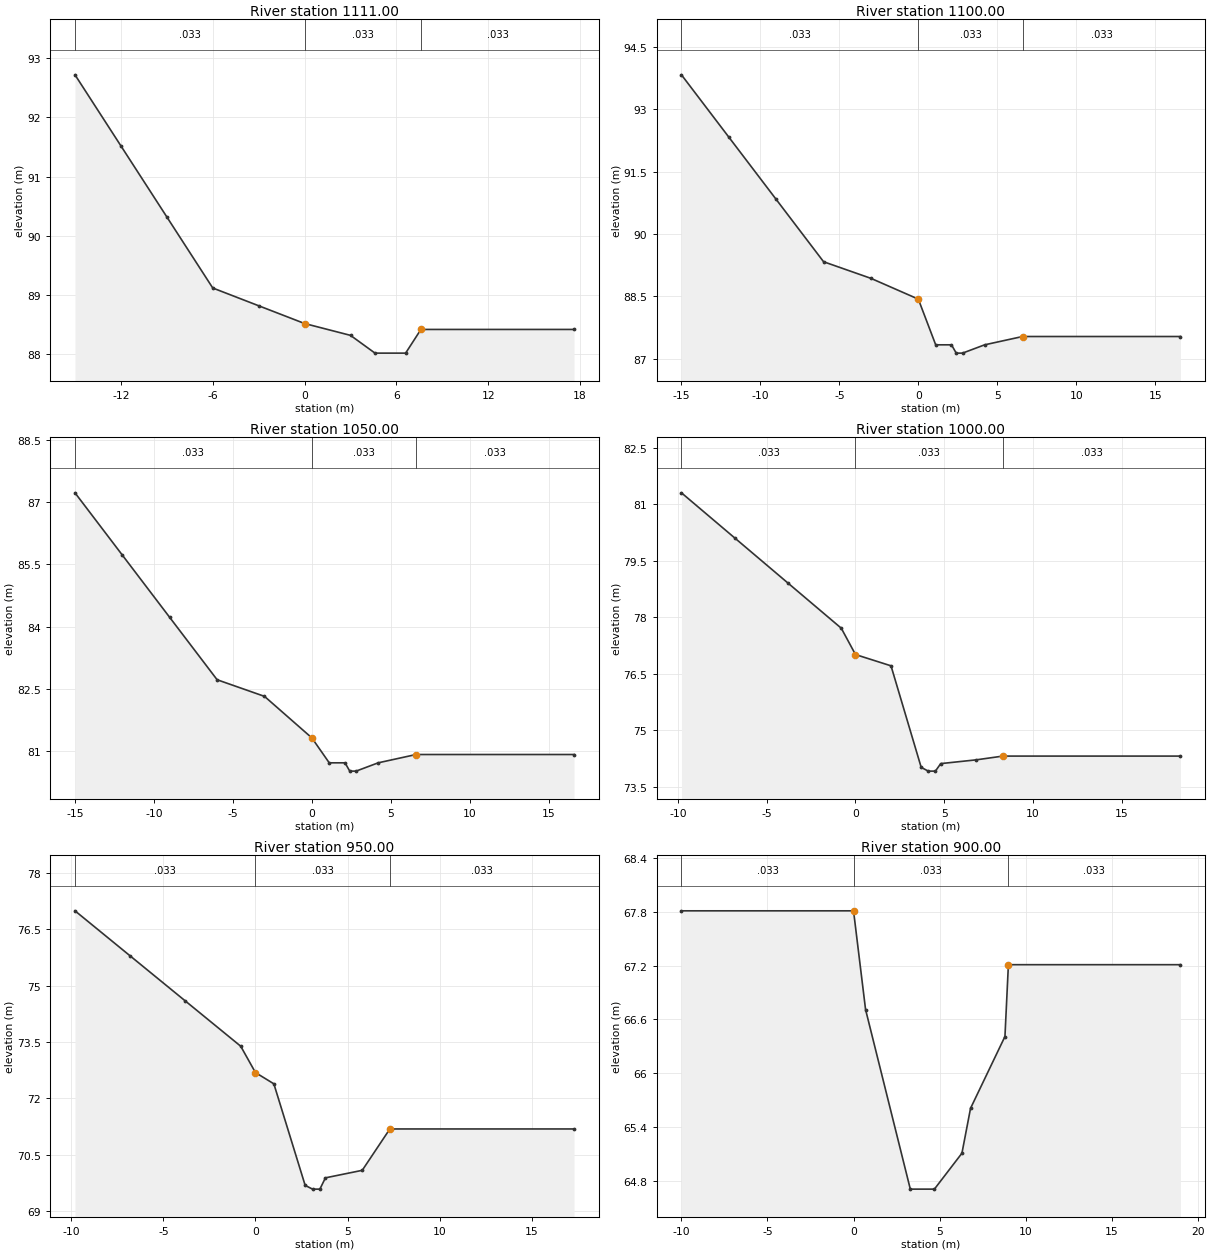
Type RM Length L Ch R = 1 ,1111.00 ,11,11,11
BEGIN DESCRIPTION:
22.011
END DESCRIPTION:
#Sta/Elev= 11
     -15   92.72     -12   91.52      -9   90.32      -6   89.12      -3   88.82
       0   88.52       3   88.32     4.6   88.02     6.6   88.02     7.6   88.42
    17.6   88.42
#Mann= 3 , 0 , 0
     -15    .033       0       0    .033       0     7.6    .033       0
#XS Ineff= 2 , 0
               0   88.52     7.6           88.42
Permanent Ineff=
       F       F
Bank Sta=0,7.6
XS Rating Curve= 0
Exp/Cntr=.3,.1

Type RM Length L Ch R = 1 ,1100.00 ,50,50,50
BEGIN DESCRIPTION:
22
END DESCRIPTION:
#Sta/Elev= 13
     -15   93.83     -12   92.33      -9   90.83      -6   89.33      -3   88.93
       0   88.43     1.1   87.33     2.1   87.33     2.4   87.13     2.8   87.13
     4.2   87.33     6.6   87.53    16.6   87.53
#Mann= 3 , 0 , 0
     -15    .033       0       0    .033       0     6.6    .033       0
#XS Ineff= 2 , 0
               0   88.43     6.6           87.53
Permanent Ineff=
       F       F
Bank Sta=0,6.6
XS Rating Curve= 0
Exp/Cntr=.3,.1

Type RM Length L Ch R = 1 ,1050.00 ,50,50,50
BEGIN DESCRIPTION:
21
END DESCRIPTION:
#Sta/Elev= 13
     -15   87.22     -12   85.72      -9   84.22      -6   82.72      -3   82.32
       0   81.32     1.1   80.72     2.1   80.72     2.4   80.52     2.8   80.52
     4.2   80.72     6.6   80.92    16.6   80.92
#Mann= 3 , 0 , 0
     -15    .033       0       0    .033       0     6.6    .033       0
#XS Ineff= 2 , 0
               0   81.32     6.6           80.92
Permanent Ineff=
       F       F
Bank Sta=0,6.6
XS Rating Curve= 0
Exp/Cntr=.3,.1

Type RM Length L Ch R = 1 ,1000.00 ,50,50,50
BEGIN DESCRIPTION:
20
END DESCRIPTION:
#Sta/Elev= 13
    -9.8   81.31    -6.8   80.11    -3.8   78.91     -.8   77.71       0   77.01
       2   76.71     3.7   74.01     4.1   73.91     4.5   73.91     4.8   74.11
     6.8   74.21     8.3   74.31    18.3   74.31
#Mann= 3 , 0 , 0
    -9.8    .033       0       0    .033       0     8.3    .033       0
#XS Ineff= 2 , 0
               0   77.01     8.3           74.31
Permanent Ineff=
       F       F
Bank Sta=0,8.3
XS Rating Curve= 0
Exp/Cntr=.3,.1

Type RM Length L Ch R = 1 ,950.00  ,50,50,50
BEGIN DESCRIPTION:
19
END DESCRIPTION:
#Sta/Elev= 13
    -9.8   76.99    -6.8   75.79    -3.8   74.59     -.8   73.39       0   72.69
       1   72.39     2.7   69.69     3.1   69.59     3.5   69.59     3.8   69.89
     5.8   70.09     7.3   71.19    17.3   71.19
#Mann= 3 , 0 , 0
    -9.8    .033       0       0    .033       0     7.3    .033       0
#XS Ineff= 2 , 0
               0   72.69     7.3           71.19
Permanent Ineff=
       F       F
Bank Sta=0,7.3
XS Rating Curve= 0
Exp/Cntr=.3,.1

Type RM Length L Ch R = 1 ,900.00  ,49,49,49
BEGIN DESCRIPTION:
18
END DESCRIPTION:
#Sta/Elev= 10
     -10   67.81       0   67.81      .7   66.71     3.3   64.71     4.7   64.71
     6.3   65.11     6.8   65.61     8.8   66.41       9   67.21      19   67.21
#Mann= 3 , 0 , 0
     -10    .033       0       0    .033       0       9    .033       0
#XS Ineff= 2 , 0
               0   67.81       9           67.21
Permanent Ineff=
       F       F
Bank Sta=0,9
XS Rating Curve= 0
Exp/Cntr=.3,.1

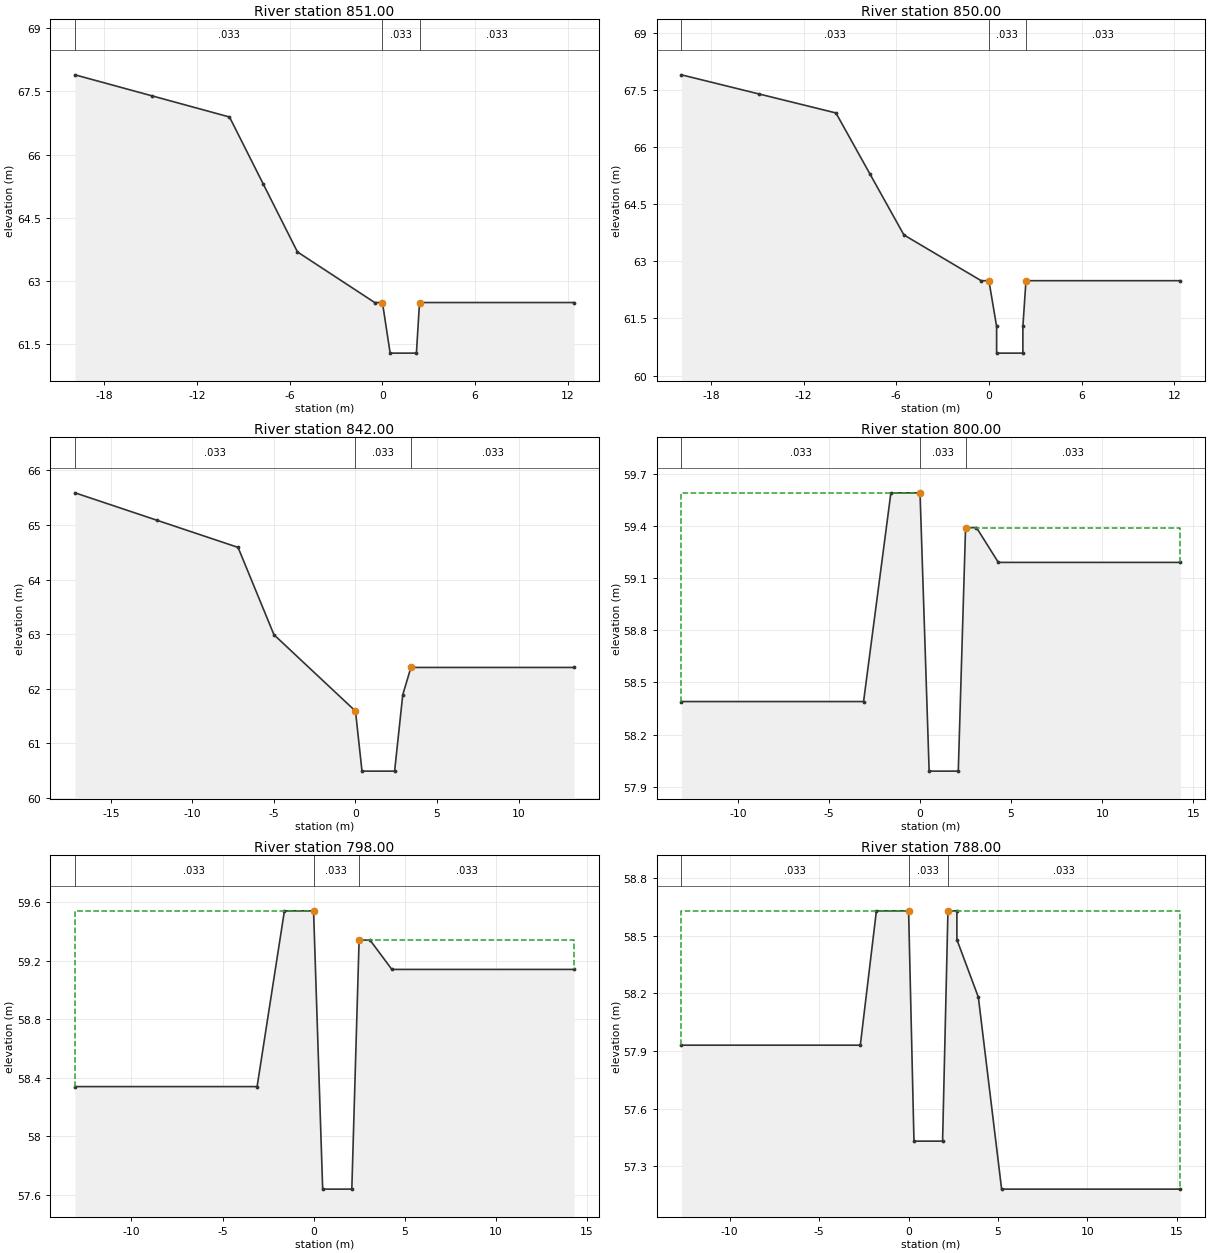
Type RM Length L Ch R = 1 ,851.00  ,1,1,1
BEGIN DESCRIPTION:
17.001
END DESCRIPTION:
#Sta/Elev= 11
   -19.9   67.89   -14.9   67.39    -9.9   66.89    -7.7   65.29    -5.5   63.69
     -.5   62.49       0   62.49      .5   61.29     2.2   61.29     2.4   62.49
    12.4   62.49
#Mann= 3 , 0 , 0
   -19.9    .033       0       0    .033       0     2.4    .033       0
#XS Ineff= 2 , 0
               0   62.49     2.4           62.49
Permanent Ineff=
       F       F
Bank Sta=0,2.4
XS Rating Curve= 0
Exp/Cntr=.3,.1

Type RM Length L Ch R = 1 ,850.00  ,8,8,8
BEGIN DESCRIPTION:
17
END DESCRIPTION:
#Sta/Elev= 13
   -19.9   67.89   -14.9   67.39    -9.9   66.89    -7.7   65.29    -5.5   63.69
     -.5   62.49       0   62.49      .5   61.29      .5   60.59     2.2   60.59
     2.2   61.29     2.4   62.49    12.4   62.49
#Mann= 3 , 0 , 0
   -19.9    .033       0       0    .033       0     2.4    .033       0
#XS Ineff= 2 , 0
               0   62.49     2.4           62.49
Permanent Ineff=
       F       F
Bank Sta=0,2.4
XS Rating Curve= 0
Exp/Cntr=.3,.1

Type RM Length L Ch R = 1 ,842.00  ,42,42,42
BEGIN DESCRIPTION:
16.042
END DESCRIPTION:
#Sta/Elev= 10
   -17.2   65.59   -12.2   65.09    -7.2   64.59      -5   62.99       0   61.59
      .4   60.49     2.4   60.49     2.9   61.89     3.4   62.39    13.4   62.39
#Mann= 3 , 0 , 0
   -17.2    .033       0       0    .033       0     3.4    .033       0
#XS Ineff= 2 , 0
               0   61.59     3.4           62.39
Permanent Ineff=
       F       F
Bank Sta=0,3.4
XS Rating Curve= 0
Exp/Cntr=.3,.1

Type RM Length L Ch R = 1 ,800.00  ,2,2,2
BEGIN DESCRIPTION:
16
END DESCRIPTION:
#Sta/Elev= 10
   -13.1   58.39    -3.1   58.39    -1.6   59.59       0   59.59      .5   57.99
     2.1   57.99     2.5   59.39     3.1   59.39     4.3   59.19    14.3   59.19
#Mann= 3 , 0 , 0
   -13.1    .033       0       0    .033       0     2.5    .033       0
#XS Ineff= 2 , 0
               0   59.59     2.5           59.39
Permanent Ineff=
       F       F
Bank Sta=0,2.5
XS Rating Curve= 0
Exp/Cntr=.3,.1

Type RM Length L Ch R = 1 ,798.00  ,10,10,10
BEGIN DESCRIPTION:
15.048
END DESCRIPTION:
#Sta/Elev= 10
   -13.1   58.34    -3.1   58.34    -1.6   59.54       0   59.54      .5   57.64
     2.1   57.64     2.5   59.34     3.1   59.34     4.3   59.14    14.3   59.14
#Mann= 3 , 0 , 0
   -13.1    .033       0       0    .033       0     2.5    .033       0
#XS Ineff= 2 , 0
               0   59.54     2.5           59.34
Permanent Ineff=
       F       F
Bank Sta=0,2.5
XS Rating Curve= 0
Exp/Cntr=.3,.1

Type RM Length L Ch R = 1 ,788.00  ,1,1,1
BEGIN DESCRIPTION:
15.038
END DESCRIPTION:
#Sta/Elev= 12
   -12.7   57.93    -2.7   57.93    -1.8   58.63       0   58.63      .3   57.43
     1.9   57.43     2.2   58.63     2.7   58.63     2.7   58.48     3.9   58.18
     5.2   57.18    15.2   57.18
#Mann= 3 , 0 , 0
   -12.7    .033       0       0    .033       0     2.2    .033       0
#XS Ineff= 2 , 0
               0   58.63     2.2           58.63
Permanent Ineff=
       F       F
Bank Sta=0,2.2
XS Rating Curve= 0
Exp/Cntr=.3,.1

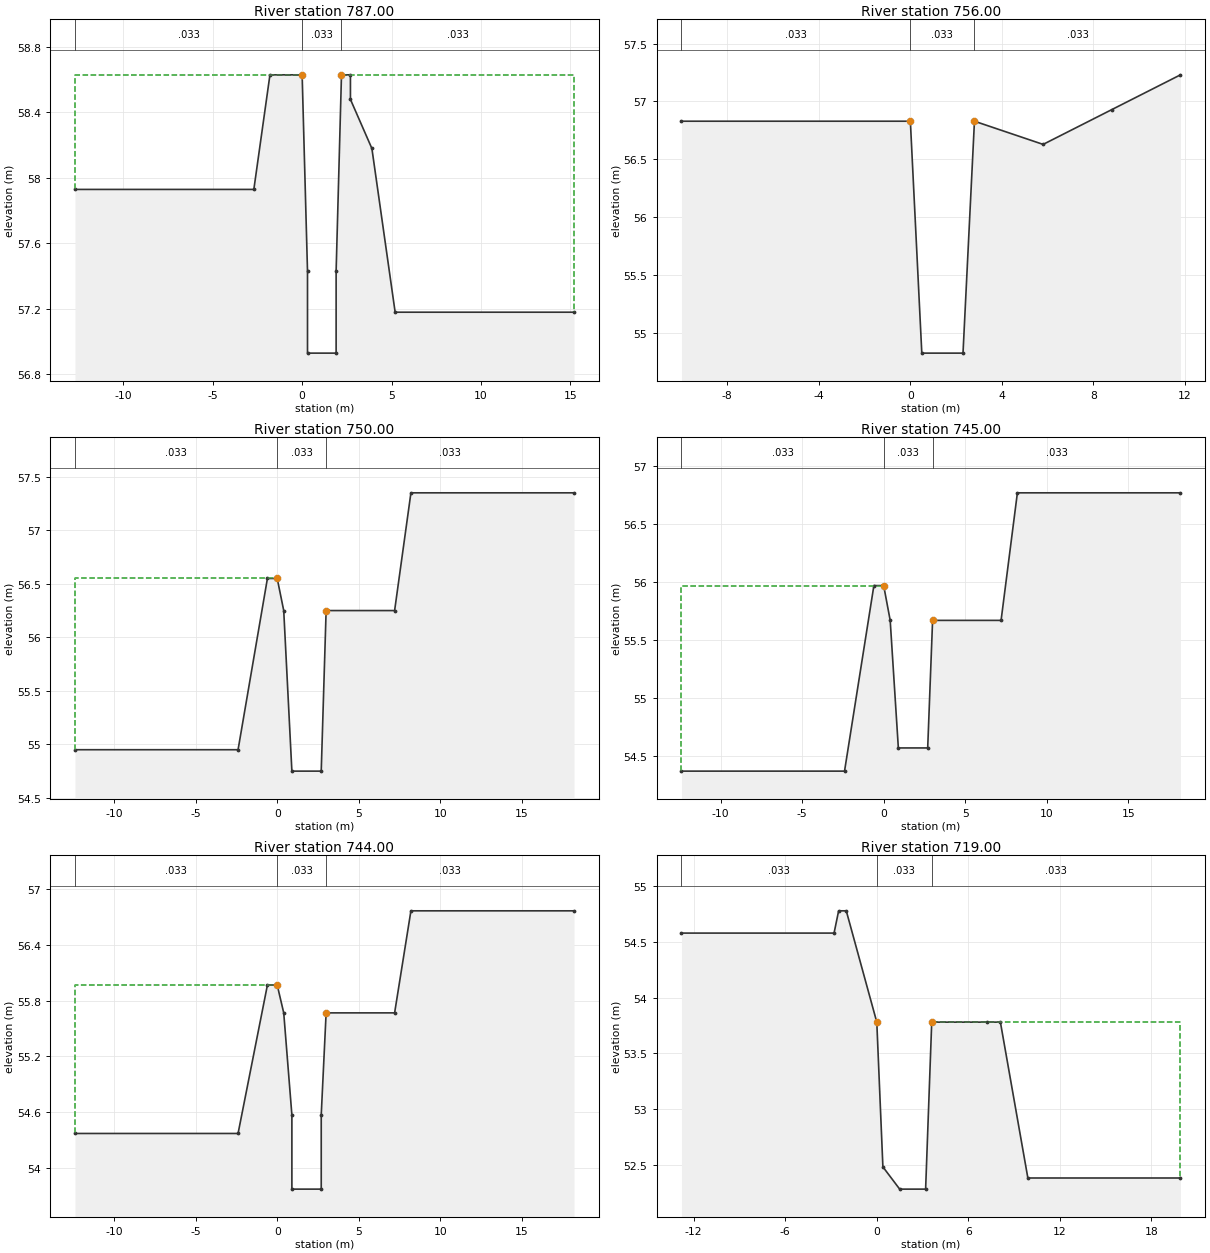
Type RM Length L Ch R = 1 ,787.00  ,31,31,31
BEGIN DESCRIPTION:
15.037
END DESCRIPTION:
#Sta/Elev= 14
   -12.7   57.93    -2.7   57.93    -1.8   58.63       0   58.63      .3   57.43
      .3   56.93     1.9   56.93     1.9   57.43     2.2   58.63     2.7   58.63
     2.7   58.48     3.9   58.18     5.2   57.18    15.2   57.18
#Mann= 3 , 0 , 0
   -12.7    .033       0       0    .033       0     2.2    .033       0
#XS Ineff= 2 , 0
               0   58.63     2.2           58.63
Permanent Ineff=
       F       F
Bank Sta=0,2.2
XS Rating Curve= 0
Exp/Cntr=.3,.1

Type RM Length L Ch R = 1 ,756.00  ,6,6,6
BEGIN DESCRIPTION:
15.006
END DESCRIPTION:
#Sta/Elev= 8
     -10   56.83       0   56.83      .5   54.83     2.3   54.83     2.8   56.83
     5.8   56.63     8.8   56.93    11.8   57.23
#Mann= 3 , 0 , 0
     -10    .033       0       0    .033       0     2.8    .033       0
#XS Ineff= 2 , 0
               0   56.83     2.8           56.83
Permanent Ineff=
       F       F
Bank Sta=0,2.8
XS Rating Curve= 0
Exp/Cntr=.3,.1

Type RM Length L Ch R = 1 ,750.00  ,5,5,5
BEGIN DESCRIPTION:
15
END DESCRIPTION:
#Sta/Elev= 11
   -12.4   54.95    -2.4   54.95     -.6   56.55       0   56.55      .4   56.25
      .9   54.75     2.7   54.75       3   56.25     7.2   56.25     8.2   57.35
    18.2   57.35
#Mann= 3 , 0 , 0
   -12.4    .033       0       0    .033       0       3    .033       0
#XS Ineff= 2 , 0
               0   56.55       3           56.25
Permanent Ineff=
       F       F
Bank Sta=0,3
XS Rating Curve= 0
Exp/Cntr=.3,.1

Type RM Length L Ch R = 1 ,745.00  ,1,1,1
BEGIN DESCRIPTION:
14.045
END DESCRIPTION:
#Sta/Elev= 11
   -12.4   54.37    -2.4   54.37     -.6   55.97       0   55.97      .4   55.67
      .9   54.57     2.7   54.57       3   55.67     7.2   55.67     8.2   56.77
    18.2   56.77
#Mann= 3 , 0 , 0
   -12.4    .033       0       0    .033       0       3    .033       0
#XS Ineff= 2 , 0
               0   55.97       3           55.67
Permanent Ineff=
       F       F
Bank Sta=0,3
XS Rating Curve= 0
Exp/Cntr=.3,.1

Type RM Length L Ch R = 1 ,744.00  ,25,25,25
BEGIN DESCRIPTION:
14.044
END DESCRIPTION:
#Sta/Elev= 13
   -12.4   54.37    -2.4   54.37     -.6   55.97       0   55.97      .4   55.67
      .9   54.57      .9   53.77     2.7   53.77     2.7   54.57       3   55.67
     7.2   55.67     8.2   56.77    18.2   56.77
#Mann= 3 , 0 , 0
   -12.4    .033       0       0    .033       0       3    .033       0
#XS Ineff= 2 , 0
               0   55.97       3           55.67
Permanent Ineff=
       F       F
Bank Sta=0,3
XS Rating Curve= 0
Exp/Cntr=.3,.1

Type RM Length L Ch R = 1 ,719.00  ,16,16,16
BEGIN DESCRIPTION:
14.019
END DESCRIPTION:
#Sta/Elev= 13
   -12.8   54.58    -2.8   54.58    -2.5   54.78      -2   54.78       0   53.78
      .4   52.48     1.5   52.28     3.2   52.28     3.6   53.78     7.2   53.78
     8.1   53.78     9.9   52.38    19.9   52.38
#Mann= 3 , 0 , 0
   -12.8    .033       0       0    .033       0     3.6    .033       0
#XS Ineff= 2 , 0
               0   53.78     3.6           53.78
Permanent Ineff=
       F       F
Bank Sta=0,3.6
XS Rating Curve= 0
Exp/Cntr=.3,.1

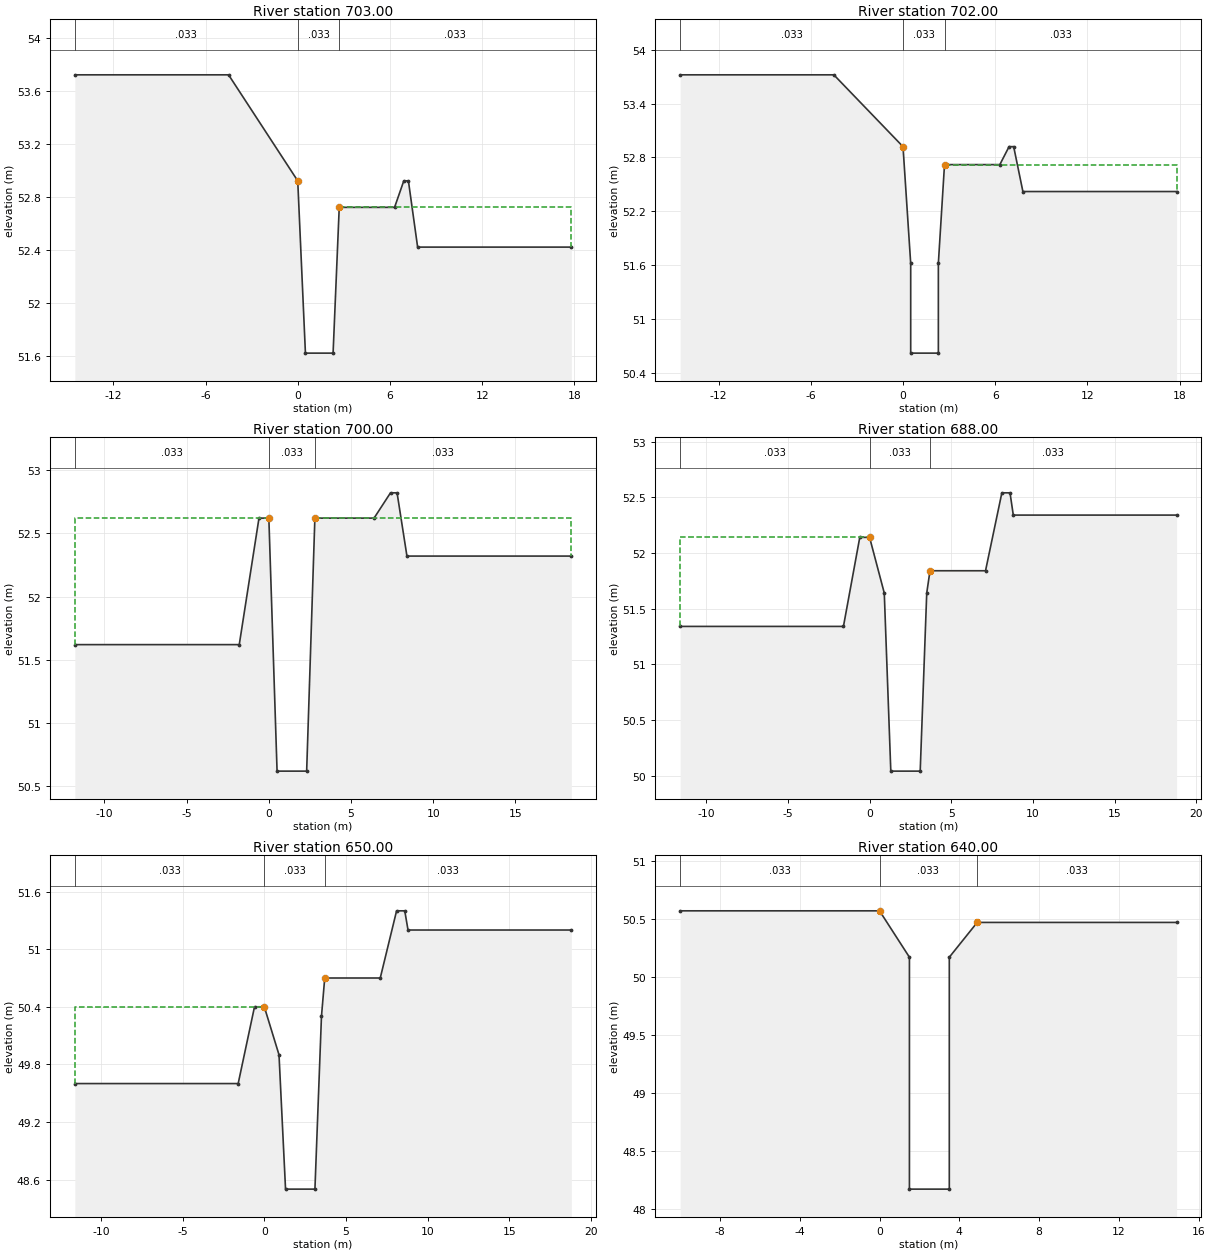
Type RM Length L Ch R = 1 ,703.00  ,1,1,1
BEGIN DESCRIPTION:
14.003
END DESCRIPTION:
#Sta/Elev= 11
   -14.5   53.72    -4.5   53.72       0   52.92      .5   51.62     2.3   51.62
     2.7   52.72     6.3   52.72     6.9   52.92     7.2   52.92     7.8   52.42
    17.8   52.42
#Mann= 3 , 0 , 0
   -14.5    .033       0       0    .033       0     2.7    .033       0
#XS Ineff= 2 , 0
               0   52.92     2.7           52.72
Permanent Ineff=
       F       F
Bank Sta=0,2.7
XS Rating Curve= 0
Exp/Cntr=.3,.1

Type RM Length L Ch R = 1 ,702.00  ,2,2,2
BEGIN DESCRIPTION:
14.002
END DESCRIPTION:
#Sta/Elev= 13
   -14.5   53.72    -4.5   53.72       0   52.92      .5   51.62      .5   50.62
     2.3   50.62     2.3   51.62     2.7   52.72     6.3   52.72     6.9   52.92
     7.2   52.92     7.8   52.42    17.8   52.42
#Mann= 3 , 0 , 0
   -14.5    .033       0       0    .033       0     2.7    .033       0
#XS Ineff= 2 , 0
               0   52.92     2.7           52.72
Permanent Ineff=
       F       F
Bank Sta=0,2.7
XS Rating Curve= 0
Exp/Cntr=.3,.1

Type RM Length L Ch R = 1 ,700.00  ,12,12,12
BEGIN DESCRIPTION:
14
END DESCRIPTION:
#Sta/Elev= 12
   -11.8   51.62    -1.8   51.62     -.6   52.62       0   52.62      .5   50.62
     2.3   50.62     2.8   52.62     6.4   52.62     7.4   52.82     7.8   52.82
     8.4   52.32    18.4   52.32
#Mann= 3 , 0 , 0
   -11.8    .033       0       0    .033       0     2.8    .033       0
#XS Ineff= 2 , 0
               0   52.62     2.8           52.62
Permanent Ineff=
       F       F
Bank Sta=0,2.8
XS Rating Curve= 0
Exp/Cntr=.3,.1

Type RM Length L Ch R = 1 ,688.00  ,38,38,38
BEGIN DESCRIPTION:
13.038
END DESCRIPTION:
#Sta/Elev= 14
   -11.6   51.34    -1.6   51.34     -.6   52.14       0   52.14      .9   51.64
     1.3   50.04     3.1   50.04     3.5   51.64     3.7   51.84     7.1   51.84
     8.1   52.54     8.6   52.54     8.8   52.34    18.8   52.34
#Mann= 3 , 0 , 0
   -11.6    .033       0       0    .033       0     3.7    .033       0
#XS Ineff= 2 , 0
               0   52.14     3.7           51.84
Permanent Ineff=
       F       F
Bank Sta=0,3.7
XS Rating Curve= 0
Exp/Cntr=.3,.1

Type RM Length L Ch R = 1 ,650.00  ,10,10,10
BEGIN DESCRIPTION:
13
END DESCRIPTION:
#Sta/Elev= 14
   -11.6    49.6    -1.6    49.6     -.6    50.4       0    50.4      .9    49.9
     1.3    48.5     3.1    48.5     3.5    50.3     3.7    50.7     7.1    50.7
     8.1    51.4     8.6    51.4     8.8    51.2    18.8    51.2
#Mann= 3 , 0 , 0
   -11.6    .033       0       0    .033       0     3.7    .033       0
#XS Ineff= 2 , 0
               0    50.4     3.7            50.7
Permanent Ineff=
       F       F
Bank Sta=0,3.7
XS Rating Curve= 0
Exp/Cntr=.3,.1

Type RM Length L Ch R = 1 ,640.00  ,1,1,1
BEGIN DESCRIPTION:
12.04
END DESCRIPTION:
#Sta/Elev= 8
     -10   50.57       0   50.57     1.5   50.17     1.5   48.17     3.5   48.17
     3.5   50.17     4.9   50.47    14.9   50.47
#Mann= 3 , 0 , 0
     -10    .033       0       0    .033       0     4.9    .033       0
#XS Ineff= 2 , 0
               0   50.57     4.9           50.47
Permanent Ineff=
       F       F
Bank Sta=0,4.9
XS Rating Curve= 0
Exp/Cntr=.3,.1

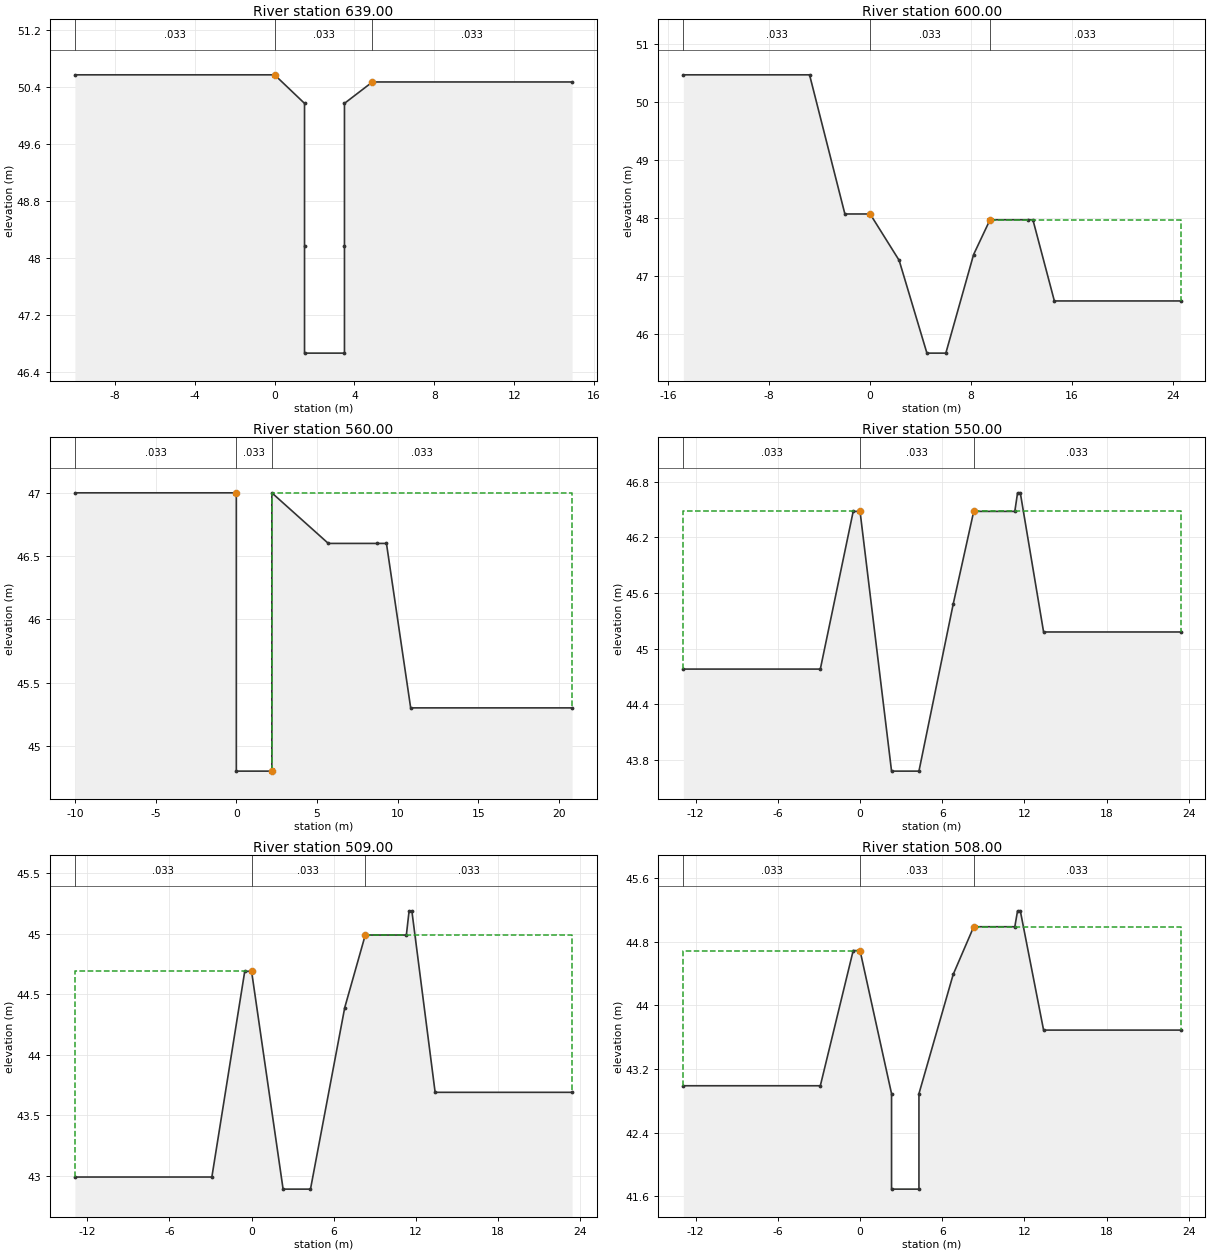
Type RM Length L Ch R = 1 ,639.00  ,39,39,39
BEGIN DESCRIPTION:
12.039
END DESCRIPTION:
#Sta/Elev= 10
     -10   50.57       0   50.57     1.5   50.17     1.5   48.17     1.5   46.67
     3.5   46.67     3.5   48.17     3.5   50.17     4.9   50.47    14.9   50.47
#Mann= 3 , 0 , 0
     -10    .033       0       0    .033       0     4.9    .033       0
#XS Ineff= 2 , 0
               0   50.57     4.9           50.47
Permanent Ineff=
       F       F
Bank Sta=0,4.9
XS Rating Curve= 0
Exp/Cntr=.3,.1

Type RM Length L Ch R = 1 ,600.00  ,40,40,40
BEGIN DESCRIPTION:
12
END DESCRIPTION:
#Sta/Elev= 13
   -14.8   50.47    -4.8   50.47      -2   48.07       0   48.07     2.3   47.27
     4.5   45.67       6   45.67     8.2   47.37     9.5   47.97    12.5   47.97
    12.9   47.97    14.6   46.57    24.6   46.57
#Mann= 3 , 0 , 0
   -14.8    .033       0       0    .033       0     9.5    .033       0
#XS Ineff= 2 , 0
               0   48.07     9.5           47.97
Permanent Ineff=
       F       F
Bank Sta=0,9.5
XS Rating Curve= 0
Exp/Cntr=.3,.1

Type RM Length L Ch R = 1 ,560.00  ,10,10,10
BEGIN DESCRIPTION:
11.01
END DESCRIPTION:
#Sta/Elev= 10
     -10      47       0      47       0    44.8     2.2    44.8     2.2      47
     5.7    46.6     8.7    46.6     9.3    46.6    10.8    45.3    20.8    45.3
#Mann= 3 , 0 , 0
     -10    .033       0       0    .033       0     2.2    .033       0
#XS Ineff= 2 , 0
               0      47     2.2              47
Permanent Ineff=
       F       F
Bank Sta=0,2.2
XS Rating Curve= 0
Exp/Cntr=.3,.1

Type RM Length L Ch R = 1 ,550.00  ,41,41,41
BEGIN DESCRIPTION:
11
END DESCRIPTION:
#Sta/Elev= 13
   -12.9   44.78    -2.9   44.78     -.5   46.48       0   46.48     2.3   43.68
     4.3   43.68     6.8   45.48     8.3   46.48    11.3   46.48    11.5   46.68
    11.7   46.68    13.4   45.18    23.4   45.18
#Mann= 3 , 0 , 0
   -12.9    .033       0       0    .033       0     8.3    .033       0
#XS Ineff= 2 , 0
               0   46.48     8.3           46.48
Permanent Ineff=
       F       F
Bank Sta=0,8.3
XS Rating Curve= 0
Exp/Cntr=.3,.1

Type RM Length L Ch R = 1 ,509.00  ,1,1,1
BEGIN DESCRIPTION:
10.009
END DESCRIPTION:
#Sta/Elev= 13
   -12.9   42.99    -2.9   42.99     -.5   44.69       0   44.69     2.3   42.89
     4.3   42.89     6.8   44.39     8.3   44.99    11.3   44.99    11.5   45.19
    11.7   45.19    13.4   43.69    23.4   43.69
#Mann= 3 , 0 , 0
   -12.9    .033       0       0    .033       0     8.3    .033       0
#XS Ineff= 2 , 0
               0   44.69     8.3           44.99
Permanent Ineff=
       F       F
Bank Sta=0,8.3
XS Rating Curve= 0
Exp/Cntr=.3,.1

Type RM Length L Ch R = 1 ,508.00  ,8,8,8
BEGIN DESCRIPTION:
10.008
END DESCRIPTION:
#Sta/Elev= 15
   -12.9   42.99    -2.9   42.99     -.5   44.69       0   44.69     2.3   42.89
     2.3   41.69     4.3   41.69     4.3   42.89     6.8   44.39     8.3   44.99
    11.3   44.99    11.5   45.19    11.7   45.19    13.4   43.69    23.4   43.69
#Mann= 3 , 0 , 0
   -12.9    .033       0       0    .033       0     8.3    .033       0
#XS Ineff= 2 , 0
               0   44.69     8.3           44.99
Permanent Ineff=
       F       F
Bank Sta=0,8.3
XS Rating Curve= 0
Exp/Cntr=.3,.1

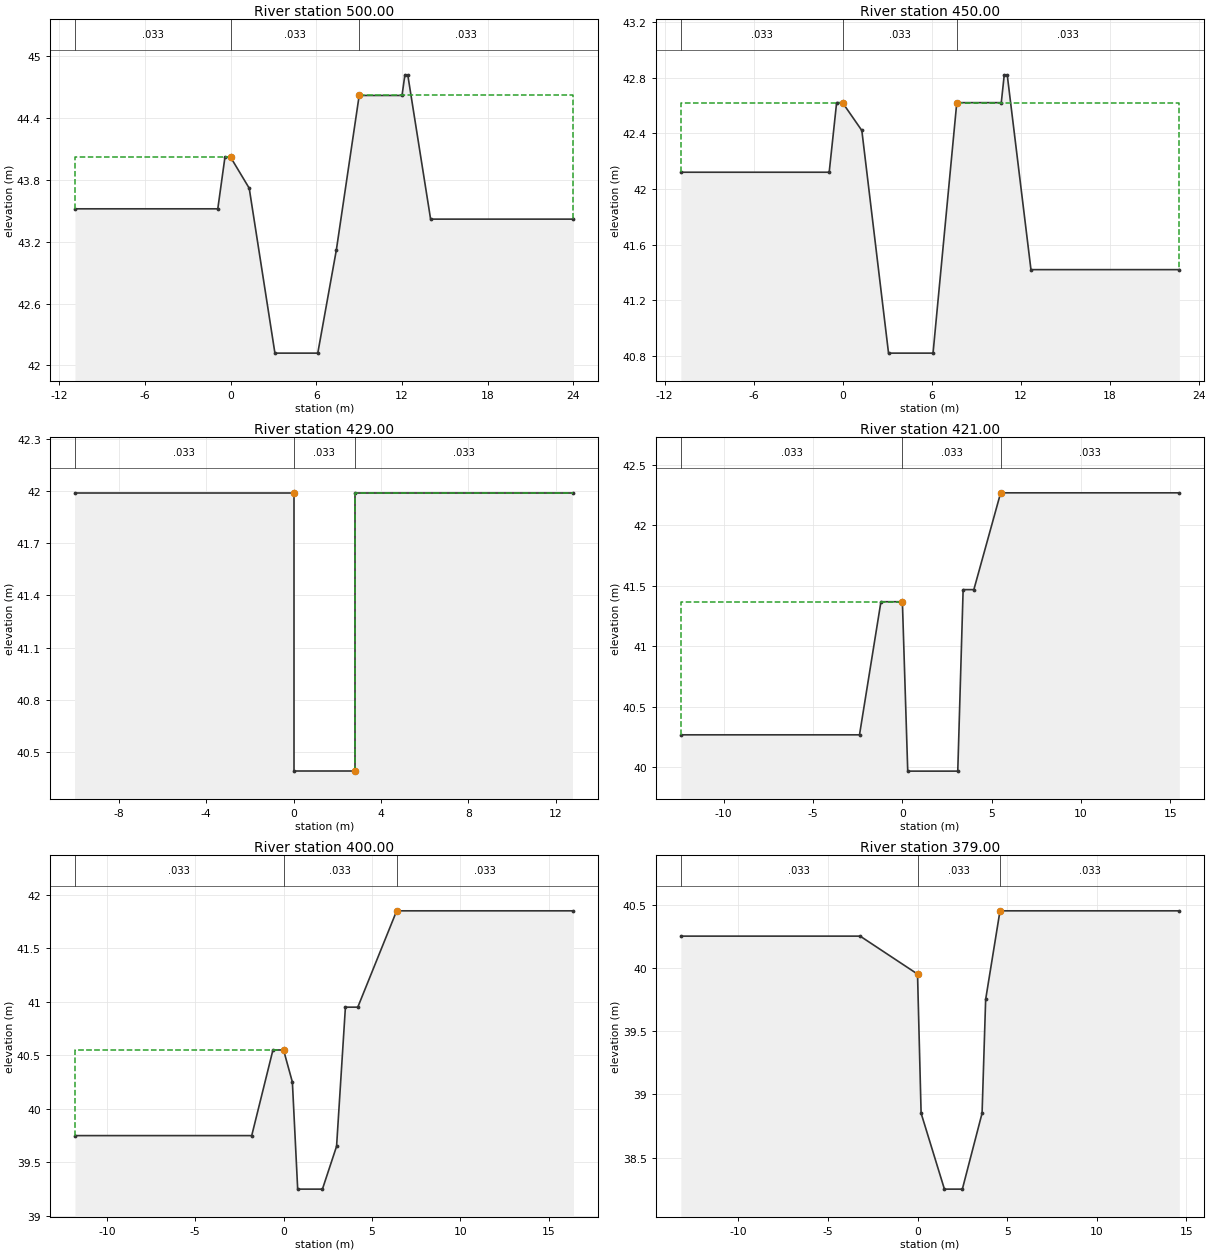
Type RM Length L Ch R = 1 ,500.00  ,50,50,50
BEGIN DESCRIPTION:
10
END DESCRIPTION:
#Sta/Elev= 14
   -10.9   43.52     -.9   43.52     -.4   44.02       0   44.02     1.3   43.72
     3.1   42.12     6.1   42.12     7.4   43.12       9   44.62      12   44.62
    12.2   44.82    12.4   44.82      14   43.42      24   43.42
#Mann= 3 , 0 , 0
   -10.9    .033       0       0    .033       0       9    .033       0
#XS Ineff= 2 , 0
               0   44.02       9           44.62
Permanent Ineff=
       F       F
Bank Sta=0,9
XS Rating Curve= 0
Exp/Cntr=.3,.1

Type RM Length L Ch R = 1 ,450.00  ,21,21,21
BEGIN DESCRIPTION:
9
END DESCRIPTION:
#Sta/Elev= 13
   -10.9   42.12     -.9   42.12     -.4   42.62       0   42.62     1.3   42.42
     3.1   40.82     6.1   40.82     7.7   42.62    10.7   42.62    10.9   42.82
    11.1   42.82    12.7   41.42    22.7   41.42
#Mann= 3 , 0 , 0
   -10.9    .033       0       0    .033       0     7.7    .033       0
#XS Ineff= 2 , 0
               0   42.62     7.7           42.62
Permanent Ineff=
       F       F
Bank Sta=0,7.7
XS Rating Curve= 0
Exp/Cntr=.3,.1

Type RM Length L Ch R = 1 ,429.00  ,8,8,8
BEGIN DESCRIPTION:
8.029
END DESCRIPTION:
#Sta/Elev= 6
     -10   41.99       0   41.99       0   40.39     2.8   40.39     2.8   41.99
    12.8   41.99
#Mann= 3 , 0 , 0
     -10    .033       0       0    .033       0     2.8    .033       0
#XS Ineff= 2 , 0
               0   41.99     2.8           41.99
Permanent Ineff=
       F       F
Bank Sta=0,2.8
XS Rating Curve= 0
Exp/Cntr=.3,.1

Type RM Length L Ch R = 1 ,421.00  ,21,21,21
BEGIN DESCRIPTION:
8.021
END DESCRIPTION:
#Sta/Elev= 10
   -12.4   40.27    -2.4   40.27    -1.2   41.37       0   41.37      .3   39.97
     3.1   39.97     3.4   41.47       4   41.47     5.5   42.27    15.5   42.27
#Mann= 3 , 0 , 0
   -12.4    .033       0       0    .033       0     5.5    .033       0
#XS Ineff= 2 , 0
               0   41.37     5.5           42.27
Permanent Ineff=
       F       F
Bank Sta=0,5.5
XS Rating Curve= 0
Exp/Cntr=.3,.1

Type RM Length L Ch R = 1 ,400.00  ,21,21,21
BEGIN DESCRIPTION:
8
END DESCRIPTION:
#Sta/Elev= 12
   -11.8   39.75    -1.8   39.75     -.6   40.55       0   40.55      .5   40.25
      .8   39.25     2.2   39.25       3   39.65     3.5   40.95     4.2   40.95
     6.4   41.85    16.4   41.85
#Mann= 3 , 0 , 0
   -11.8    .033       0       0    .033       0     6.4    .033       0
#XS Ineff= 2 , 0
               0   40.55     6.4           41.85
Permanent Ineff=
       F       F
Bank Sta=0,6.4
XS Rating Curve= 0
Exp/Cntr=.3,.1

Type RM Length L Ch R = 1 ,379.00  ,29,29,29
BEGIN DESCRIPTION:
7.029
END DESCRIPTION:
#Sta/Elev= 10
   -13.2   40.25    -3.2   40.25       0   39.95      .2   38.85     1.5   38.25
     2.5   38.25     3.6   38.85     3.8   39.75     4.6   40.45    14.6   40.45
#Mann= 3 , 0 , 0
   -13.2    .033       0       0    .033       0     4.6    .033       0
#XS Ineff= 2 , 0
               0   39.95     4.6           40.45
Permanent Ineff=
       F       F
Bank Sta=0,4.6
XS Rating Curve= 0
Exp/Cntr=.3,.1

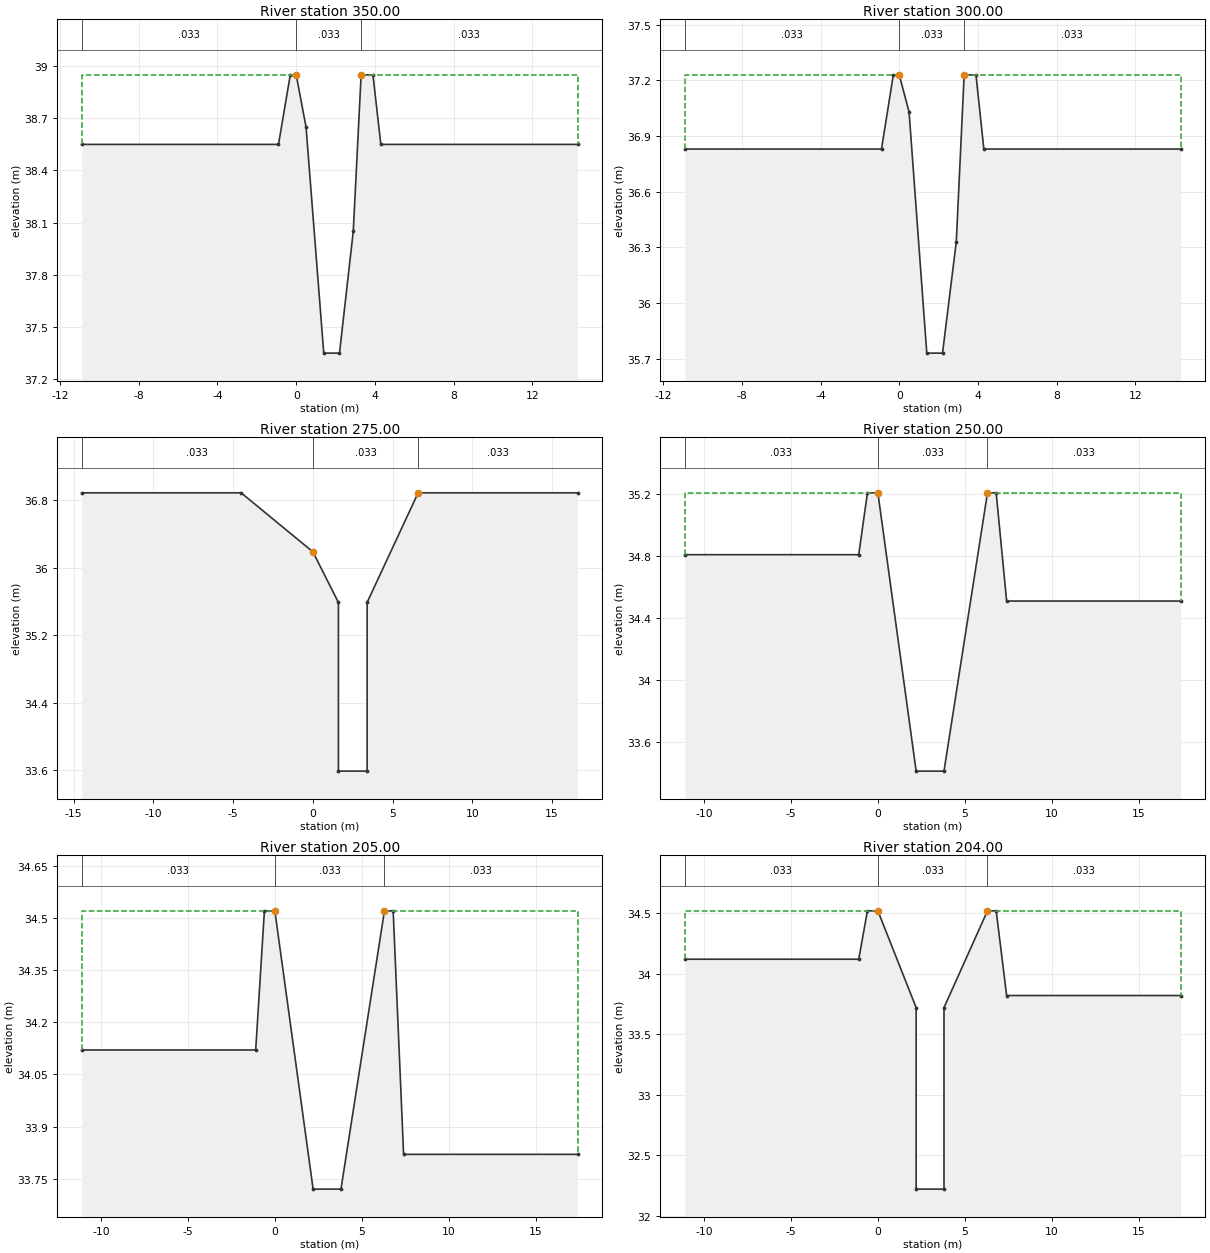
Type RM Length L Ch R = 1 ,350.00  ,50,50,50
BEGIN DESCRIPTION:
7
END DESCRIPTION:
#Sta/Elev= 12
   -10.9   38.55     -.9   38.55     -.3   38.95       0   38.95      .5   38.65
     1.4   37.35     2.2   37.35     2.9   38.05     3.3   38.95     3.9   38.95
     4.3   38.55    14.3   38.55
#Mann= 3 , 0 , 0
   -10.9    .033       0       0    .033       0     3.3    .033       0
#XS Ineff= 2 , 0
               0   38.95     3.3           38.95
Permanent Ineff=
       F       F
Bank Sta=0,3.3
XS Rating Curve= 0
Exp/Cntr=.3,.1

Type RM Length L Ch R = 1 ,300.00  ,25,25,25
BEGIN DESCRIPTION:
6
END DESCRIPTION:
#Sta/Elev= 12
   -10.9   36.83     -.9   36.83     -.3   37.23       0   37.23      .5   37.03
     1.4   35.73     2.2   35.73     2.9   36.33     3.3   37.23     3.9   37.23
     4.3   36.83    14.3   36.83
#Mann= 3 , 0 , 0
   -10.9    .033       0       0    .033       0     3.3    .033       0
#XS Ineff= 2 , 0
               0   37.23     3.3           37.23
Permanent Ineff=
       F       F
Bank Sta=0,3.3
XS Rating Curve= 0
Exp/Cntr=.3,.1

Type RM Length L Ch R = 1 ,275.00  ,25,25,25
BEGIN DESCRIPTION:
5.025
END DESCRIPTION:
#Sta/Elev= 9
   -14.5   36.89    -4.5   36.89       0   36.19     1.6   35.59     1.6   33.59
     3.4   33.59     3.4   35.59     6.6   36.89    16.6   36.89
#Mann= 3 , 0 , 0
   -14.5    .033       0       0    .033       0     6.6    .033       0
#XS Ineff= 2 , 0
               0   36.19     6.6           36.89
Permanent Ineff=
       F       F
Bank Sta=0,6.6
XS Rating Curve= 0
Exp/Cntr=.3,.1

Type RM Length L Ch R = 1 ,250.00  ,45,45,45
BEGIN DESCRIPTION:
5
END DESCRIPTION:
#Sta/Elev= 10
   -11.1   34.81    -1.1   34.81     -.6   35.21       0   35.21     2.2   33.41
     3.8   33.41     6.3   35.21     6.8   35.21     7.4   34.51    17.4   34.51
#Mann= 3 , 0 , 0
   -11.1    .033       0       0    .033       0     6.3    .033       0
#XS Ineff= 2 , 0
               0   35.21     6.3           35.21
Permanent Ineff=
       F       F
Bank Sta=0,6.3
XS Rating Curve= 0
Exp/Cntr=.3,.1

Type RM Length L Ch R = 1 ,205.00  ,1,1,1
BEGIN DESCRIPTION:
4.005
END DESCRIPTION:
#Sta/Elev= 10
   -11.1   34.12    -1.1   34.12     -.6   34.52       0   34.52     2.2   33.72
     3.8   33.72     6.3   34.52     6.8   34.52     7.4   33.82    17.4   33.82
#Mann= 3 , 0 , 0
   -11.1    .033       0       0    .033       0     6.3    .033       0
#XS Ineff= 2 , 0
               0   34.52     6.3           34.52
Permanent Ineff=
       F       F
Bank Sta=0,6.3
XS Rating Curve= 0
Exp/Cntr=.3,.1

Type RM Length L Ch R = 1 ,204.00  ,4,4,4
BEGIN DESCRIPTION:
4.004
END DESCRIPTION:
#Sta/Elev= 12
   -11.1   34.12    -1.1   34.12     -.6   34.52       0   34.52     2.2   33.72
     2.2   32.22     3.8   32.22     3.8   33.72     6.3   34.52     6.8   34.52
     7.4   33.82    17.4   33.82
#Mann= 3 , 0 , 0
   -11.1    .033       0       0    .033       0     6.3    .033       0
#XS Ineff= 2 , 0
               0   34.52     6.3           34.52
Permanent Ineff=
       F       F
Bank Sta=0,6.3
XS Rating Curve= 0
Exp/Cntr=.3,.1