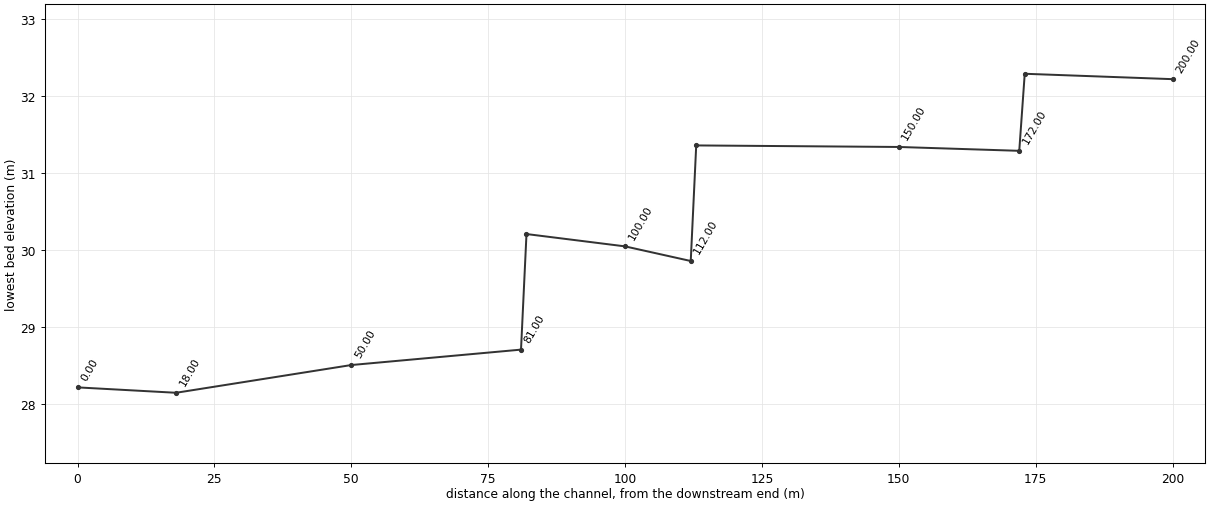
HEC-RAS study WDC.prj: WDC

--- WDC.g01 (geometry) --- (continued)

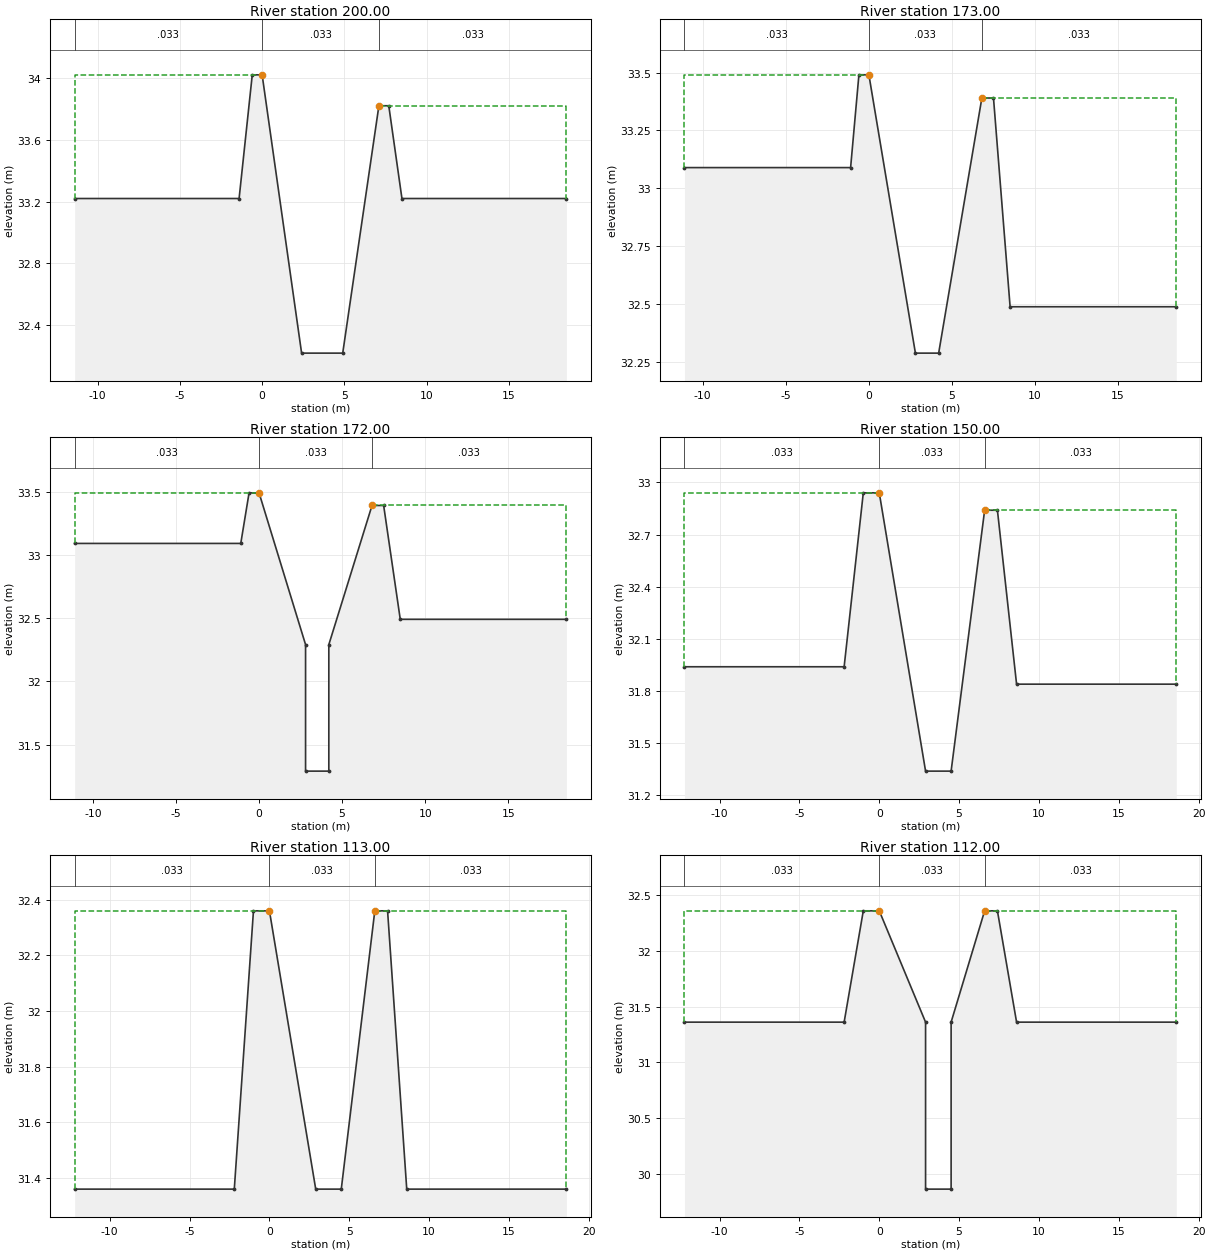
Type RM Length L Ch R = 1 ,200.00  ,27,27,27
BEGIN DESCRIPTION:
4
END DESCRIPTION:
#Sta/Elev= 10
   -11.4   33.22    -1.4   33.22     -.6   34.02       0   34.02     2.4   32.22
     4.9   32.22     7.1   33.82     7.7   33.82     8.5   33.22    18.5   33.22
#Mann= 3 , 0 , 0
   -11.4    .033       0       0    .033       0     7.1    .033       0
#XS Ineff= 2 , 0
               0   34.02     7.1           33.82
Permanent Ineff=
       F       F
Bank Sta=0,7.1
XS Rating Curve= 0
Exp/Cntr=.3,.1

Type RM Length L Ch R = 1 ,173.00  ,1,1,1
BEGIN DESCRIPTION:
3.023
END DESCRIPTION:
#Sta/Elev= 10
   -11.1   33.09    -1.1   33.09     -.6   33.49       0   33.49     2.8   32.29
     4.2   32.29     6.8   33.39     7.5   33.39     8.5   32.49    18.5   32.49
#Mann= 3 , 0 , 0
   -11.1    .033       0       0    .033       0     6.8    .033       0
#XS Ineff= 2 , 0
               0   33.49     6.8           33.39
Permanent Ineff=
       F       F
Bank Sta=0,6.8
XS Rating Curve= 0
Exp/Cntr=.3,.1

Type RM Length L Ch R = 1 ,172.00  ,22,22,22
BEGIN DESCRIPTION:
3.022
END DESCRIPTION:
#Sta/Elev= 12
   -11.1   33.09    -1.1   33.09     -.6   33.49       0   33.49     2.8   32.29
     2.8   31.29     4.2   31.29     4.2   32.29     6.8   33.39     7.5   33.39
     8.5   32.49    18.5   32.49
#Mann= 3 , 0 , 0
   -11.1    .033       0       0    .033       0     6.8    .033       0
#XS Ineff= 2 , 0
               0   33.49     6.8           33.39
Permanent Ineff=
       F       F
Bank Sta=0,6.8
XS Rating Curve= 0
Exp/Cntr=.3,.1

Type RM Length L Ch R = 1 ,150.00  ,37,37,37
BEGIN DESCRIPTION:
3
END DESCRIPTION:
#Sta/Elev= 10
   -12.2   31.94    -2.2   31.94      -1   32.94       0   32.94     2.9   31.34
     4.5   31.34     6.6   32.84     7.4   32.84     8.6   31.84    18.6   31.84
#Mann= 3 , 0 , 0
   -12.2    .033       0       0    .033       0     6.6    .033       0
#XS Ineff= 2 , 0
               0   32.94     6.6           32.84
Permanent Ineff=
       F       F
Bank Sta=0,6.6
XS Rating Curve= 0
Exp/Cntr=.3,.1

Type RM Length L Ch R = 1 ,113.00  ,1,1,1
BEGIN DESCRIPTION:
2.013
END DESCRIPTION:
#Sta/Elev= 10
   -12.2   31.36    -2.2   31.36      -1   32.36       0   32.36     2.9   31.36
     4.5   31.36     6.6   32.36     7.4   32.36     8.6   31.36    18.6   31.36
#Mann= 3 , 0 , 0
   -12.2    .033       0       0    .033       0     6.6    .033       0
#XS Ineff= 2 , 0
               0   32.36     6.6           32.36
Permanent Ineff=
       F       F
Bank Sta=0,6.6
XS Rating Curve= 0
Exp/Cntr=.3,.1

Type RM Length L Ch R = 1 ,112.00  ,12,12,12
BEGIN DESCRIPTION:
2.012
END DESCRIPTION:
#Sta/Elev= 12
   -12.2   31.36    -2.2   31.36      -1   32.36       0   32.36     2.9   31.36
     2.9   29.86     4.5   29.86     4.5   31.36     6.6   32.36     7.4   32.36
     8.6   31.36    18.6   31.36
#Mann= 3 , 0 , 0
   -12.2    .033       0       0    .033       0     6.6    .033       0
#XS Ineff= 2 , 0
               0   32.36     6.6           32.36
Permanent Ineff=
       F       F
Bank Sta=0,6.6
XS Rating Curve= 0
Exp/Cntr=.3,.1

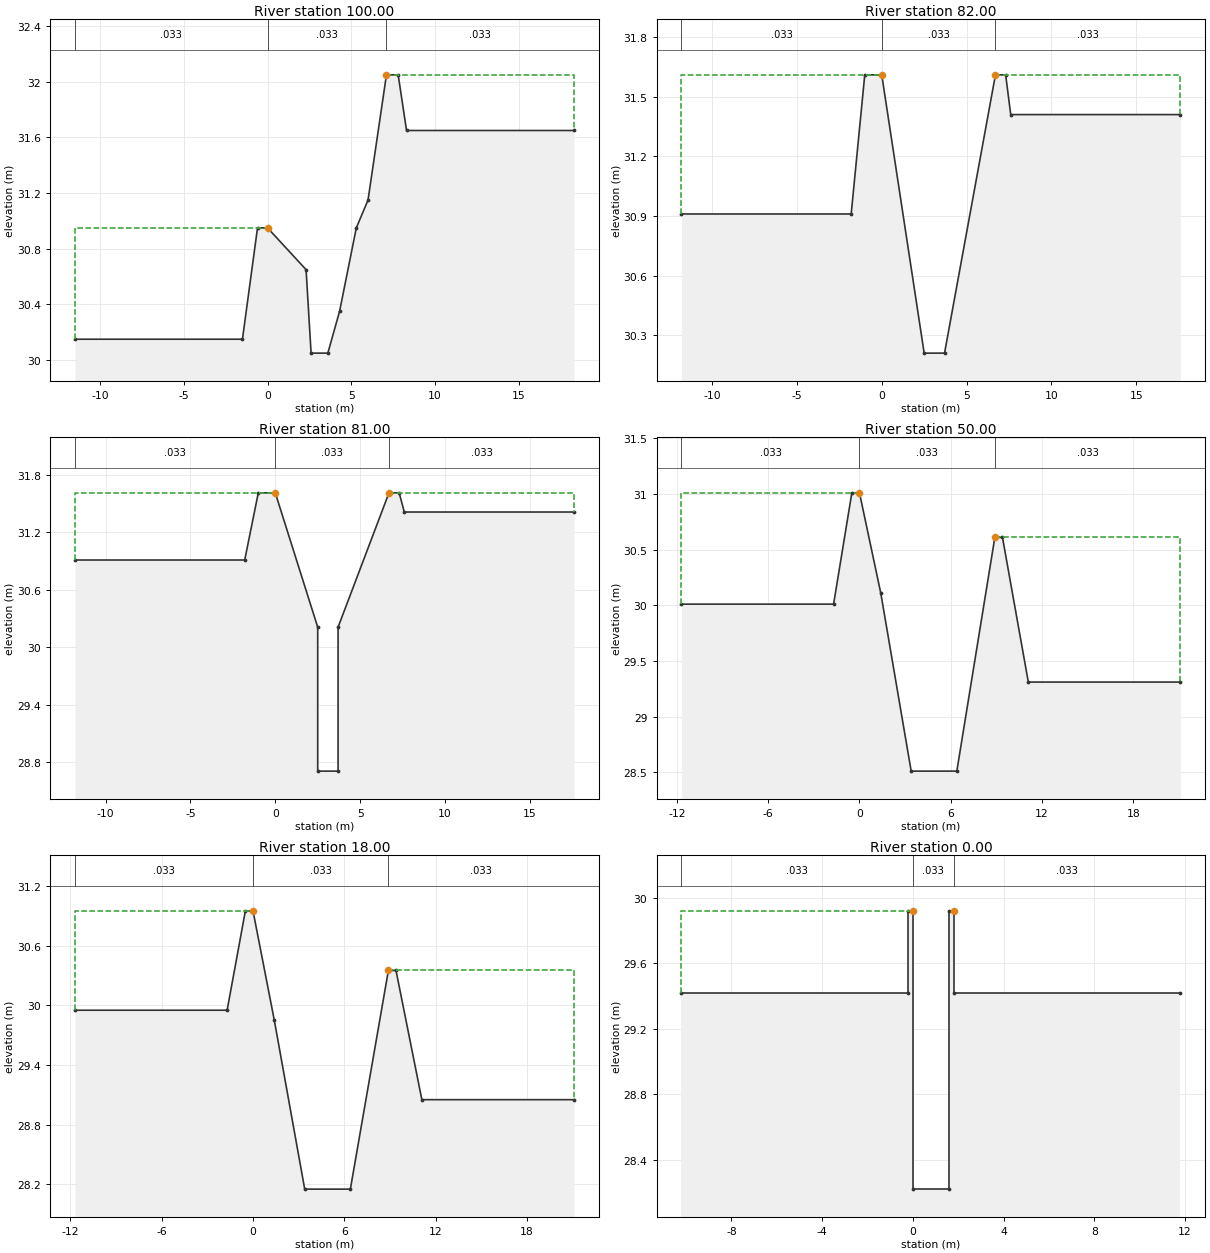
Type RM Length L Ch R = 1 ,100.00  ,18,18,18
BEGIN DESCRIPTION:
2
END DESCRIPTION:
#Sta/Elev= 14
   -11.5   30.15    -1.5   30.15     -.6   30.95       0   30.95     2.3   30.65
     2.6   30.05     3.6   30.05     4.3   30.35     5.3   30.95       6   31.15
     7.1   32.05     7.8   32.05     8.3   31.65    18.3   31.65
#Mann= 3 , 0 , 0
   -11.5    .033       0       0    .033       0     7.1    .033       0
#XS Ineff= 2 , 0
               0   30.95     7.1           32.05
Permanent Ineff=
       F       F
Bank Sta=0,7.1
XS Rating Curve= 0
Exp/Cntr=.3,.1

Type RM Length L Ch R = 1 ,82.00   ,1,1,1
BEGIN DESCRIPTION:
1.032
END DESCRIPTION:
#Sta/Elev= 10
   -11.8   30.91    -1.8   30.91      -1   31.61       0   31.61     2.5   30.21
     3.7   30.21     6.7   31.61     7.3   31.61     7.6   31.41    17.6   31.41
#Mann= 3 , 0 , 0
   -11.8    .033       0       0    .033       0     6.7    .033       0
#XS Ineff= 2 , 0
               0   31.61     6.7           31.61
Permanent Ineff=
       F       F
Bank Sta=0,6.7
XS Rating Curve= 0
Exp/Cntr=.3,.1

Type RM Length L Ch R = 1 ,81.00   ,31,31,31
BEGIN DESCRIPTION:
1.031
END DESCRIPTION:
#Sta/Elev= 12
   -11.8   30.91    -1.8   30.91      -1   31.61       0   31.61     2.5   30.21
     2.5   28.71     3.7   28.71     3.7   30.21     6.7   31.61     7.3   31.61
     7.6   31.41    17.6   31.41
#Mann= 3 , 0 , 0
   -11.8    .033       0       0    .033       0     6.7    .033       0
#XS Ineff= 2 , 0
               0   31.61     6.7           31.61
Permanent Ineff=
       F       F
Bank Sta=0,6.7
XS Rating Curve= 0
Exp/Cntr=.3,.1

Type RM Length L Ch R = 1 ,50.00   ,32,32,32
BEGIN DESCRIPTION:
1
END DESCRIPTION:
#Sta/Elev= 11
   -11.7   30.01    -1.7   30.01     -.5   31.01       0   31.01     1.4   30.11
     3.4   28.51     6.4   28.51     8.9   30.61     9.4   30.61    11.1   29.31
    21.1   29.31
#Mann= 3 , 0 , 0
   -11.7    .033       0       0    .033       0     8.9    .033       0
#XS Ineff= 2 , 0
               0   31.01     8.9           30.61
Permanent Ineff=
       F       F
Bank Sta=0,8.9
XS Rating Curve= 0
Exp/Cntr=.3,.1

Type RM Length L Ch R = 1 ,18.00   ,18,18,18
BEGIN DESCRIPTION:
0.018
END DESCRIPTION:
#Sta/Elev= 11
   -11.7   29.95    -1.7   29.95     -.5   30.95       0   30.95     1.4   29.85
     3.4   28.15     6.4   28.15     8.9   30.35     9.4   30.35    11.1   29.05
    21.1   29.05
#Mann= 3 , 0 , 0
   -11.7    .033       0       0    .033       0     8.9    .033       0
#XS Ineff= 2 , 0
               0   30.95     8.9           30.35
Permanent Ineff=
       F       F
Bank Sta=0,8.9
XS Rating Curve= 0
Exp/Cntr=.3,.1

Type RM Length L Ch R = 1 ,0.00    ,0,0,0
BEGIN DESCRIPTION:
0
END DESCRIPTION:
#Sta/Elev= 10
   -10.2   29.42     -.2   29.42     -.2   29.92       0   29.92       0   28.22
     1.6   28.22     1.6   29.92     1.8   29.92     1.8   29.42    11.8   29.42
#Mann= 3 , 0 , 0
   -10.2    .033       0       0    .033       0     1.8    .033       0
#XS Ineff= 2 , 0
               0   29.92     1.8           29.42
Permanent Ineff=
       F       F
Bank Sta=0,1.8
XS Rating Curve= 0
Exp/Cntr=.3,.1

Chan Stop Cuts=-1