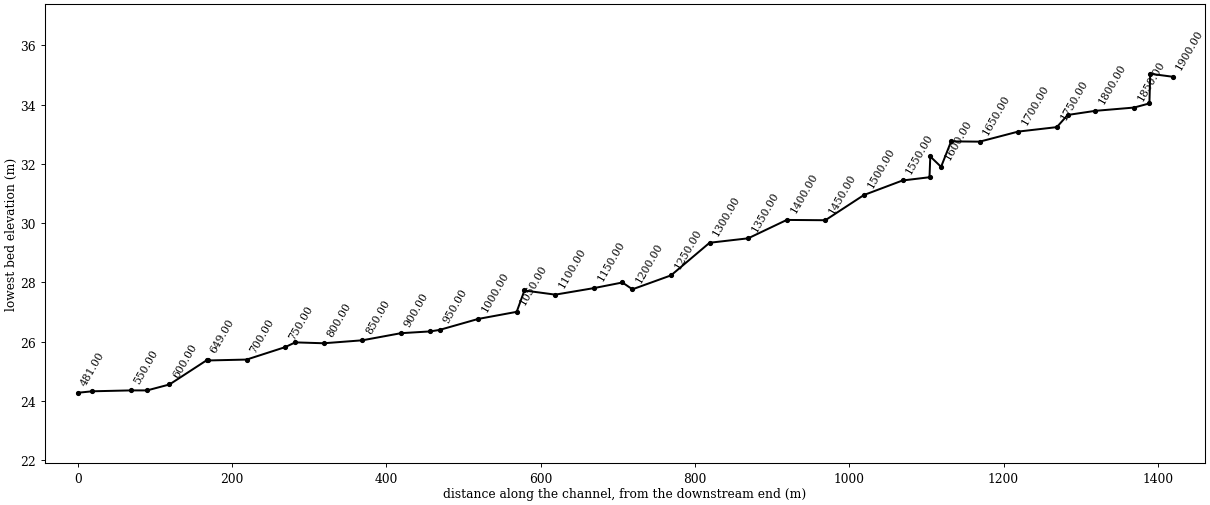
--- DONG.prj (project) ---

Proj Title=DONG
Current Plan=p01
Default Exp/Contr=.3,.1
SI Units
Geom File=g01
Flow File=f01
Plan File=p01
Y Axis Title=Elevation
X Axis Title(PF)=Main Channel Distance
X Axis Title(XS)=Station
BEGIN DESCRIPTION:
           BACK WATER COMPUTATION
      APPLICATION OF HEC-2 BY Samju Construction Engineering
      DONGSIL-STREEM : 30 YR
END DESCRIPTION:
DSS Export Rating Curves= 0
DSS Export Rating Curve Sorted= 0
DSS Export Volume Flow Curves= 0
DXF OffsetX= 0
DXF OffsetY= 0
DXF ScaleX= 1
DXF ScaleY= 10

--- DONG.p01 (plan) ---

Plan Title=Imported Plan 01
Version=Version 3.0.1  Mar 2001
Short Identifier=Imported Pla
Geom File=g01
Flow File=f01
Subcritical Flow
K Sum by GR= 0
Std Step Tol= 0.003
Critical Tol= 0.003
Num of Std Step Trials= 20
Max Error Tol= 0.1
Flow Tol Ratio= 0.001
Split Flow NTrial= 30
Split Flow Tol= 0.02
Split Flow Ratio= 0.02
Log Output Level= 0
Friction Slope Method= 1
Unsteady Friction Slope Method= 2
Parabolic Critical Depth
Global Vel Dist= 0 , 0 , 0
Global Log Level= 0
CheckData=True
Encroach Param=-1 ,0,0, 0
Computation Interval=1HOUR
Output Interval=1HOUR
Run HTab= 0
Run UNet= 0
Run PostProcess= 0
UNET Theta= 1
UNET ZTol= 0.02
UNET ZSATol= 0.1
UNET MxIter= 20
UNET MaxInSteps= 20
UNET DtIC= 0
UNET DtMin= 0
UNET MaxCRTS= 20
UNET WFStab= 2
UNET SFStab= 1
UNET WFX= 1
UNET SFX= 1
UNET Convert EG Bridges=-1
UNET Use Existing IB Tables=-1
Instantaneous Interval=1HOUR
Write IC File= 0
Write Velocity= 0
Write Detailed= 0

--- DONG.f01 (steady flow) ---

Flow Title=Imported Flow 01
Version=Version 3.0.1  Mar 2001
Number of Profiles= 5
Profile Names=10YR,20YR,30YR,50YR,80YR
River Rch & RM=RIVER-1,Reach-1         ,1900.00
   39.19   43.19   45.53   48.48    51.2
River Rch & RM=RIVER-1,Reach-1         ,1000.00
   49.79    54.9   57.89   61.66   65.12
Boundary for River Rch & Prof#=RIVER-1,Reach-1         , 1
Up Type= 0
Dn Type= 3
Dn Slope=.022
Boundary for River Rch & Prof#=RIVER-1,Reach-1         , 2
Up Type= 0
Dn Type= 3
Dn Slope=.022
Boundary for River Rch & Prof#=RIVER-1,Reach-1         , 3
Up Type= 0
Dn Type= 3
Dn Slope=.022
Boundary for River Rch & Prof#=RIVER-1,Reach-1         , 4
Up Type= 0
Dn Type= 3
Dn Slope=.022
Boundary for River Rch & Prof#=RIVER-1,Reach-1         , 5
Up Type= 0
Dn Type= 3
Dn Slope=.022
DSS Import GetInterval= 0
DSS Import GetPeak= 0
DSS Import FillOption= 0

--- DONG.g01 (geometry) ---

Geom Title=Imported Geom 01
Version=Version 3.0.1  Mar 2001

River Reach=RIVER-1         ,Reach-1
Reach XY= 2
              .5             .95              .5             .05

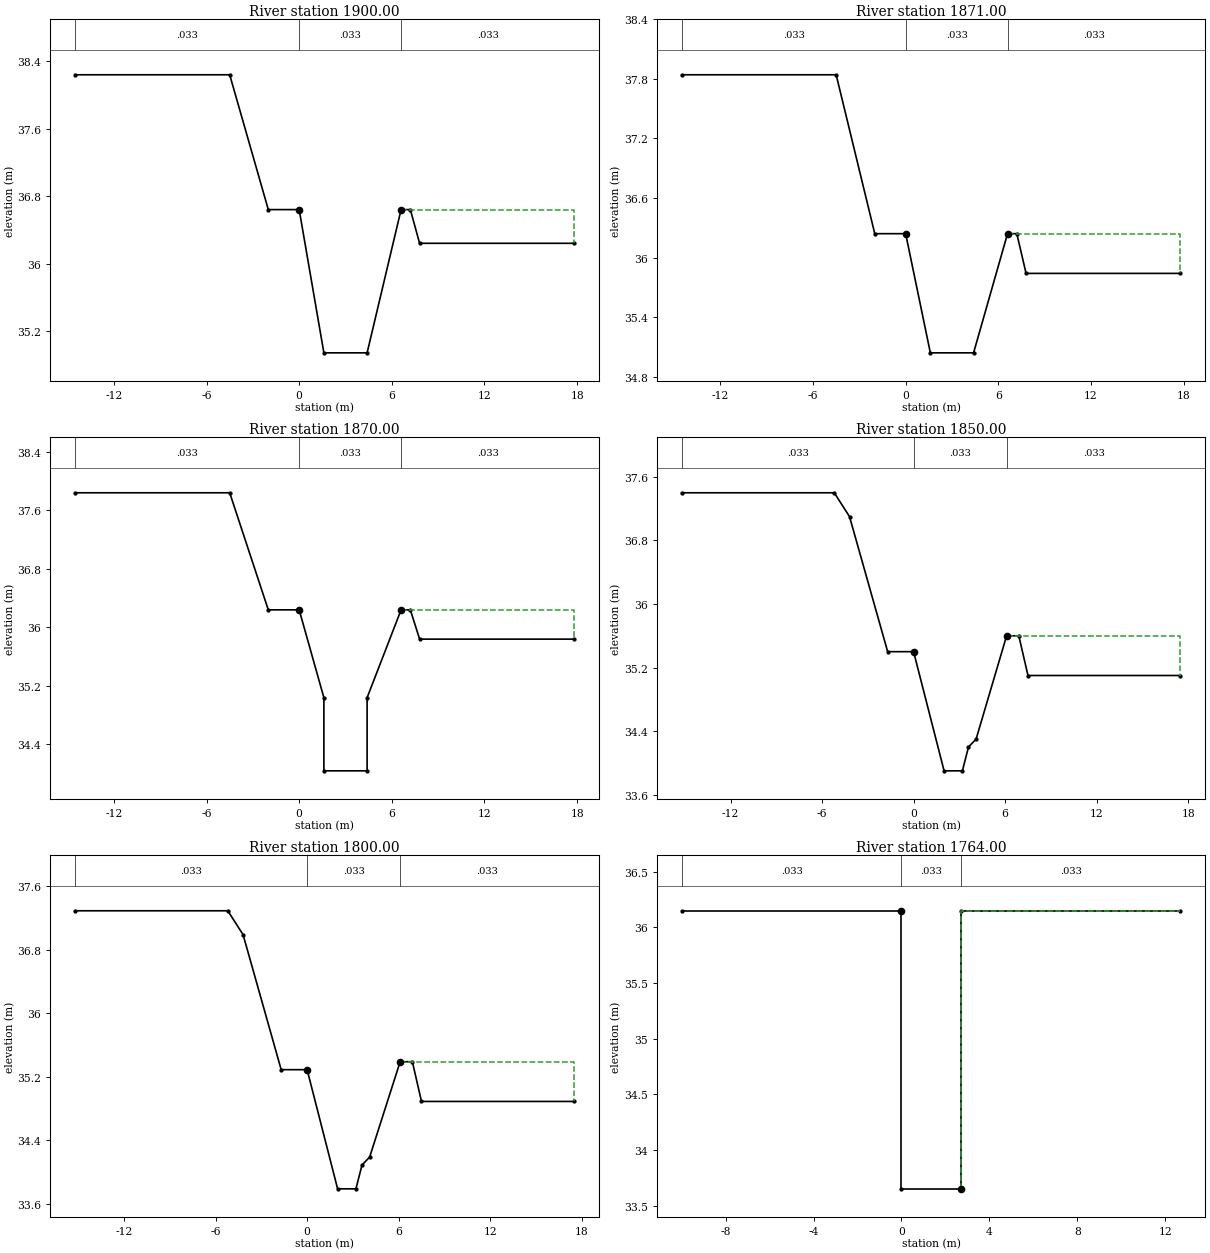
Type RM Length L Ch R = 1 ,1900.00 ,29,29,29
BEGIN DESCRIPTION:
39
END DESCRIPTION:
#Sta/Elev= 10
   -14.5   38.24    -4.5   38.24      -2   36.64       0   36.64     1.6   34.94
     4.4   34.94     6.6   36.64     7.2   36.64     7.8   36.24    17.8   36.24
#Mann= 3 , 0 , 0
   -14.5    .033       0       0    .033       0     6.6    .033       0
#XS Ineff= 2 , 0
               0   36.64     6.6           36.64
Permanent Ineff=
       F       F
Bank Sta=0,6.6
XS Rating Curve= 0
Exp/Cntr=.3,.1

Type RM Length L Ch R = 1 ,1871.00 ,1,1,1
BEGIN DESCRIPTION:
38.021
END DESCRIPTION:
#Sta/Elev= 10
   -14.5   37.84    -4.5   37.84      -2   36.24       0   36.24     1.6   35.04
     4.4   35.04     6.6   36.24     7.2   36.24     7.8   35.84    17.8   35.84
#Mann= 3 , 0 , 0
   -14.5    .033       0       0    .033       0     6.6    .033       0
#XS Ineff= 2 , 0
               0   36.24     6.6           36.24
Permanent Ineff=
       F       F
Bank Sta=0,6.6
XS Rating Curve= 0
Exp/Cntr=.3,.1

Type RM Length L Ch R = 1 ,1870.00 ,20,20,20
BEGIN DESCRIPTION:
38.02
END DESCRIPTION:
#Sta/Elev= 12
   -14.5   37.84    -4.5   37.84      -2   36.24       0   36.24     1.6   35.04
     1.6   34.04     4.4   34.04     4.4   35.04     6.6   36.24     7.2   36.24
     7.8   35.84    17.8   35.84
#Mann= 3 , 0 , 0
   -14.5    .033       0       0    .033       0     6.6    .033       0
#XS Ineff= 2 , 0
               0   36.24     6.6           36.24
Permanent Ineff=
       F       F
Bank Sta=0,6.6
XS Rating Curve= 0
Exp/Cntr=.3,.1

Type RM Length L Ch R = 1 ,1850.00 ,50,50,50
BEGIN DESCRIPTION:
38
END DESCRIPTION:
#Sta/Elev= 13
   -15.2    37.4    -5.2    37.4    -4.2    37.1    -1.7    35.4       0    35.4
       2    33.9     3.2    33.9     3.6    34.2     4.1    34.3     6.1    35.6
     6.9    35.6     7.5    35.1    17.5    35.1
#Mann= 3 , 0 , 0
   -15.2    .033       0       0    .033       0     6.1    .033       0
#XS Ineff= 2 , 0
               0    35.4     6.1            35.6
Permanent Ineff=
       F       F
Bank Sta=0,6.1
XS Rating Curve= 0
Exp/Cntr=.3,.1

Type RM Length L Ch R = 1 ,1800.00 ,36,36,36
BEGIN DESCRIPTION:
37
END DESCRIPTION:
#Sta/Elev= 13
   -15.2   37.29    -5.2   37.29    -4.2   36.99    -1.7   35.29       0   35.29
       2   33.79     3.2   33.79     3.6   34.09     4.1   34.19     6.1   35.39
     6.9   35.39     7.5   34.89    17.5   34.89
#Mann= 3 , 0 , 0
   -15.2    .033       0       0    .033       0     6.1    .033       0
#XS Ineff= 2 , 0
               0   35.29     6.1           35.39
Permanent Ineff=
       F       F
Bank Sta=0,6.1
XS Rating Curve= 0
Exp/Cntr=.3,.1

Type RM Length L Ch R = 1 ,1764.00 ,14,14,14
BEGIN DESCRIPTION:
36.014
END DESCRIPTION:
#Sta/Elev= 6
     -10   36.15       0   36.15       0   33.65     2.7   33.65     2.7   36.15
    12.7   36.15
#Mann= 3 , 0 , 0
     -10    .033       0       0    .033       0     2.7    .033       0
#XS Ineff= 2 , 0
               0   36.15     2.7           36.15
Permanent Ineff=
       F       F
Bank Sta=0,2.7
XS Rating Curve= 0
Exp/Cntr=.3,.1

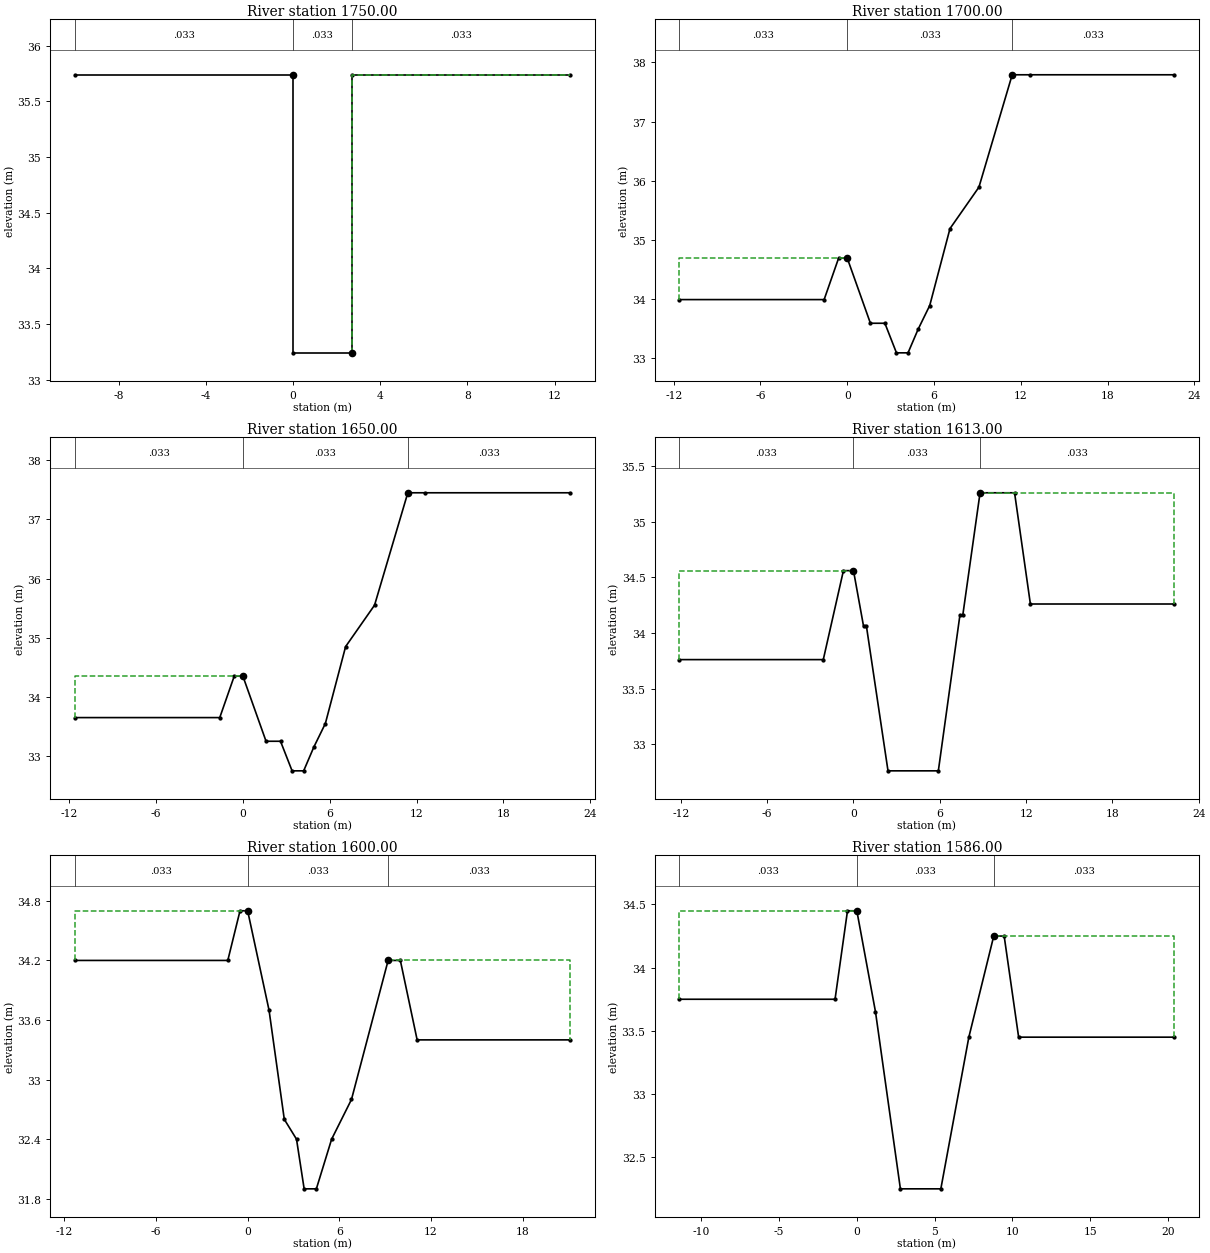
Type RM Length L Ch R = 1 ,1750.00 ,50,50,50
BEGIN DESCRIPTION:
36
END DESCRIPTION:
#Sta/Elev= 6
     -10   35.74       0   35.74       0   33.24     2.7   33.24     2.7   35.74
    12.7   35.74
#Mann= 3 , 0 , 0
     -10    .033       0       0    .033       0     2.7    .033       0
#XS Ineff= 2 , 0
               0   35.74     2.7           35.74
Permanent Ineff=
       F       F
Bank Sta=0,2.7
XS Rating Curve= 0
Exp/Cntr=.3,.1

Type RM Length L Ch R = 1 ,1700.00 ,50,50,50
BEGIN DESCRIPTION:
35
END DESCRIPTION:
#Sta/Elev= 15
   -11.6   33.99    -1.6   33.99     -.6   34.69       0   34.69     1.6   33.59
     2.6   33.59     3.4   33.09     4.2   33.09     4.9   33.49     5.7   33.89
     7.1   35.19     9.1   35.89    11.4   37.79    12.6   37.79    22.6   37.79
#Mann= 3 , 0 , 0
   -11.6    .033       0       0    .033       0    11.4    .033       0
#XS Ineff= 2 , 0
               0   34.69    11.4           37.79
Permanent Ineff=
       F       F
Bank Sta=0,11.4
XS Rating Curve= 0
Exp/Cntr=.3,.1

Type RM Length L Ch R = 1 ,1650.00 ,37,37,37
BEGIN DESCRIPTION:
34
END DESCRIPTION:
#Sta/Elev= 15
   -11.6   33.65    -1.6   33.65     -.6   34.35       0   34.35     1.6   33.25
     2.6   33.25     3.4   32.75     4.2   32.75     4.9   33.15     5.7   33.55
     7.1   34.85     9.1   35.55    11.4   37.45    12.6   37.45    22.6   37.45
#Mann= 3 , 0 , 0
   -11.6    .033       0       0    .033       0    11.4    .033       0
#XS Ineff= 2 , 0
               0   34.35    11.4           37.45
Permanent Ineff=
       F       F
Bank Sta=0,11.4
XS Rating Curve= 0
Exp/Cntr=.3,.1

Type RM Length L Ch R = 1 ,1613.00 ,13,13,13
BEGIN DESCRIPTION:
33.013
END DESCRIPTION:
#Sta/Elev= 14
   -12.1   33.76    -2.1   33.76     -.7   34.56       0   34.56      .7   34.06
      .9   34.06     2.4   32.76     5.9   32.76     7.4   34.16     7.6   34.16
     8.8   35.26    11.2   35.26    12.3   34.26    22.3   34.26
#Mann= 3 , 0 , 0
   -12.1    .033       0       0    .033       0     8.8    .033       0
#XS Ineff= 2 , 0
               0   34.56     8.8           35.26
Permanent Ineff=
       F       F
Bank Sta=0,8.8
XS Rating Curve= 0
Exp/Cntr=.3,.1

Type RM Length L Ch R = 1 ,1600.00 ,14,14,14
BEGIN DESCRIPTION:
32
END DESCRIPTION:
#Sta/Elev= 15
   -11.3    34.2    -1.3    34.2     -.5    34.7       0    34.7     1.4    33.7
     2.4    32.6     3.2    32.4     3.7    31.9     4.5    31.9     5.5    32.4
     6.8    32.8     9.2    34.2      10    34.2    11.1    33.4    21.1    33.4
#Mann= 3 , 0 , 0
   -11.3    .033       0       0    .033       0     9.2    .033       0
#XS Ineff= 2 , 0
               0    34.7     9.2            34.2
Permanent Ineff=
       F       F
Bank Sta=0,9.2
XS Rating Curve= 0
Exp/Cntr=.3,.1

Type RM Length L Ch R = 1 ,1586.00 ,1,1,1
BEGIN DESCRIPTION:
31.036
END DESCRIPTION:
#Sta/Elev= 12
   -11.4   33.75    -1.4   33.75     -.6   34.45       0   34.45     1.2   33.65
     2.8   32.25     5.4   32.25     7.2   33.45     8.8   34.25    9.47   34.25
    10.4   33.45    20.4   33.45
#Mann= 3 , 0 , 0
   -11.4    .033       0       0    .033       0     8.8    .033       0
#XS Ineff= 2 , 0
               0   34.45     8.8           34.25
Permanent Ineff=
       F       F
Bank Sta=0,8.8
XS Rating Curve= 0
Exp/Cntr=.3,.1

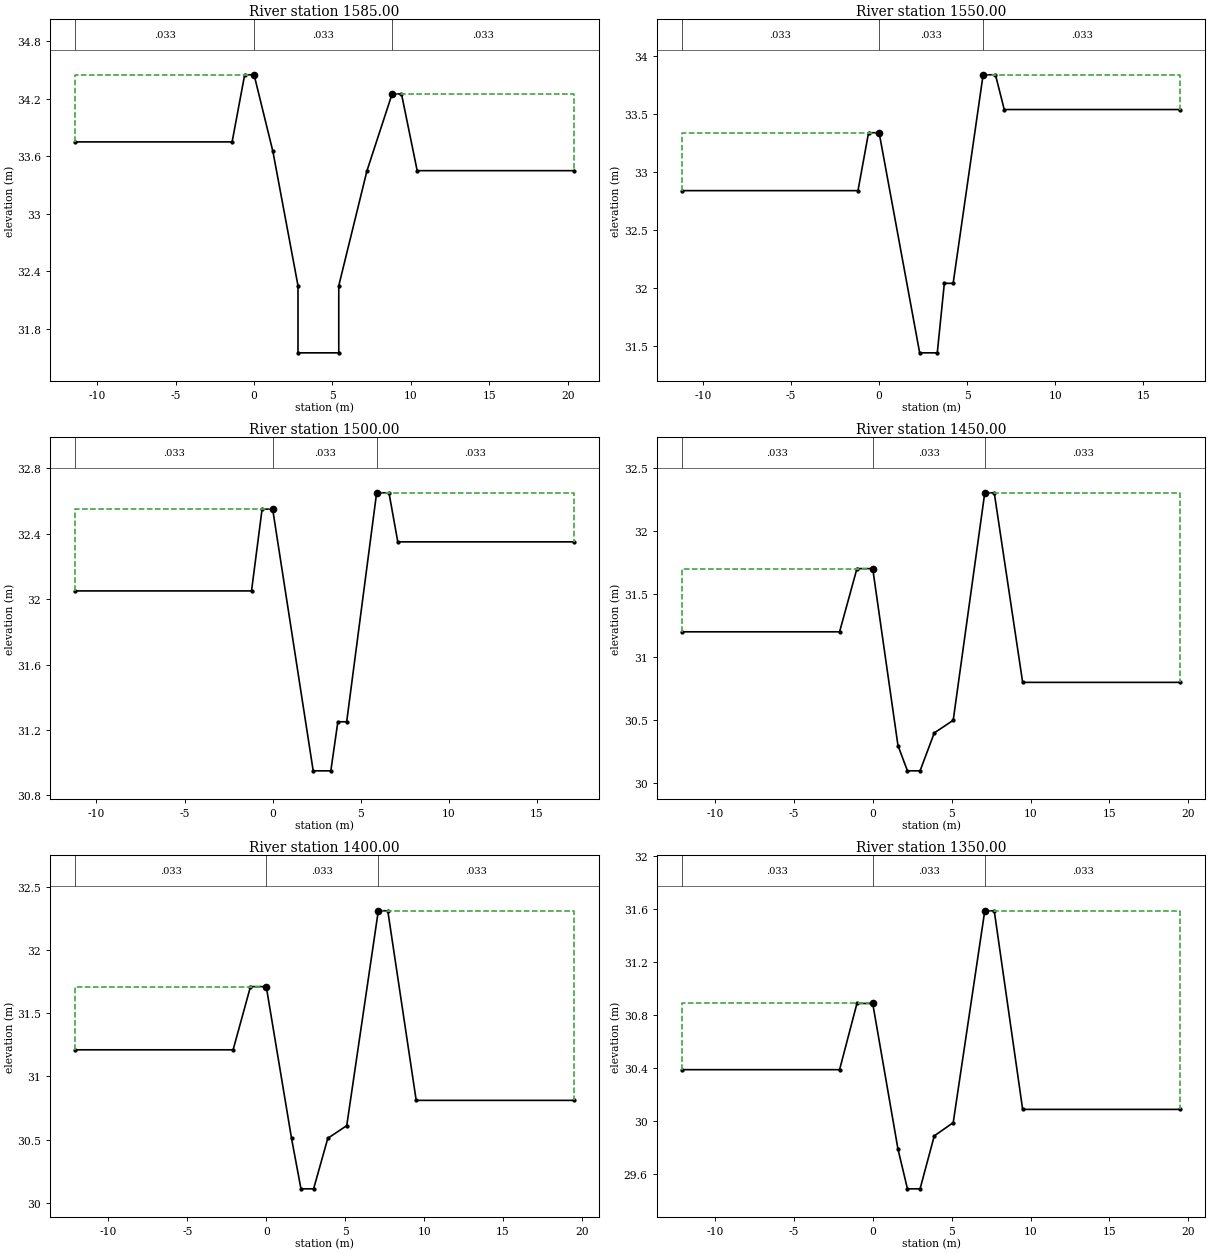
Type RM Length L Ch R = 1 ,1585.00 ,35,35,35
BEGIN DESCRIPTION:
31.035
END DESCRIPTION:
#Sta/Elev= 14
   -11.4   33.75    -1.4   33.75     -.6   34.45       0   34.45     1.2   33.65
     2.8   32.25     2.8   31.55     5.4   31.55     5.4   32.25     7.2   33.45
     8.8   34.25     9.4   34.25    10.4   33.45    20.4   33.45
#Mann= 3 , 0 , 0
   -11.4    .033       0       0    .033       0     8.8    .033       0
#XS Ineff= 2 , 0
               0   34.45     8.8           34.25
Permanent Ineff=
       F       F
Bank Sta=0,8.8
XS Rating Curve= 0
Exp/Cntr=.3,.1

Type RM Length L Ch R = 1 ,1550.00 ,50,50,50
BEGIN DESCRIPTION:
31
END DESCRIPTION:
#Sta/Elev= 12
   -11.2   32.84    -1.2   32.84     -.6   33.34       0   33.34     2.3   31.44
     3.3   31.44     3.7   32.04     4.2   32.04     5.9   33.84     6.6   33.84
     7.1   33.54    17.1   33.54
#Mann= 3 , 0 , 0
   -11.2    .033       0       0    .033       0     5.9    .033       0
#XS Ineff= 2 , 0
               0   33.34     5.9           33.84
Permanent Ineff=
       F       F
Bank Sta=0,5.9
XS Rating Curve= 0
Exp/Cntr=.3,.1

Type RM Length L Ch R = 1 ,1500.00 ,50,50,50
BEGIN DESCRIPTION:
30
END DESCRIPTION:
#Sta/Elev= 12
   -11.2   32.05    -1.2   32.05     -.6   32.55       0   32.55     2.3   30.95
     3.3   30.95     3.7   31.25     4.2   31.25     5.9   32.65     6.6   32.65
     7.1   32.35    17.1   32.35
#Mann= 3 , 0 , 0
   -11.2    .033       0       0    .033       0     5.9    .033       0
#XS Ineff= 2 , 0
               0   32.55     5.9           32.65
Permanent Ineff=
       F       F
Bank Sta=0,5.9
XS Rating Curve= 0
Exp/Cntr=.3,.1

Type RM Length L Ch R = 1 ,1450.00 ,50,50,50
BEGIN DESCRIPTION:
29
END DESCRIPTION:
#Sta/Elev= 13
   -12.1    31.2    -2.1    31.2      -1    31.7       0    31.7     1.6    30.3
     2.2    30.1       3    30.1     3.9    30.4     5.1    30.5     7.1    32.3
     7.7    32.3     9.5    30.8    19.5    30.8
#Mann= 3 , 0 , 0
   -12.1    .033       0       0    .033       0     7.1    .033       0
#XS Ineff= 2 , 0
               0    31.7     7.1            32.3
Permanent Ineff=
       F       F
Bank Sta=0,7.1
XS Rating Curve= 0
Exp/Cntr=.3,.1

Type RM Length L Ch R = 1 ,1400.00 ,50,50,50
BEGIN DESCRIPTION:
28
END DESCRIPTION:
#Sta/Elev= 13
   -12.1   31.21    -2.1   31.21      -1   31.71       0   31.71     1.6   30.51
     2.2   30.11       3   30.11     3.9   30.51     5.1   30.61     7.1   32.31
     7.7   32.31     9.5   30.81    19.5   30.81
#Mann= 3 , 0 , 0
   -12.1    .033       0       0    .033       0     7.1    .033       0
#XS Ineff= 2 , 0
               0   31.71     7.1           32.31
Permanent Ineff=
       F       F
Bank Sta=0,7.1
XS Rating Curve= 0
Exp/Cntr=.3,.1

Type RM Length L Ch R = 1 ,1350.00 ,50,50,50
BEGIN DESCRIPTION:
27
END DESCRIPTION:
#Sta/Elev= 13
   -12.1   30.39    -2.1   30.39      -1   30.89       0   30.89     1.6   29.79
     2.2   29.49       3   29.49     3.9   29.89     5.1   29.99     7.1   31.59
     7.7   31.59     9.5   30.09    19.5   30.09
#Mann= 3 , 0 , 0
   -12.1    .033       0       0    .033       0     7.1    .033       0
#XS Ineff= 2 , 0
               0   30.89     7.1           31.59
Permanent Ineff=
       F       F
Bank Sta=0,7.1
XS Rating Curve= 0
Exp/Cntr=.3,.1

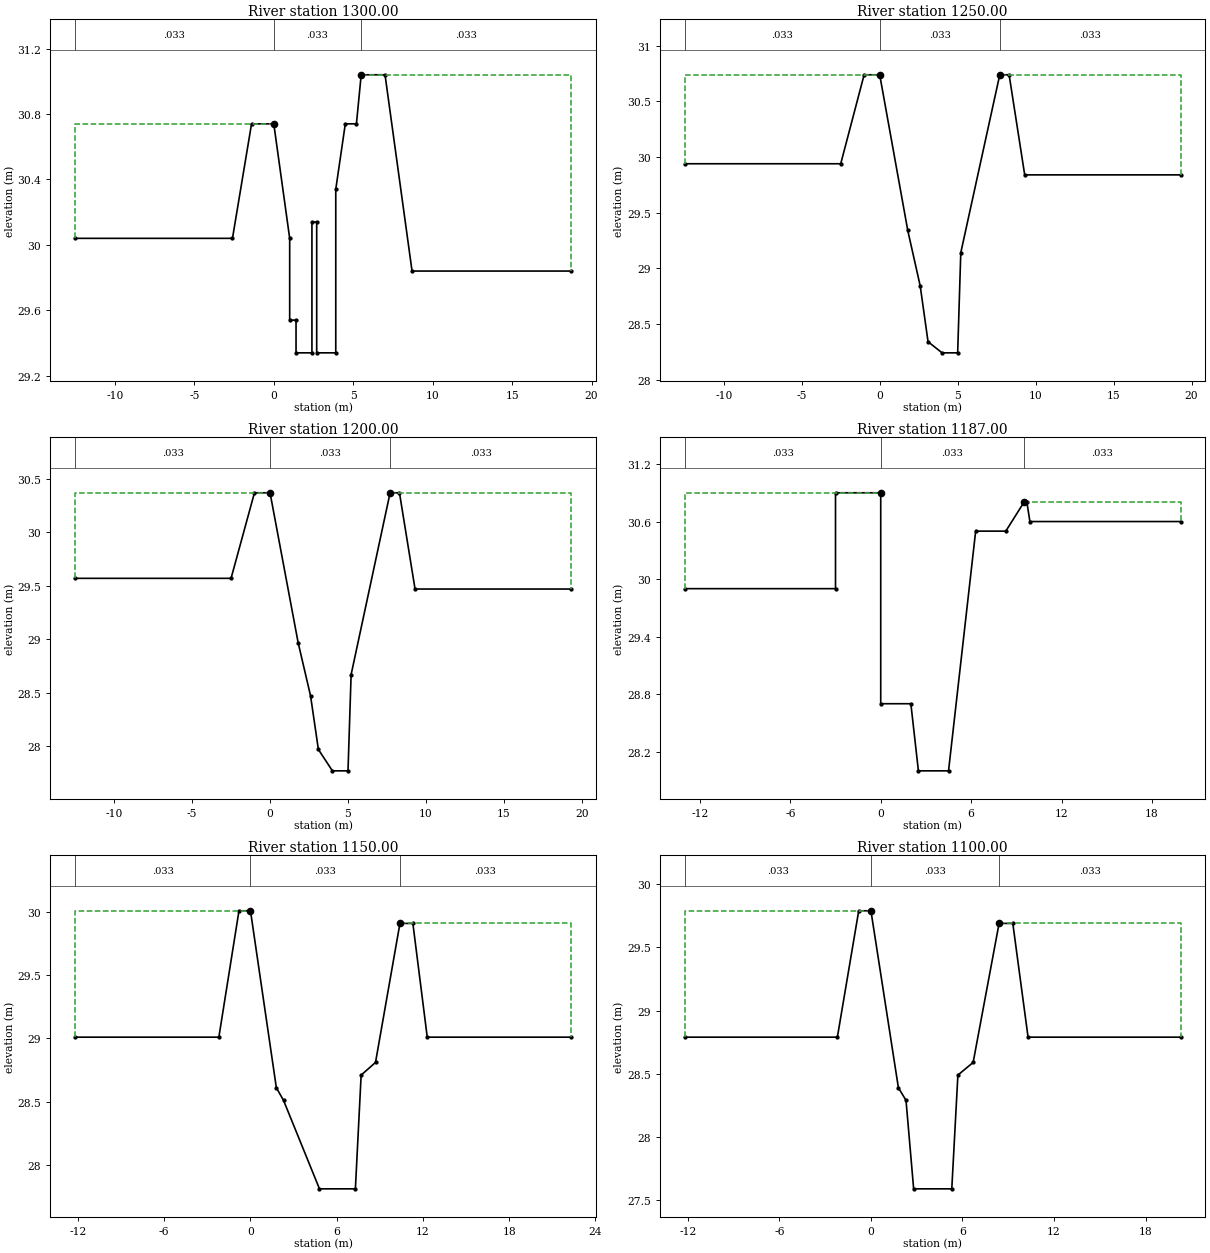
Type RM Length L Ch R = 1 ,1300.00 ,50,50,50
BEGIN DESCRIPTION:
26
END DESCRIPTION:
#Sta/Elev= 20
   -12.5   30.04    -2.6   30.04    -1.4   30.74       0   30.74       1   30.04
       1   29.54     1.4   29.54     1.4   29.34     2.4   29.34     2.4   30.14
     2.7   30.14     2.7   29.34     3.9   29.34     3.9   30.34     4.5   30.74
     5.2   30.74     5.5   31.04       7   31.04     8.7   29.84    18.7   29.84
#Mann= 3 , 0 , 0
   -12.5    .033       0       0    .033       0     5.5    .033       0
#XS Ineff= 2 , 0
               0   30.74     5.5           31.04
Permanent Ineff=
       F       F
Bank Sta=0,5.5
XS Rating Curve= 0
Exp/Cntr=.3,.1

Type RM Length L Ch R = 1 ,1250.00 ,50,50,50
BEGIN DESCRIPTION:
25
END DESCRIPTION:
#Sta/Elev= 14
   -12.5   29.94    -2.5   29.94      -1   30.74       0   30.74     1.8   29.34
     2.6   28.84     3.1   28.34       4   28.24       5   28.24     5.2   29.14
     7.7   30.74     8.3   30.74     9.3   29.84    19.3   29.84
#Mann= 3 , 0 , 0
   -12.5    .033       0       0    .033       0     7.7    .033       0
#XS Ineff= 2 , 0
               0   30.74     7.7           30.74
Permanent Ineff=
       F       F
Bank Sta=0,7.7
XS Rating Curve= 0
Exp/Cntr=.3,.1

Type RM Length L Ch R = 1 ,1200.00 ,13,13,13
BEGIN DESCRIPTION:
24
END DESCRIPTION:
#Sta/Elev= 14
   -12.5   29.57    -2.5   29.57      -1   30.37       0   30.37     1.8   28.97
     2.6   28.47     3.1   27.97       4   27.77       5   27.77     5.2   28.67
     7.7   30.37     8.3   30.37     9.3   29.47    19.3   29.47
#Mann= 3 , 0 , 0
   -12.5    .033       0       0    .033       0     7.7    .033       0
#XS Ineff= 2 , 0
               0   30.37     7.7           30.37
Permanent Ineff=
       F       F
Bank Sta=0,7.7
XS Rating Curve= 0
Exp/Cntr=.3,.1

Type RM Length L Ch R = 1 ,1187.00 ,37,37,37
BEGIN DESCRIPTION:
23.037
END DESCRIPTION:
#Sta/Elev= 14
     -13    29.9      -3    29.9      -3    30.9       0    30.9       0    28.7
       2    28.7     2.5      28     4.5      28     6.3    30.5     8.3    30.5
     9.5    30.8     9.7    30.8     9.9    30.6    19.9    30.6
#Mann= 3 , 0 , 0
     -13    .033       0       0    .033       0     9.5    .033       0
#XS Ineff= 2 , 0
               0    30.9     9.5            30.8
Permanent Ineff=
       F       F
Bank Sta=0,9.5
XS Rating Curve= 0
Exp/Cntr=.3,.1

Type RM Length L Ch R = 1 ,1150.00 ,50,50,50
BEGIN DESCRIPTION:
23
END DESCRIPTION:
#Sta/Elev= 14
   -12.2   29.01    -2.2   29.01     -.8   30.01       0   30.01     1.8   28.61
     2.3   28.51     4.8   27.81     7.3   27.81     7.7   28.71     8.7   28.81
    10.4   29.91    11.3   29.91    12.3   29.01    22.3   29.01
#Mann= 3 , 0 , 0
   -12.2    .033       0       0    .033       0    10.4    .033       0
#XS Ineff= 2 , 0
               0   30.01    10.4           29.91
Permanent Ineff=
       F       F
Bank Sta=0,10.4
XS Rating Curve= 0
Exp/Cntr=.3,.1

Type RM Length L Ch R = 1 ,1100.00 ,40,40,40
BEGIN DESCRIPTION:
22
END DESCRIPTION:
#Sta/Elev= 14
   -12.2   28.79    -2.2   28.79     -.8   29.79       0   29.79     1.8   28.39
     2.3   28.29     2.8   27.59     5.3   27.59     5.7   28.49     6.7   28.59
     8.4   29.69     9.3   29.69    10.3   28.79    20.3   28.79
#Mann= 3 , 0 , 0
   -12.2    .033       0       0    .033       0     8.4    .033       0
#XS Ineff= 2 , 0
               0   29.79     8.4           29.69
Permanent Ineff=
       F       F
Bank Sta=0,8.4
XS Rating Curve= 0
Exp/Cntr=.3,.1

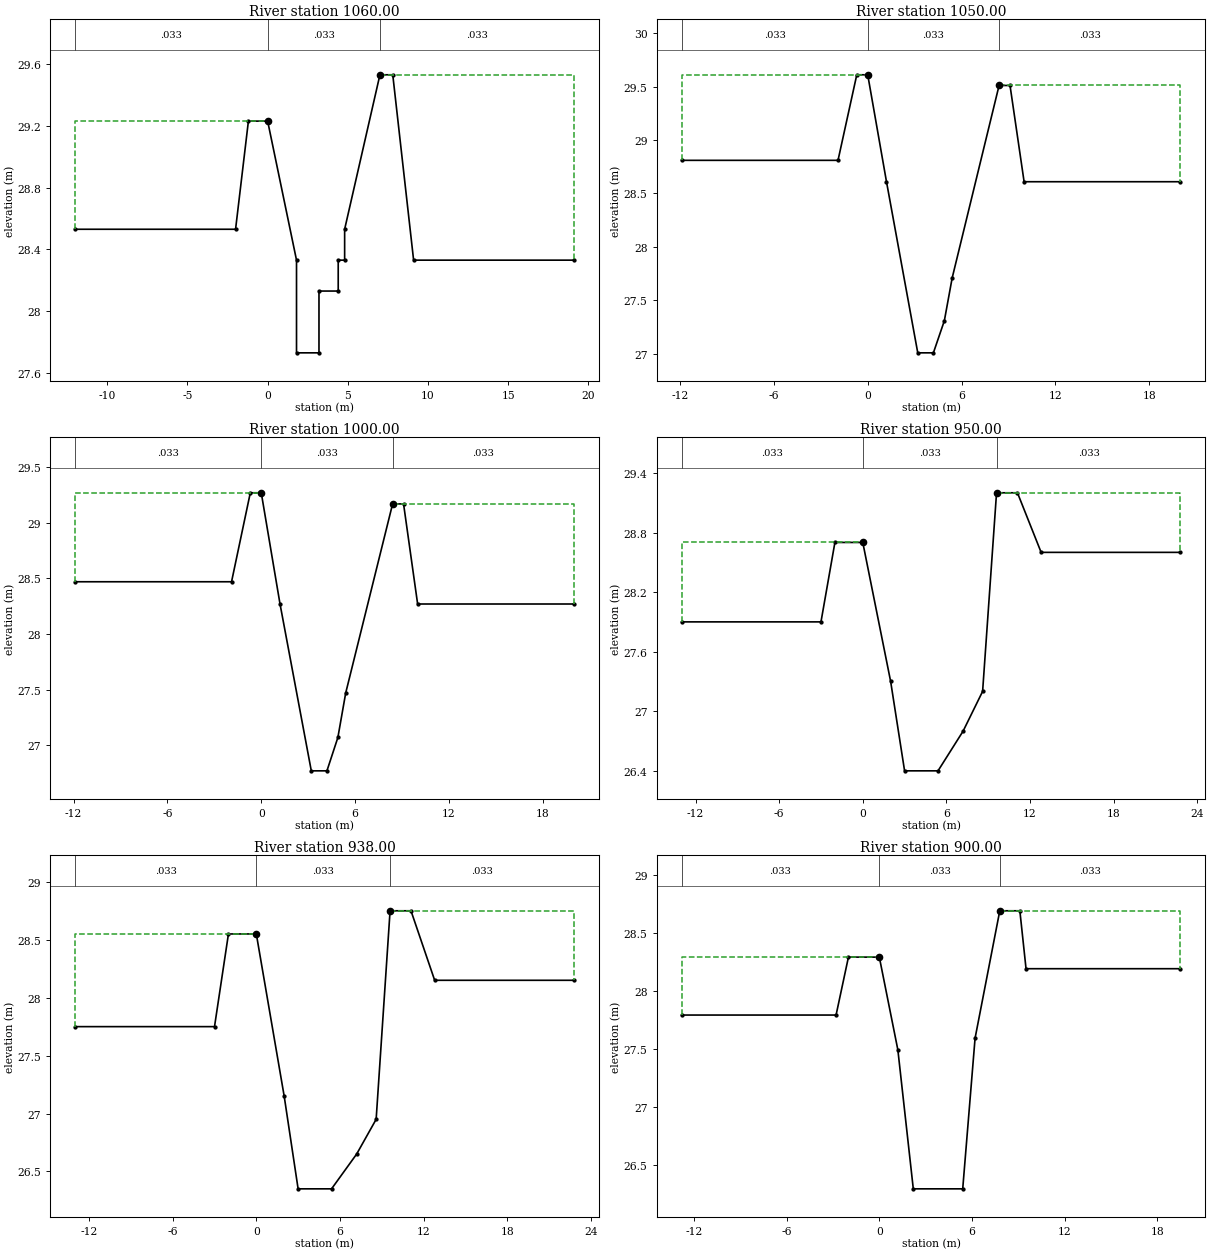
Type RM Length L Ch R = 1 ,1060.00 ,10,10,10
BEGIN DESCRIPTION:
21.01
END DESCRIPTION:
#Sta/Elev= 16
     -12   28.53      -2   28.53    -1.2   29.23       0   29.23     1.8   28.33
     1.8   27.73     3.2   27.73     3.2   28.13     4.4   28.13     4.4   28.33
     4.8   28.33     4.8   28.53       7   29.53     7.8   29.53     9.1   28.33
    19.1   28.33
#Mann= 3 , 0 , 0
     -12    .033       0       0    .033       0       7    .033       0
#XS Ineff= 2 , 0
               0   29.23       7           29.53
Permanent Ineff=
       F       F
Bank Sta=0,7
XS Rating Curve= 0
Exp/Cntr=.3,.1

Type RM Length L Ch R = 1 ,1050.00 ,50,50,50
BEGIN DESCRIPTION:
21
END DESCRIPTION:
#Sta/Elev= 13
   -11.9   28.81    -1.9   28.81     -.7   29.61       0   29.61     1.2   28.61
     3.2   27.01     4.2   27.01     4.9   27.31     5.4   27.71     8.4   29.51
     9.1   29.51      10   28.61      20   28.61
#Mann= 3 , 0 , 0
   -11.9    .033       0       0    .033       0     8.4    .033       0
#XS Ineff= 2 , 0
               0   29.61     8.4           29.51
Permanent Ineff=
       F       F
Bank Sta=0,8.4
XS Rating Curve= 0
Exp/Cntr=.3,.1

Type RM Length L Ch R = 1 ,1000.00 ,50,50,50
BEGIN DESCRIPTION:
20
END DESCRIPTION:
#Sta/Elev= 13
   -11.9   28.47    -1.9   28.47     -.7   29.27       0   29.27     1.2   28.27
     3.2   26.77     4.2   26.77     4.9   27.07     5.4   27.47     8.4   29.17
     9.1   29.17      10   28.27      20   28.27
#Mann= 3 , 0 , 0
   -11.9    .033       0       0    .033       0     8.4    .033       0
#XS Ineff= 2 , 0
               0   29.27     8.4           29.17
Permanent Ineff=
       F       F
Bank Sta=0,8.4
XS Rating Curve= 0
Exp/Cntr=.3,.1

Type RM Length L Ch R = 1 ,950.00  ,12,12,12
BEGIN DESCRIPTION:
19
END DESCRIPTION:
#Sta/Elev= 13
     -13    27.9      -3    27.9      -2    28.7       0    28.7       2    27.3
       3    26.4     5.4    26.4     7.2    26.8     8.6    27.2     9.6    29.2
    11.1    29.2    12.8    28.6    22.8    28.6
#Mann= 3 , 0 , 0
     -13    .033       0       0    .033       0     9.6    .033       0
#XS Ineff= 2 , 0
               0    28.7     9.6            29.2
Permanent Ineff=
       F       F
Bank Sta=0,9.6
XS Rating Curve= 0
Exp/Cntr=.3,.1

Type RM Length L Ch R = 1 ,938.00  ,38,38,38
BEGIN DESCRIPTION:
18.038
END DESCRIPTION:
#Sta/Elev= 13
     -13   27.75      -3   27.75      -2   28.55       0   28.55       2   27.15
       3   26.35     5.4   26.35     7.2   26.65     8.6   26.95     9.6   28.75
    11.1   28.75    12.8   28.15    22.8   28.15
#Mann= 3 , 0 , 0
     -13    .033       0       0    .033       0     9.6    .033       0
#XS Ineff= 2 , 0
               0   28.55     9.6           28.75
Permanent Ineff=
       F       F
Bank Sta=0,9.6
XS Rating Curve= 0
Exp/Cntr=.3,.1

Type RM Length L Ch R = 1 ,900.00  ,50,50,50
BEGIN DESCRIPTION:
18
END DESCRIPTION:
#Sta/Elev= 12
   -12.8   27.79    -2.8   27.79      -2   28.29       0   28.29     1.2   27.49
     2.2   26.29     5.4   26.29     6.2   27.59     7.8   28.69     9.1   28.69
     9.5   28.19    19.5   28.19
#Mann= 3 , 0 , 0
   -12.8    .033       0       0    .033       0     7.8    .033       0
#XS Ineff= 2 , 0
               0   28.29     7.8           28.69
Permanent Ineff=
       F       F
Bank Sta=0,7.8
XS Rating Curve= 0
Exp/Cntr=.3,.1

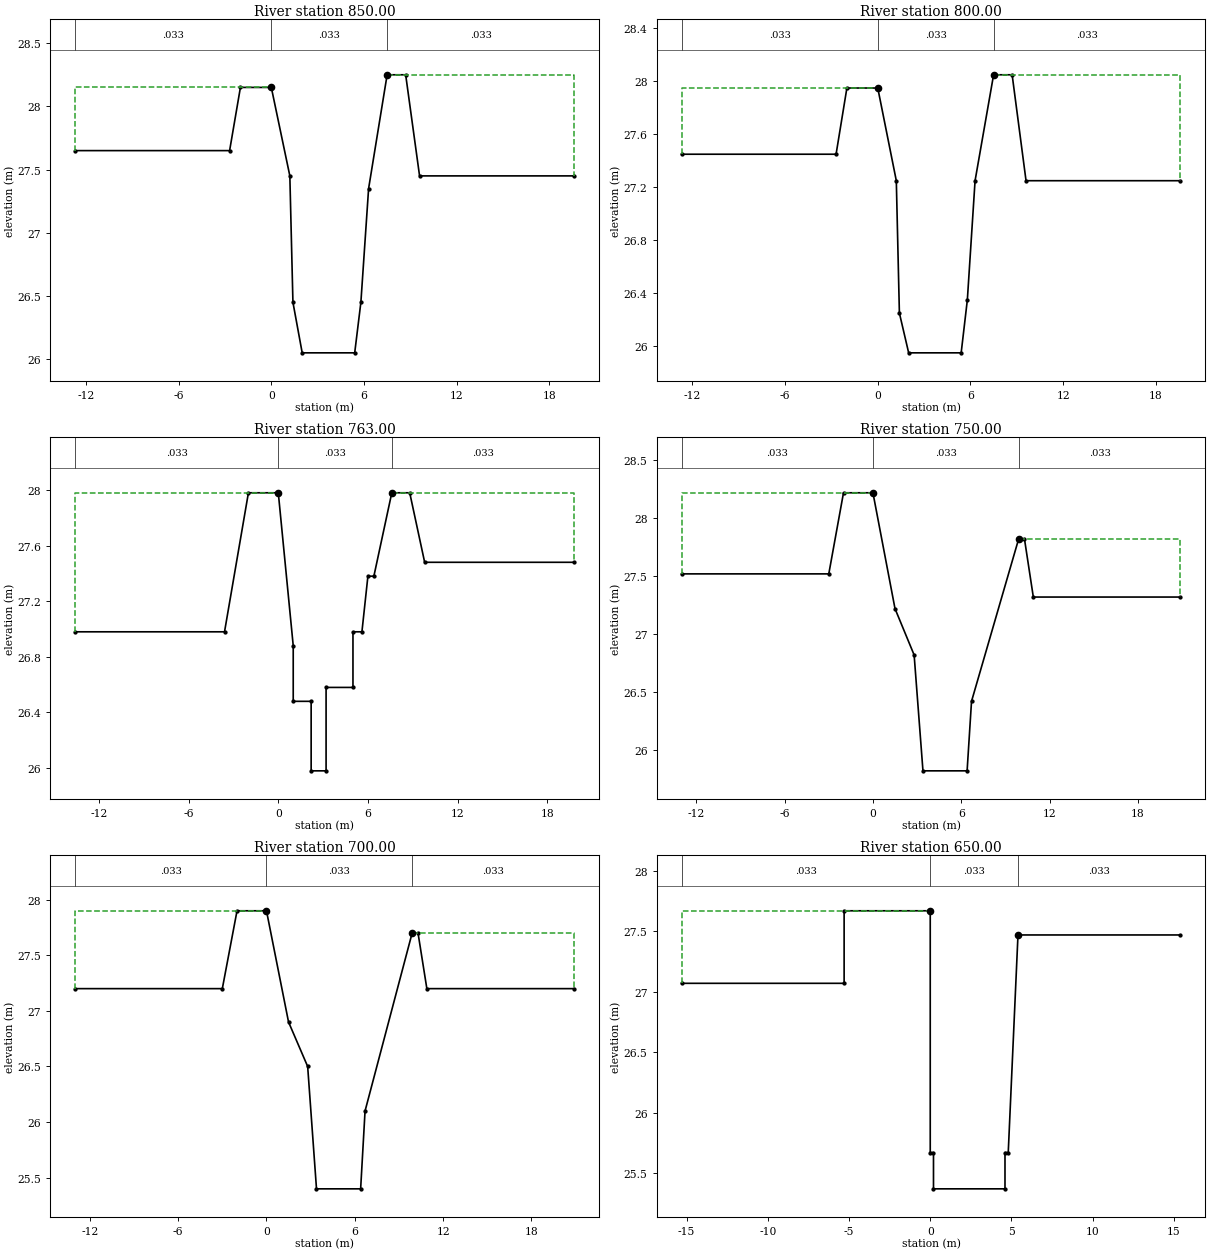
Type RM Length L Ch R = 1 ,850.00  ,50,50,50
BEGIN DESCRIPTION:
17
END DESCRIPTION:
#Sta/Elev= 14
   -12.7   27.65    -2.7   27.65      -2   28.15       0   28.15     1.2   27.45
     1.4   26.45       2   26.05     5.4   26.05     5.8   26.45     6.3   27.35
     7.5   28.25     8.7   28.25     9.6   27.45    19.6   27.45
#Mann= 3 , 0 , 0
   -12.7    .033       0       0    .033       0     7.5    .033       0
#XS Ineff= 2 , 0
               0   28.15     7.5           28.25
Permanent Ineff=
       F       F
Bank Sta=0,7.5
XS Rating Curve= 0
Exp/Cntr=.3,.1

Type RM Length L Ch R = 1 ,800.00  ,37,37,37
BEGIN DESCRIPTION:
16
END DESCRIPTION:
#Sta/Elev= 14
   -12.7   27.45    -2.7   27.45      -2   27.95       0   27.95     1.2   27.25
     1.4   26.25       2   25.95     5.4   25.95     5.8   26.35     6.3   27.25
     7.5   28.05     8.7   28.05     9.6   27.25    19.6   27.25
#Mann= 3 , 0 , 0
   -12.7    .033       0       0    .033       0     7.5    .033       0
#XS Ineff= 2 , 0
               0   27.95     7.5           28.05
Permanent Ineff=
       F       F
Bank Sta=0,7.5
XS Rating Curve= 0
Exp/Cntr=.3,.1

Type RM Length L Ch R = 1 ,763.00  ,13,13,13
BEGIN DESCRIPTION:
15.013
END DESCRIPTION:
#Sta/Elev= 19
   -13.6   26.98    -3.6   26.98      -2   27.98       0   27.98       1   26.88
       1   26.48     2.2   26.48     2.2   25.98     3.2   25.98     3.2   26.58
       5   26.58       5   26.98     5.6   26.98       6   27.38     6.4   27.38
     7.6   27.98     8.8   27.98     9.8   27.48    19.8   27.48
#Mann= 3 , 0 , 0
   -13.6    .033       0       0    .033       0     7.6    .033       0
#XS Ineff= 2 , 0
               0   27.98     7.6           27.98
Permanent Ineff=
       F       F
Bank Sta=0,7.6
XS Rating Curve= 0
Exp/Cntr=.3,.1

Type RM Length L Ch R = 1 ,750.00  ,50,50,50
BEGIN DESCRIPTION:
15
END DESCRIPTION:
#Sta/Elev= 13
     -13   27.52      -3   27.52      -2   28.22       0   28.22     1.5   27.22
     2.8   26.82     3.4   25.82     6.4   25.82     6.7   26.42     9.9   27.82
    10.3   27.82    10.9   27.32    20.9   27.32
#Mann= 3 , 0 , 0
     -13    .033       0       0    .033       0     9.9    .033       0
#XS Ineff= 2 , 0
               0   28.22     9.9           27.82
Permanent Ineff=
       F       F
Bank Sta=0,9.9
XS Rating Curve= 0
Exp/Cntr=.3,.1

Type RM Length L Ch R = 1 ,700.00  ,50,50,50
BEGIN DESCRIPTION:
14
END DESCRIPTION:
#Sta/Elev= 13
     -13    27.2      -3    27.2      -2    27.9       0    27.9     1.5    26.9
     2.8    26.5     3.4    25.4     6.4    25.4     6.7    26.1     9.9    27.7
    10.3    27.7    10.9    27.2    20.9    27.2
#Mann= 3 , 0 , 0
     -13    .033       0       0    .033       0     9.9    .033       0
#XS Ineff= 2 , 0
               0    27.9     9.9            27.7
Permanent Ineff=
       F       F
Bank Sta=0,9.9
XS Rating Curve= 0
Exp/Cntr=.3,.1

Type RM Length L Ch R = 1 ,650.00  ,1,1,1
BEGIN DESCRIPTION:
13
END DESCRIPTION:
#Sta/Elev= 12
   -15.3   27.07    -5.3   27.07    -5.3   27.67       0   27.67       0   25.67
      .2   25.67      .2   25.37     4.6   25.37     4.6   25.67     4.8   25.67
     5.4   27.47    15.4   27.47
#Mann= 3 , 0 , 0
   -15.3    .033       0       0    .033       0     5.4    .033       0
#XS Ineff= 2 , 0
               0   27.67     5.4           27.47
Permanent Ineff=
       F       F
Bank Sta=0,5.4
XS Rating Curve= 0
Exp/Cntr=.3,.1

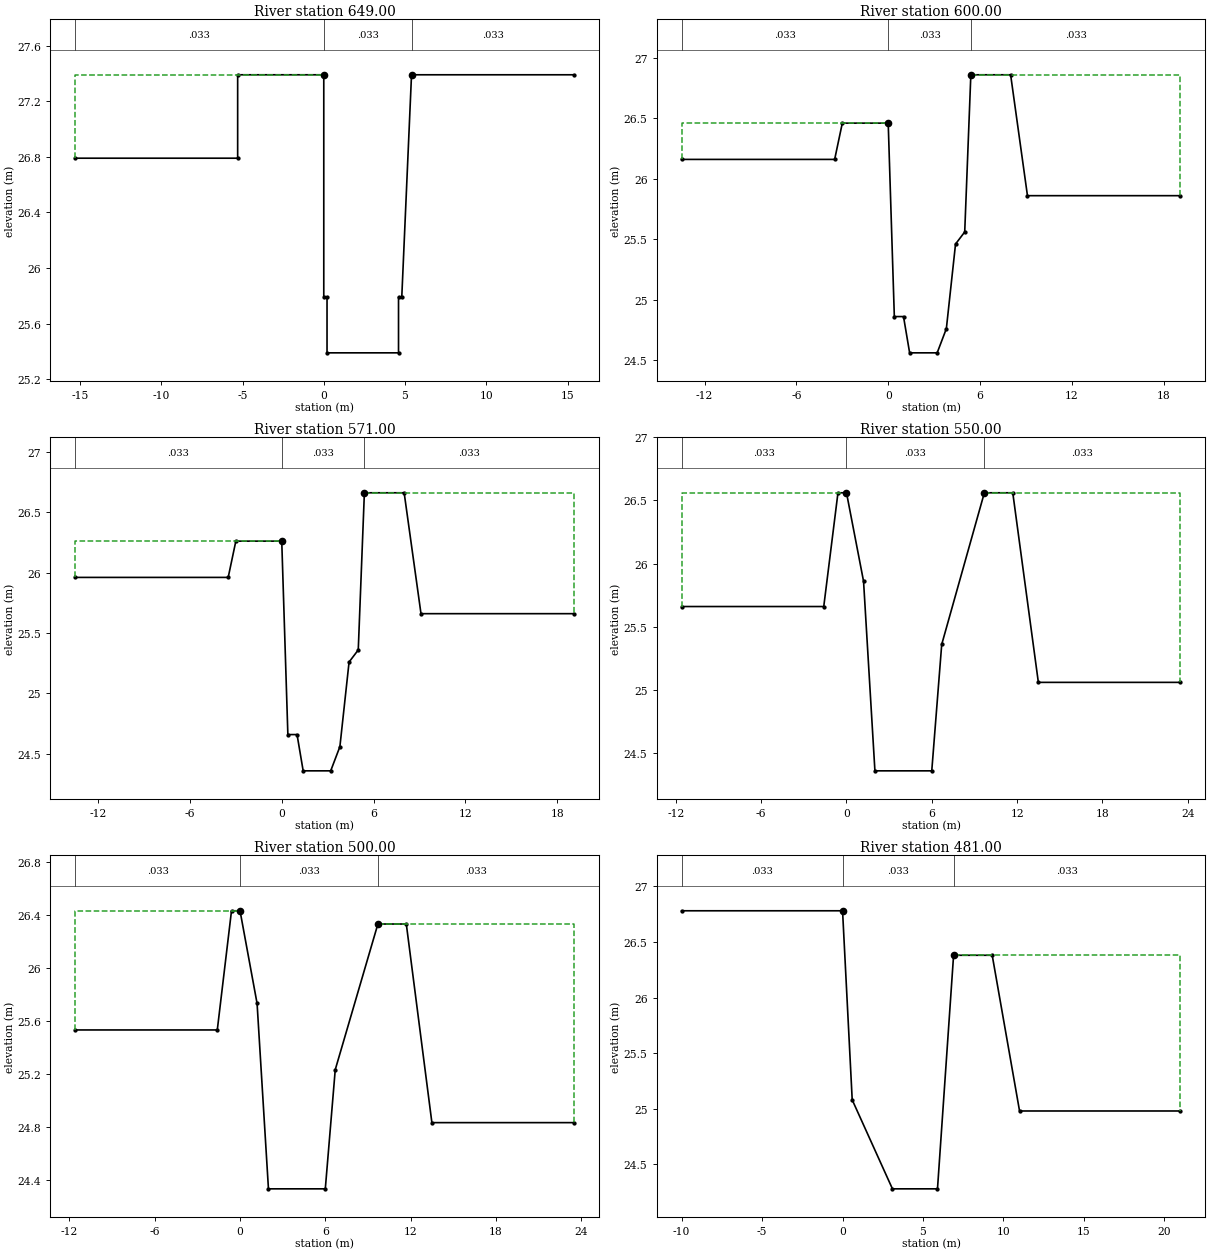
Type RM Length L Ch R = 1 ,649.00  ,49,49,49
BEGIN DESCRIPTION:
12.049
END DESCRIPTION:
#Sta/Elev= 12
   -15.3   26.79    -5.3   26.79    -5.3   27.39       0   27.39       0   25.79
      .2   25.79      .2   25.39     4.6   25.39     4.6   25.79     4.8   25.79
     5.4   27.39    15.4   27.39
#Mann= 3 , 0 , 0
   -15.3    .033       0       0    .033       0     5.4    .033       0
#XS Ineff= 2 , 0
               0   27.39     5.4           27.39
Permanent Ineff=
       F       F
Bank Sta=0,5.4
XS Rating Curve= 0
Exp/Cntr=.3,.1

Type RM Length L Ch R = 1 ,600.00  ,29,29,29
BEGIN DESCRIPTION:
12
END DESCRIPTION:
#Sta/Elev= 15
   -13.5   26.16    -3.5   26.16      -3   26.46       0   26.46      .4   24.86
       1   24.86     1.4   24.56     3.2   24.56     3.8   24.76     4.4   25.46
       5   25.56     5.4   26.86       8   26.86     9.1   25.86    19.1   25.86
#Mann= 3 , 0 , 0
   -13.5    .033       0       0    .033       0     5.4    .033       0
#XS Ineff= 2 , 0
               0   26.46     5.4           26.86
Permanent Ineff=
       F       F
Bank Sta=0,5.4
XS Rating Curve= 0
Exp/Cntr=.3,.1

Type RM Length L Ch R = 1 ,571.00  ,21,21,21
BEGIN DESCRIPTION:
11.021
END DESCRIPTION:
#Sta/Elev= 15
   -13.5   25.96    -3.5   25.96      -3   26.26       0   26.26      .4   24.66
       1   24.66     1.4   24.36     3.2   24.36     3.8   24.56     4.4   25.26
       5   25.36     5.4   26.66       8   26.66     9.1   25.66    19.1   25.66
#Mann= 3 , 0 , 0
   -13.5    .033       0       0    .033       0     5.4    .033       0
#XS Ineff= 2 , 0
               0   26.26     5.4           26.66
Permanent Ineff=
       F       F
Bank Sta=0,5.4
XS Rating Curve= 0
Exp/Cntr=.3,.1

Type RM Length L Ch R = 1 ,550.00  ,50,50,50
BEGIN DESCRIPTION:
11
END DESCRIPTION:
#Sta/Elev= 12
   -11.6   25.66    -1.6   25.66     -.6   26.56       0   26.56     1.2   25.86
       2   24.36       6   24.36     6.7   25.36     9.7   26.56    11.7   26.56
    13.5   25.06    23.5   25.06
#Mann= 3 , 0 , 0
   -11.6    .033       0       0    .033       0     9.7    .033       0
#XS Ineff= 2 , 0
               0   26.56     9.7           26.56
Permanent Ineff=
       F       F
Bank Sta=0,9.7
XS Rating Curve= 0
Exp/Cntr=.3,.1

Type RM Length L Ch R = 1 ,500.00  ,19,19,19
BEGIN DESCRIPTION:
10
END DESCRIPTION:
#Sta/Elev= 12
   -11.6   25.53    -1.6   25.53     -.6   26.43       0   26.43     1.2   25.73
       2   24.33       6   24.33     6.7   25.23     9.7   26.33    11.7   26.33
    13.5   24.83    23.5   24.83
#Mann= 3 , 0 , 0
   -11.6    .033       0       0    .033       0     9.7    .033       0
#XS Ineff= 2 , 0
               0   26.43     9.7           26.33
Permanent Ineff=
       F       F
Bank Sta=0,9.7
XS Rating Curve= 0
Exp/Cntr=.3,.1

Type RM Length L Ch R = 1 ,481.00  ,31,31,31
BEGIN DESCRIPTION:
9.031
END DESCRIPTION:
#Sta/Elev= 9
     -10   26.78       0   26.78      .6   25.08     3.1   24.28     5.9   24.28
     6.9   26.38     9.3   26.38      11   24.98      21   24.98
#Mann= 3 , 0 , 0
     -10    .033       0       0    .033       0     6.9    .033       0
#XS Ineff= 2 , 0
               0   26.78     6.9           26.38
Permanent Ineff=
       F       F
Bank Sta=0,6.9
XS Rating Curve= 0
Exp/Cntr=.3,.1