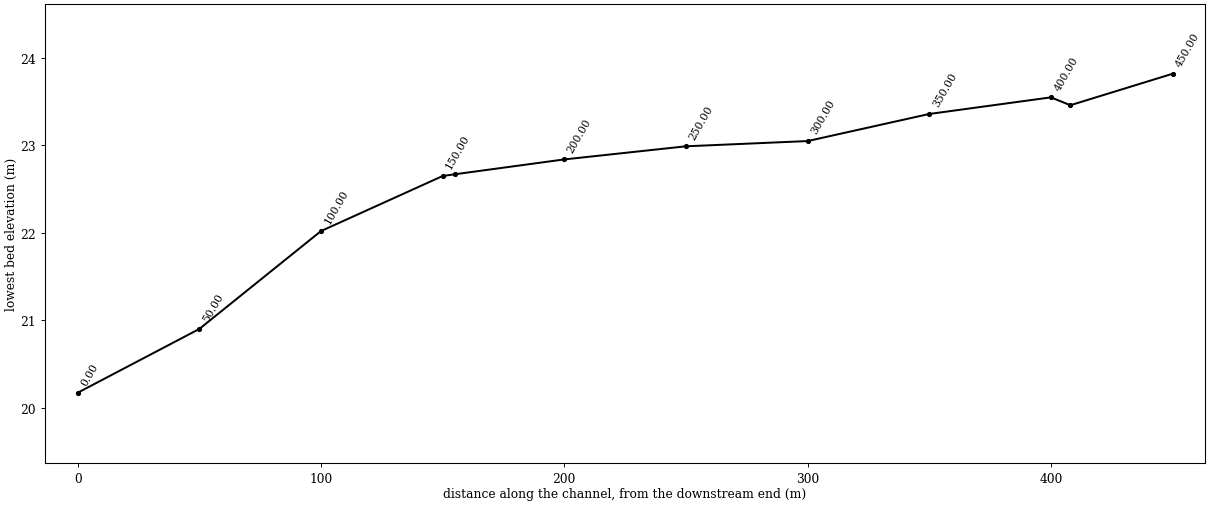
HEC-RAS study DONG.prj: DONG

--- DONG.g01 (geometry) --- (continued)

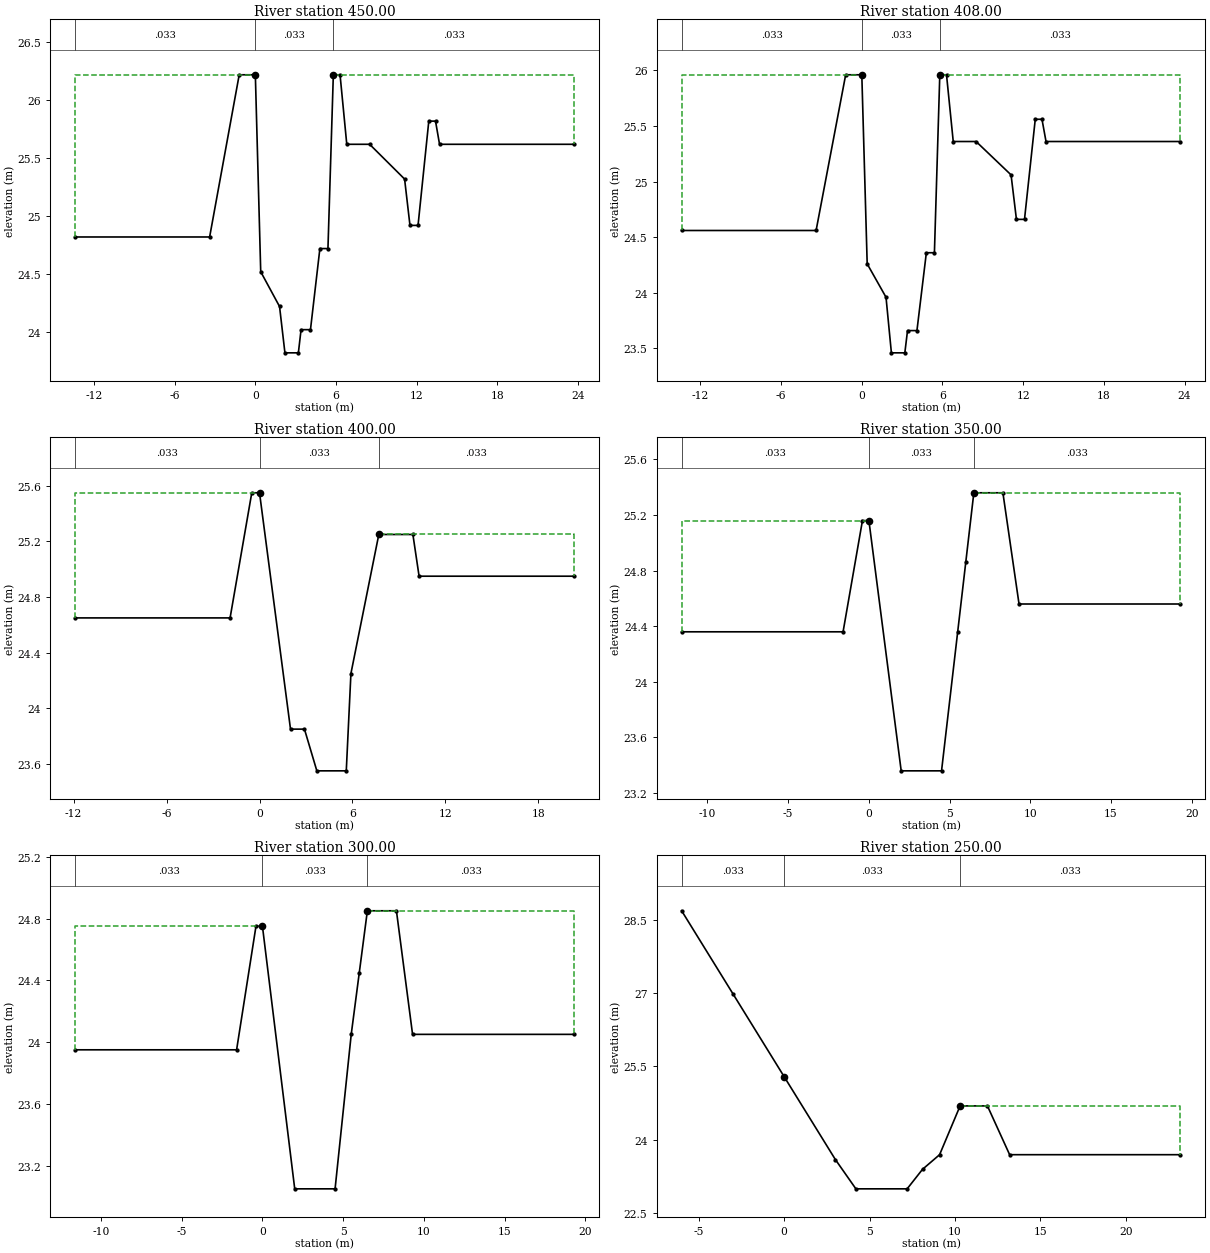
Type RM Length L Ch R = 1 ,450.00  ,42,42,42
BEGIN DESCRIPTION:
9
END DESCRIPTION:
#Sta/Elev= 23
   -13.4   24.82    -3.4   24.82    -1.2   26.22       0   26.22      .4   24.52
     1.8   24.22     2.2   23.82     3.2   23.82     3.4   24.02     4.1   24.02
     4.8   24.72     5.4   24.72     5.8   26.22     6.3   26.22     6.8   25.62
     8.5   25.62    11.1   25.32    11.5   24.92    12.1   24.92    12.9   25.82
    13.4   25.82    13.7   25.62    23.7   25.62
#Mann= 3 , 0 , 0
   -13.4    .033       0       0    .033       0     5.8    .033       0
#XS Ineff= 2 , 0
               0   26.22     5.8           26.22
Permanent Ineff=
       F       F
Bank Sta=0,5.8
XS Rating Curve= 0
Exp/Cntr=.3,.1

Type RM Length L Ch R = 1 ,408.00  ,8,8,8
BEGIN DESCRIPTION:
8.008
END DESCRIPTION:
#Sta/Elev= 23
   -13.4   24.56    -3.4   24.56    -1.2   25.96       0   25.96      .4   24.26
     1.8   23.96     2.2   23.46     3.2   23.46     3.4   23.66     4.1   23.66
     4.8   24.36     5.4   24.36     5.8   25.96     6.3   25.96     6.8   25.36
     8.5   25.36    11.1   25.06    11.5   24.66    12.1   24.66    12.9   25.56
    13.4   25.56    13.7   25.36    23.7   25.36
#Mann= 3 , 0 , 0
   -13.4    .033       0       0    .033       0     5.8    .033       0
#XS Ineff= 2 , 0
               0   25.96     5.8           25.96
Permanent Ineff=
       F       F
Bank Sta=0,5.8
XS Rating Curve= 0
Exp/Cntr=.3,.1

Type RM Length L Ch R = 1 ,400.00  ,50,50,50
BEGIN DESCRIPTION:
8
END DESCRIPTION:
#Sta/Elev= 13
   -11.9   24.65    -1.9   24.65     -.5   25.55       0   25.55       2   23.85
     2.9   23.85     3.7   23.55     5.6   23.55     5.9   24.25     7.7   25.25
     9.9   25.25    10.3   24.95    20.3   24.95
#Mann= 3 , 0 , 0
   -11.9    .033       0       0    .033       0     7.7    .033       0
#XS Ineff= 2 , 0
               0   25.55     7.7           25.25
Permanent Ineff=
       F       F
Bank Sta=0,7.7
XS Rating Curve= 0
Exp/Cntr=.3,.1

Type RM Length L Ch R = 1 ,350.00  ,50,50,50
BEGIN DESCRIPTION:
7
END DESCRIPTION:
#Sta/Elev= 12
   -11.6   24.36    -1.6   24.36     -.4   25.16       0   25.16       2   23.36
     4.5   23.36     5.5   24.36       6   24.86     6.5   25.36     8.3   25.36
     9.3   24.56    19.3   24.56
#Mann= 3 , 0 , 0
   -11.6    .033       0       0    .033       0     6.5    .033       0
#XS Ineff= 2 , 0
               0   25.16     6.5           25.36
Permanent Ineff=
       F       F
Bank Sta=0,6.5
XS Rating Curve= 0
Exp/Cntr=.3,.1

Type RM Length L Ch R = 1 ,300.00  ,50,50,50
BEGIN DESCRIPTION:
6
END DESCRIPTION:
#Sta/Elev= 12
   -11.6   23.95    -1.6   23.95     -.4   24.75       0   24.75       2   23.05
     4.5   23.05     5.5   24.05       6   24.45     6.5   24.85     8.3   24.85
     9.3   24.05    19.3   24.05
#Mann= 3 , 0 , 0
   -11.6    .033       0       0    .033       0     6.5    .033       0
#XS Ineff= 2 , 0
               0   24.75     6.5           24.85
Permanent Ineff=
       F       F
Bank Sta=0,6.5
XS Rating Curve= 0
Exp/Cntr=.3,.1

Type RM Length L Ch R = 1 ,250.00  ,50,50,50
BEGIN DESCRIPTION:
5
END DESCRIPTION:
#Sta/Elev= 12
      -6   28.69      -3   26.99       0   25.29       3   23.59     4.2   22.99
     7.2   22.99     8.1   23.39     9.1   23.69    10.3   24.69    11.9   24.69
    13.2   23.69    23.2   23.69
#Mann= 3 , 0 , 0
      -6    .033       0       0    .033       0    10.3    .033       0
#XS Ineff= 2 , 0
               0   25.29    10.3           24.69
Permanent Ineff=
       F       F
Bank Sta=0,10.3
XS Rating Curve= 0
Exp/Cntr=.3,.1

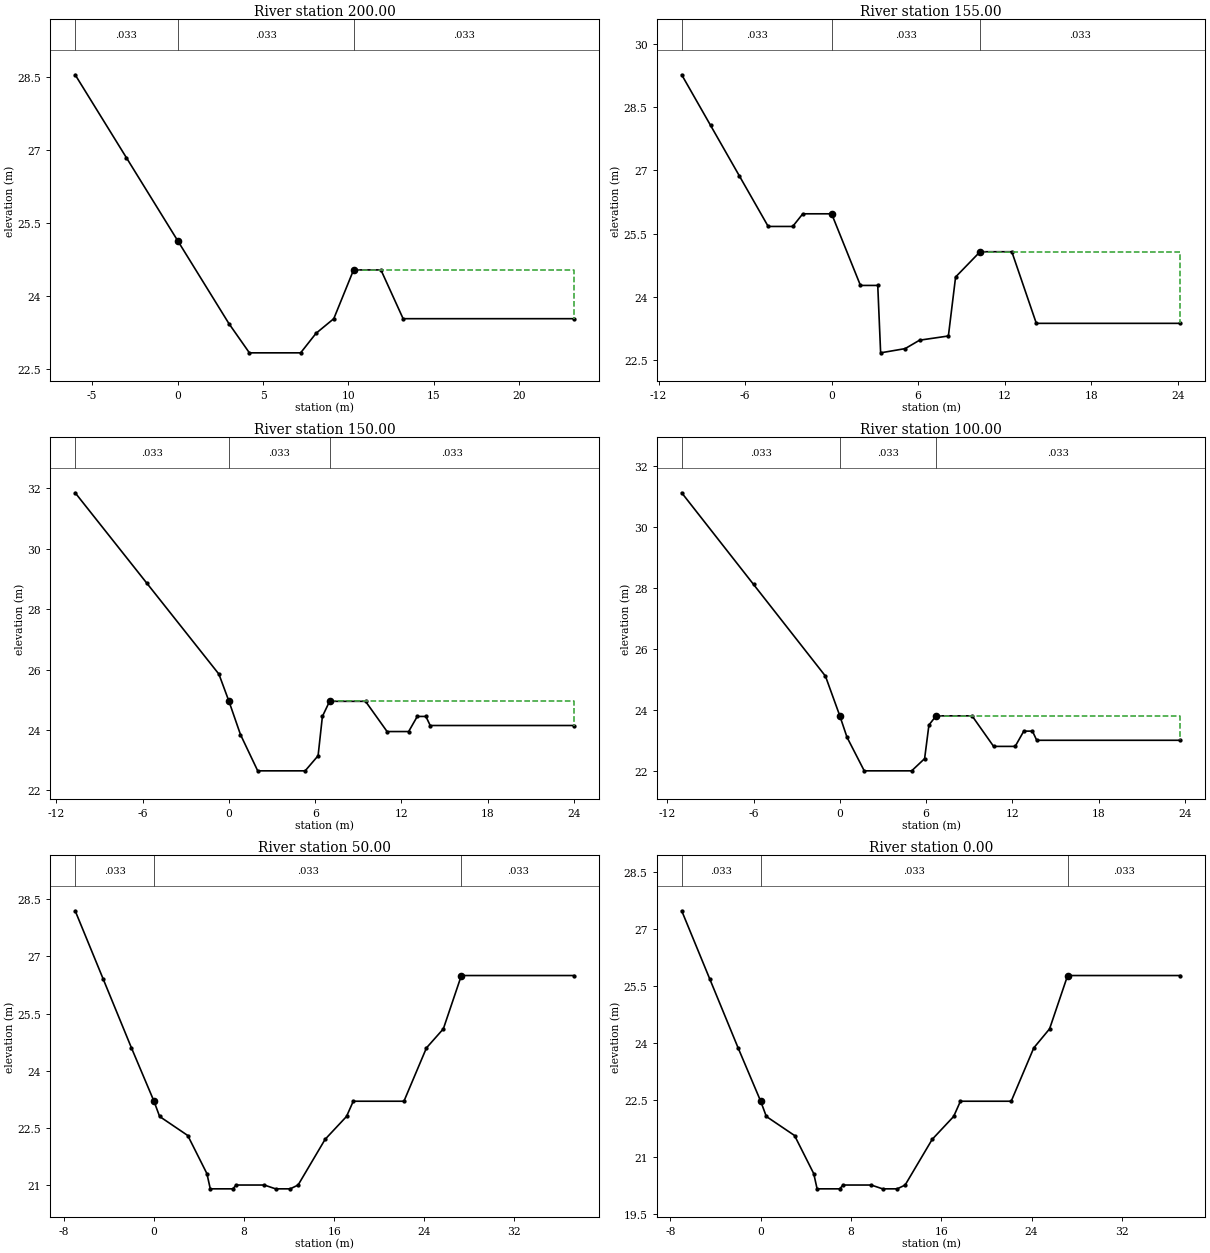
Type RM Length L Ch R = 1 ,200.00  ,45,45,45
BEGIN DESCRIPTION:
4
END DESCRIPTION:
#Sta/Elev= 12
      -6   28.54      -3   26.84       0   25.14       3   23.44     4.2   22.84
     7.2   22.84     8.1   23.24    9.14   23.54    10.3   24.54    11.9   24.54
    13.2   23.54    23.2   23.54
#Mann= 3 , 0 , 0
      -6    .033       0       0    .033       0    10.3    .033       0
#XS Ineff= 2 , 0
               0   25.14    10.3           24.54
Permanent Ineff=
       F       F
Bank Sta=0,10.3
XS Rating Curve= 0
Exp/Cntr=.3,.1

Type RM Length L Ch R = 1 ,155.00  ,5,5,5
BEGIN DESCRIPTION:
3.005
END DESCRIPTION:
#Sta/Elev= 18
   -10.4   29.27    -8.4   28.07    -6.4   26.87    -4.4   25.67    -2.7   25.67
      -2   25.97       0   25.97       2   24.27     3.2   24.27     3.4   22.67
     5.1   22.77     6.1   22.97     8.1   23.07     8.6   24.47    10.3   25.07
    12.5   25.07    14.2   23.37    24.2   23.37
#Mann= 3 , 0 , 0
   -10.4    .033       0       0    .033       0    10.3    .033       0
#XS Ineff= 2 , 0
               0   25.97    10.3           25.07
Permanent Ineff=
       F       F
Bank Sta=0,10.3
XS Rating Curve= 0
Exp/Cntr=.3,.1

Type RM Length L Ch R = 1 ,150.00  ,50,50,50
BEGIN DESCRIPTION:
3
END DESCRIPTION:
#Sta/Elev= 17
   -10.7   31.85    -5.7   28.85     -.7   25.85       0   24.95      .8   23.85
       2   22.65     5.3   22.65     6.2   23.15     6.5   24.45       7   24.95
     9.5   24.95      11   23.95    12.5   23.95    13.1   24.45    13.7   24.45
      14   24.15      24   24.15
#Mann= 3 , 0 , 0
   -10.7    .033       0       0    .033       0       7    .033       0
#XS Ineff= 2 , 0
               0   24.95       7           24.95
Permanent Ineff=
       F       F
Bank Sta=0,7
XS Rating Curve= 0
Exp/Cntr=.3,.1

Type RM Length L Ch R = 1 ,100.00  ,50,50,50
BEGIN DESCRIPTION:
2
END DESCRIPTION:
#Sta/Elev= 17
     -11   31.12      -6   28.12      -1   25.12       0   23.82      .5   23.12
     1.7   22.02       5   22.02     5.9   22.42     6.2   23.52     6.7   23.82
     9.2   23.82    10.7   22.82    12.2   22.82    12.8   23.32    13.4   23.32
    13.7   23.02    23.7   23.02
#Mann= 3 , 0 , 0
     -11    .033       0       0    .033       0     6.7    .033       0
#XS Ineff= 2 , 0
               0   23.82     6.7           23.82
Permanent Ineff=
       F       F
Bank Sta=0,6.7
XS Rating Curve= 0
Exp/Cntr=.3,.1

Type RM Length L Ch R = 1 ,50.00   ,50,50,50
BEGIN DESCRIPTION:
1
END DESCRIPTION:
#Sta/Elev= 22
      -7    28.2    -4.5    26.4      -2    24.6       0    23.2      .5    22.8
       3    22.3     4.7    21.3       5    20.9       7    20.9     7.3      21
     9.8      21    10.8    20.9    12.1    20.9    12.8      21    15.2    22.2
    17.1    22.8    17.7    23.2    22.2    23.2    24.2    24.6    25.7    25.1
    27.3    26.5    37.3    26.5
#Mann= 3 , 0 , 0
      -7    .033       0       0    .033       0    27.3    .033       0
#XS Ineff= 2 , 0
               0    23.2    27.3            26.5
Permanent Ineff=
       F       F
Bank Sta=0,27.3
XS Rating Curve= 0
Exp/Cntr=.3,.1

Type RM Length L Ch R = 1 ,0.00    ,0,0,0
BEGIN DESCRIPTION:
0
END DESCRIPTION:
#Sta/Elev= 22
      -7   27.47    -4.5   25.67      -2   23.87       0   22.47      .5   22.07
       3   21.57     4.7   20.57       5   20.17       7   20.17     7.3   20.27
     9.8   20.27    10.8   20.17    12.1   20.17    12.8   20.27    15.2   21.47
    17.1   22.07    17.7   22.47    22.2   22.47    24.2   23.87    25.6   24.37
    27.2   25.77    37.2   25.77
#Mann= 3 , 0 , 0
      -7    .033       0       0    .033       0    27.2    .033       0
#XS Ineff= 2 , 0
               0   22.47    27.2           25.77
Permanent Ineff=
       F       F
Bank Sta=0,27.2
XS Rating Curve= 0
Exp/Cntr=.3,.1

Chan Stop Cuts=-1