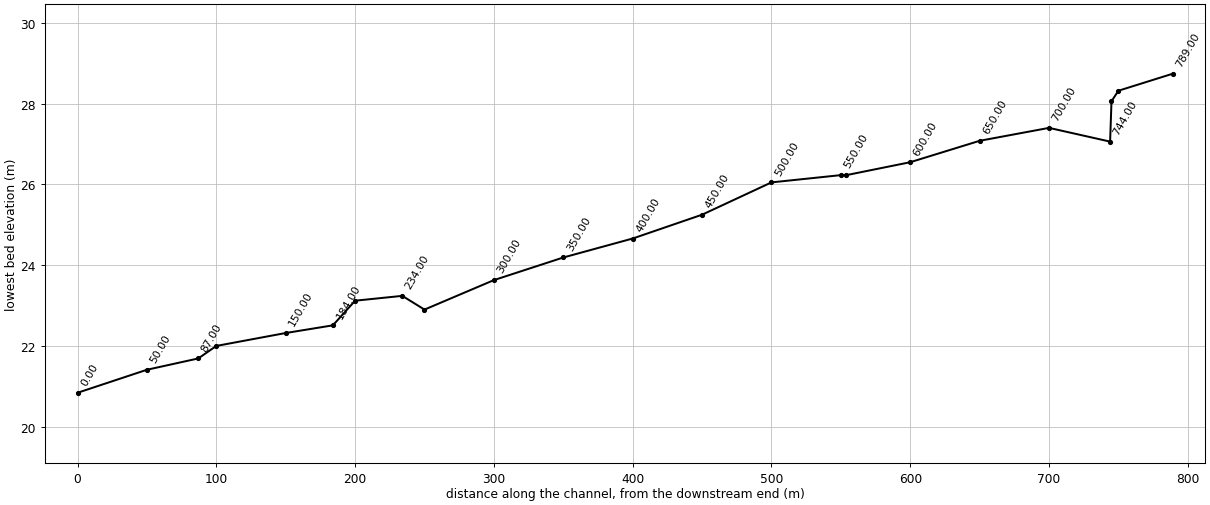
--- YDC.prj (project) ---

Proj Title=YDC
Current Plan=p01
Default Exp/Contr=.3,.1
SI Units
Geom File=g01
Flow File=f01
Plan File=p01
Y Axis Title=Elevation
X Axis Title(PF)=Main Channel Distance
X Axis Title(XS)=Station
BEGIN DESCRIPTION:
           BACK WATER COMPUTATION
      APPLICATION OF HEC-2 BY Samju Construction Engineering
      YOULDONG-STREEM : 30 YR
END DESCRIPTION:
DSS Export Rating Curves= 0
DSS Export Rating Curve Sorted= 0
DSS Export Volume Flow Curves= 0
DXF OffsetX= 0
DXF OffsetY= 0
DXF ScaleX= 1
DXF ScaleY= 10

--- YDC.p01 (plan) ---

Plan Title=Imported Plan 01
Version=Version 3.0.1  Mar 2001
Short Identifier=Imported Pla
Geom File=g01
Flow File=f01
Subcritical Flow
K Sum by GR= 0
Std Step Tol= 0.003
Critical Tol= 0.003
Num of Std Step Trials= 20
Max Error Tol= 0.1
Flow Tol Ratio= 0.001
Split Flow NTrial= 30
Split Flow Tol= 0.02
Split Flow Ratio= 0.02
Log Output Level= 0
Friction Slope Method= 1
Unsteady Friction Slope Method= 2
Parabolic Critical Depth
Global Vel Dist= 0 , 0 , 0
Global Log Level= 0
CheckData=True
Encroach Param=-1 ,0,0, 0
Computation Interval=1HOUR
Output Interval=1HOUR
Run HTab= 0
Run UNet= 0
Run PostProcess= 0
UNET Theta= 1
UNET ZTol= 0.02
UNET ZSATol= 0.1
UNET MxIter= 20
UNET MaxInSteps= 20
UNET DtIC= 0
UNET DtMin= 0
UNET MaxCRTS= 20
UNET WFStab= 2
UNET SFStab= 1
UNET WFX= 1
UNET SFX= 1
UNET Convert EG Bridges=-1
UNET Use Existing IB Tables=-1
Instantaneous Interval=1HOUR
Write IC File= 0
Write Velocity= 0
Write Detailed= 0

--- YDC.f01 (steady flow) ---

Flow Title=Imported Flow 01
Version=Version 3.0.1  Mar 2001
Number of Profiles= 5
Profile Names=10YR,20YR,30YR,50YR,80YR
River Rch & RM=RIVER-1,Reach-1         ,789.00
   13.97   15.39   16.22   17.26   18.23
Boundary for River Rch & Prof#=RIVER-1,Reach-1         , 1
Up Type= 0
Dn Type= 3
Dn Slope=.05
Boundary for River Rch & Prof#=RIVER-1,Reach-1         , 2
Up Type= 0
Dn Type= 3
Dn Slope=.05
Boundary for River Rch & Prof#=RIVER-1,Reach-1         , 3
Up Type= 0
Dn Type= 3
Dn Slope=.05
Boundary for River Rch & Prof#=RIVER-1,Reach-1         , 4
Up Type= 0
Dn Type= 3
Dn Slope=.05
Boundary for River Rch & Prof#=RIVER-1,Reach-1         , 5
Up Type= 0
Dn Type= 3
Dn Slope=.05
DSS Import GetInterval= 0
DSS Import GetPeak= 0
DSS Import FillOption= 0

--- YDC.g01 (geometry) ---

Geom Title=Imported Geom 01
Version=Version 3.0.1  Mar 2001

River Reach=RIVER-1         ,Reach-1
Reach XY= 2
              .5             .95              .5             .05

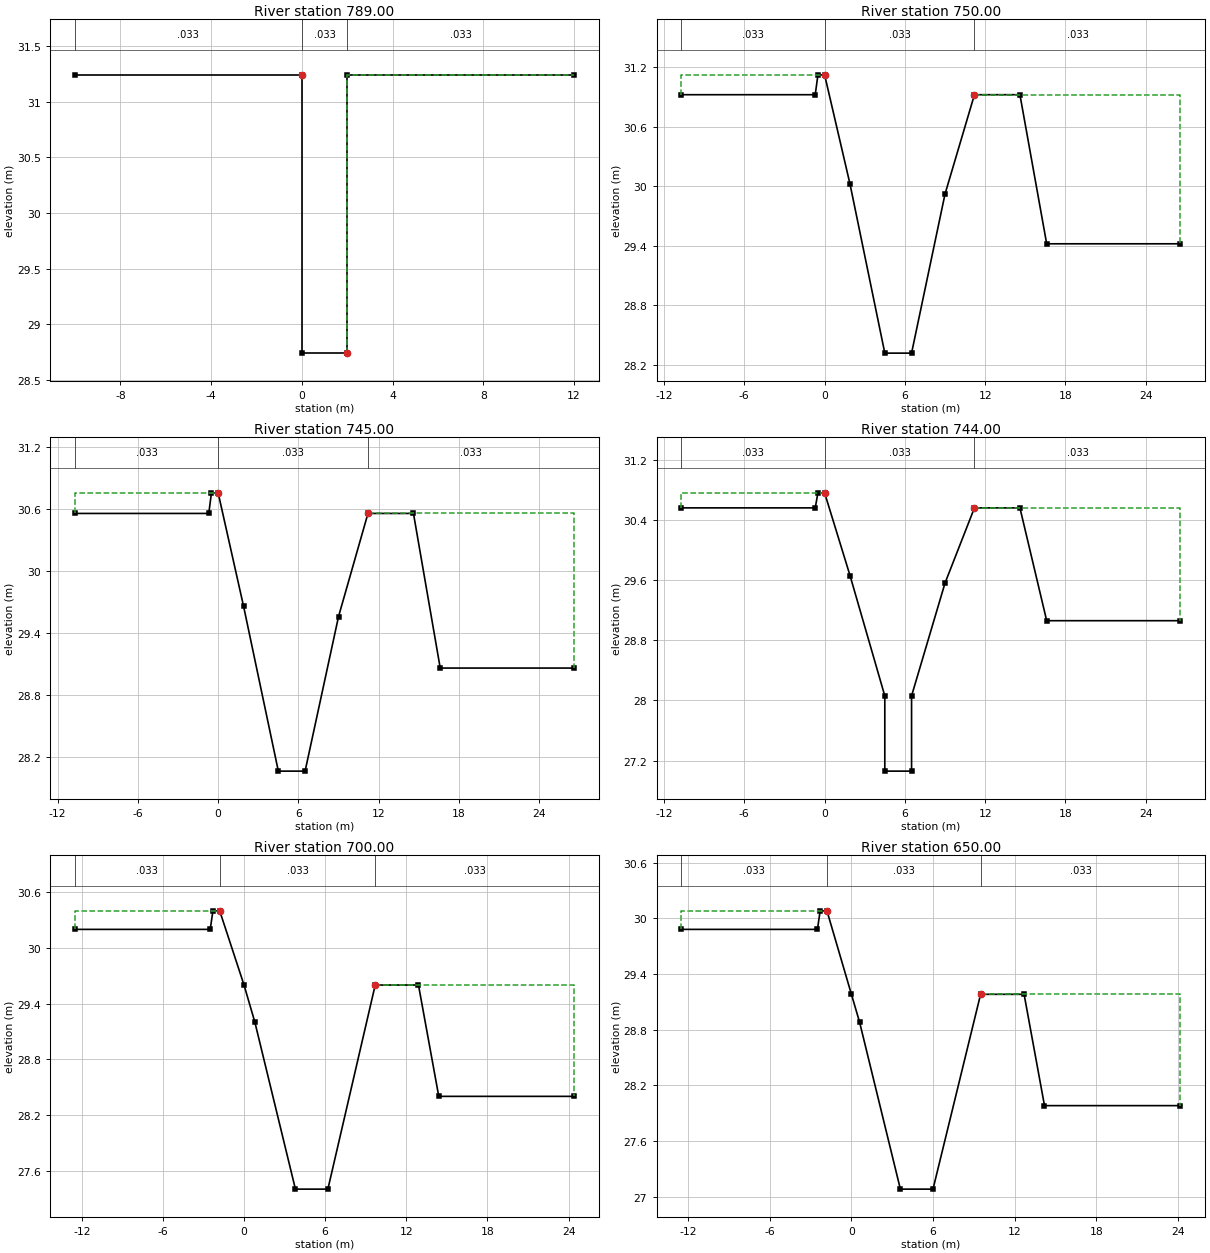
Type RM Length L Ch R = 1 ,789.00  ,39,39,39
BEGIN DESCRIPTION:
15.039
END DESCRIPTION:
#Sta/Elev= 6
     -10   31.24       0   31.24       0   28.74       2   28.74       2   31.24
      12   31.24
#Mann= 3 , 0 , 0
     -10    .033       0       0    .033       0       2    .033       0
#XS Ineff= 2 , 0
               0   31.24       2           31.24
Permanent Ineff=
       F       F
Bank Sta=0,2
XS Rating Curve= 0
Exp/Cntr=.3,.1

Type RM Length L Ch R = 1 ,750.00  ,5,5,5
BEGIN DESCRIPTION:
15
END DESCRIPTION:
#Sta/Elev= 12
   -10.7   30.92     -.7   30.92     -.5   31.12       0   31.12     1.9   30.02
     4.5   28.32     6.5   28.32       9   29.92    11.2   30.92    14.6   30.92
    16.6   29.42    26.6   29.42
#Mann= 3 , 0 , 0
   -10.7    .033       0       0    .033       0    11.2    .033       0
#XS Ineff= 2 , 0
               0   31.12    11.2           30.92
Permanent Ineff=
       F       F
Bank Sta=0,11.2
XS Rating Curve= 0
Exp/Cntr=.3,.1

Type RM Length L Ch R = 1 ,745.00  ,1,1,1
BEGIN DESCRIPTION:
14.045
END DESCRIPTION:
#Sta/Elev= 12
   -10.7   30.56     -.7   30.56     -.5   30.76       0   30.76     1.9   29.66
     4.5   28.06     6.5   28.06       9   29.56    11.2   30.56    14.6   30.56
    16.6   29.06    26.6   29.06
#Mann= 3 , 0 , 0
   -10.7    .033       0       0    .033       0    11.2    .033       0
#XS Ineff= 2 , 0
               0   30.76    11.2           30.56
Permanent Ineff=
       F       F
Bank Sta=0,11.2
XS Rating Curve= 0
Exp/Cntr=.3,.1

Type RM Length L Ch R = 1 ,744.00  ,44,44,44
BEGIN DESCRIPTION:
14.044
END DESCRIPTION:
#Sta/Elev= 14
   -10.7   30.56     -.7   30.56     -.5   30.76       0   30.76     1.9   29.66
     4.5   28.06     4.5   27.06     6.5   27.06     6.5   28.06       9   29.56
    11.2   30.56    14.6   30.56    16.6   29.06    26.6   29.06
#Mann= 3 , 0 , 0
   -10.7    .033       0       0    .033       0    11.2    .033       0
#XS Ineff= 2 , 0
               0   30.76    11.2           30.56
Permanent Ineff=
       F       F
Bank Sta=0,11.2
XS Rating Curve= 0
Exp/Cntr=.3,.1

Type RM Length L Ch R = 1 ,700.00  ,50,50,50
BEGIN DESCRIPTION:
14
END DESCRIPTION:
#Sta/Elev= 12
   -12.5    30.2    -2.5    30.2    -2.3    30.4    -1.8    30.4       0    29.6
      .8    29.2     3.8    27.4     6.2    27.4     9.7    29.6    12.9    29.6
    14.4    28.4    24.4    28.4
#Mann= 3 , 0 , 0
   -12.5    .033       0    -1.8    .033       0     9.7    .033       0
#XS Ineff= 2 , 0
            -1.8    30.4     9.7            29.6
Permanent Ineff=
       F       F
Bank Sta=-1.8,9.7
XS Rating Curve= 0
Exp/Cntr=.3,.1

Type RM Length L Ch R = 1 ,650.00  ,50,50,50
BEGIN DESCRIPTION:
13
END DESCRIPTION:
#Sta/Elev= 12
   -12.5   29.88    -2.5   29.88    -2.3   30.08    -1.8   30.08       0   29.18
      .6   28.88     3.6   27.08       6   27.08     9.5   29.18    12.7   29.18
    14.2   27.98    24.2   27.98
#Mann= 3 , 0 , 0
   -12.5    .033       0    -1.8    .033       0     9.5    .033       0
#XS Ineff= 2 , 0
            -1.8   30.08     9.5           29.18
Permanent Ineff=
       F       F
Bank Sta=-1.8,9.5
XS Rating Curve= 0
Exp/Cntr=.3,.1

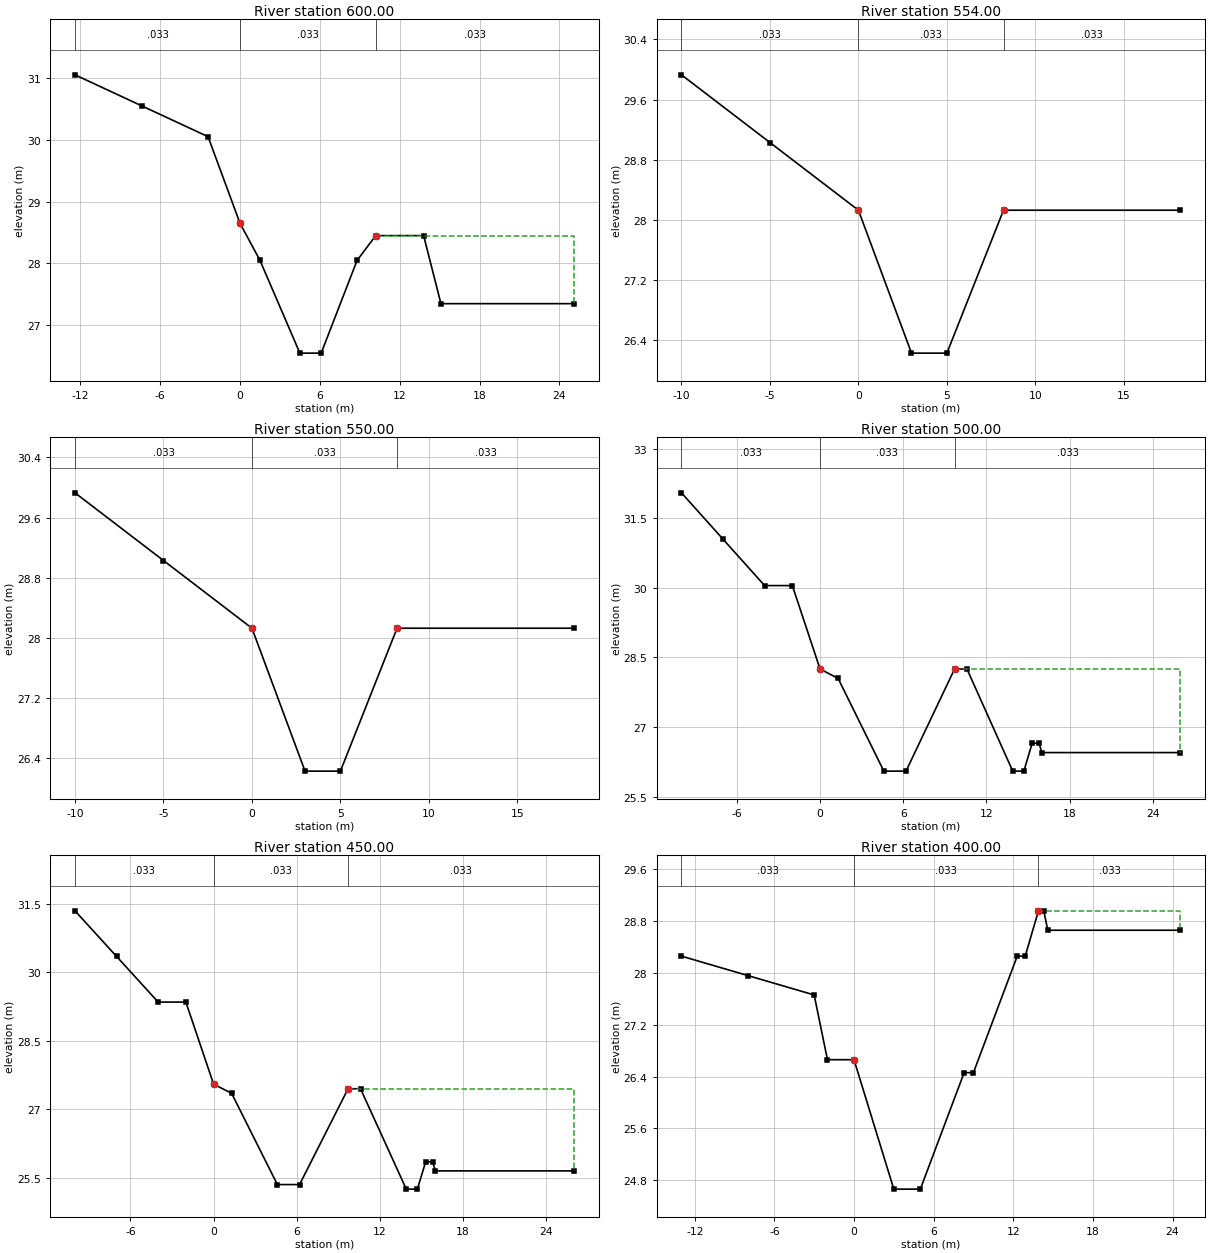
Type RM Length L Ch R = 1 ,600.00  ,46,46,46
BEGIN DESCRIPTION:
12
END DESCRIPTION:
#Sta/Elev= 12
   -12.4   31.05    -7.4   30.55    -2.4   30.05       0   28.65     1.5   28.05
     4.5   26.55     6.1   26.55     8.8   28.05    10.2   28.45    13.8   28.45
    15.1   27.35    25.1   27.35
#Mann= 3 , 0 , 0
   -12.4    .033       0       0    .033       0    10.2    .033       0
#XS Ineff= 2 , 0
               0   28.65    10.2           28.45
Permanent Ineff=
       F       F
Bank Sta=0,10.2
XS Rating Curve= 0
Exp/Cntr=.3,.1

Type RM Length L Ch R = 1 ,554.00  ,4,4,4
BEGIN DESCRIPTION:
11.004
END DESCRIPTION:
#Sta/Elev= 7
     -10   29.93      -5   29.03       0   28.13       3   26.23       5   26.23
     8.2   28.13    18.2   28.13
#Mann= 3 , 0 , 0
     -10    .033       0       0    .033       0     8.2    .033       0
#XS Ineff= 2 , 0
               0   28.13     8.2           28.13
Permanent Ineff=
       F       F
Bank Sta=0,8.2
XS Rating Curve= 0
Exp/Cntr=.3,.1

Type RM Length L Ch R = 1 ,550.00  ,50,50,50
BEGIN DESCRIPTION:
11
END DESCRIPTION:
#Sta/Elev= 7
     -10   29.93      -5   29.03       0   28.13       3   26.23       5   26.23
     8.2   28.13    18.2   28.13
#Mann= 3 , 0 , 0
     -10    .033       0       0    .033       0     8.2    .033       0
#XS Ineff= 2 , 0
               0   28.13     8.2           28.13
Permanent Ineff=
       F       F
Bank Sta=0,8.2
XS Rating Curve= 0
Exp/Cntr=.3,.1

Type RM Length L Ch R = 1 ,500.00  ,50,50,50
BEGIN DESCRIPTION:
10
END DESCRIPTION:
#Sta/Elev= 16
     -10   32.05      -7   31.05      -4   30.05      -2   30.05       0   28.25
     1.3   28.05     4.6   26.05     6.2   26.05     9.7   28.25    10.6   28.25
    13.9   26.05    14.7   26.05    15.3   26.65    15.8   26.65      16   26.45
      26   26.45
#Mann= 3 , 0 , 0
     -10    .033       0       0    .033       0     9.7    .033       0
#XS Ineff= 2 , 0
               0   28.25     9.7           28.25
Permanent Ineff=
       F       F
Bank Sta=0,9.7
XS Rating Curve= 0
Exp/Cntr=.3,.1

Type RM Length L Ch R = 1 ,450.00  ,50,50,50
BEGIN DESCRIPTION:
9
END DESCRIPTION:
#Sta/Elev= 16
     -10   31.35      -7   30.35      -4   29.35      -2   29.35       0   27.55
     1.3   27.35     4.6   25.35     6.2   25.35     9.7   27.45    10.6   27.45
    13.9   25.25    14.7   25.25    15.3   25.85    15.8   25.85      16   25.65
      26   25.65
#Mann= 3 , 0 , 0
     -10    .033       0       0    .033       0     9.7    .033       0
#XS Ineff= 2 , 0
               0   27.55     9.7           27.45
Permanent Ineff=
       F       F
Bank Sta=0,9.7
XS Rating Curve= 0
Exp/Cntr=.3,.1

Type RM Length L Ch R = 1 ,400.00  ,50,50,50
BEGIN DESCRIPTION:
8
END DESCRIPTION:
#Sta/Elev= 15
     -13   28.26      -8   27.96      -3   27.66      -2   26.66       0   26.66
       3   24.66       5   24.66     8.3   26.46       9   26.46    12.3   28.26
    12.9   28.26    13.9   28.96    14.3   28.96    14.6   28.66    24.6   28.66
#Mann= 3 , 0 , 0
     -13    .033       0       0    .033       0    13.9    .033       0
#XS Ineff= 2 , 0
               0   26.66    13.9           28.96
Permanent Ineff=
       F       F
Bank Sta=0,13.9
XS Rating Curve= 0
Exp/Cntr=.3,.1

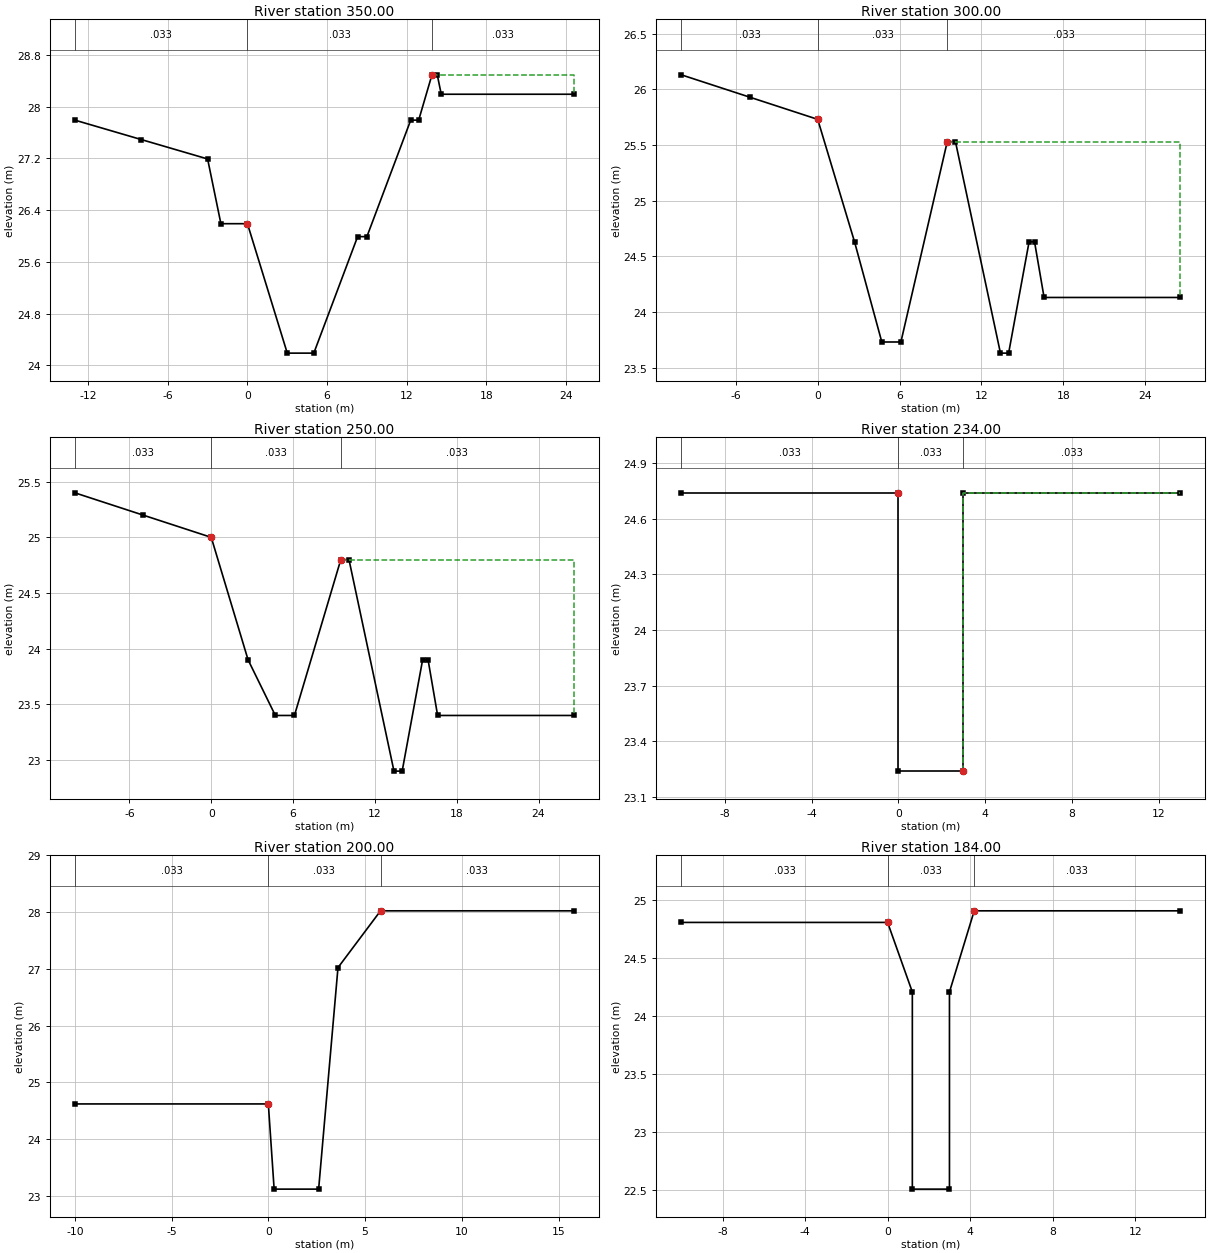
Type RM Length L Ch R = 1 ,350.00  ,50,50,50
BEGIN DESCRIPTION:
7
END DESCRIPTION:
#Sta/Elev= 15
     -13   27.79      -8   27.49      -3   27.19      -2   26.19       0   26.19
       3   24.19       5   24.19     8.3   25.99       9   25.99    12.3   27.79
    12.9   27.79    13.9   28.49    14.3   28.49    14.6   28.19    24.6   28.19
#Mann= 3 , 0 , 0
     -13    .033       0       0    .033       0    13.9    .033       0
#XS Ineff= 2 , 0
               0   26.19    13.9           28.49
Permanent Ineff=
       F       F
Bank Sta=0,13.9
XS Rating Curve= 0
Exp/Cntr=.3,.1

Type RM Length L Ch R = 1 ,300.00  ,50,50,50
BEGIN DESCRIPTION:
6
END DESCRIPTION:
#Sta/Elev= 14
     -10   26.13      -5   25.93       0   25.73     2.7   24.63     4.7   23.73
     6.1   23.73     9.5   25.53    10.1   25.53    13.4   23.63      14   23.63
    15.5   24.63    15.9   24.63    16.6   24.13    26.6   24.13
#Mann= 3 , 0 , 0
     -10    .033       0       0    .033       0     9.5    .033       0
#XS Ineff= 2 , 0
               0   25.73     9.5           25.53
Permanent Ineff=
       F       F
Bank Sta=0,9.5
XS Rating Curve= 0
Exp/Cntr=.3,.1

Type RM Length L Ch R = 1 ,250.00  ,16,16,16
BEGIN DESCRIPTION:
5
END DESCRIPTION:
#Sta/Elev= 14
     -10    25.4      -5    25.2       0      25     2.7    23.9     4.7    23.4
     6.1    23.4     9.5    24.8    10.1    24.8    13.4    22.9      14    22.9
    15.5    23.9    15.9    23.9    16.6    23.4    26.6    23.4
#Mann= 3 , 0 , 0
     -10    .033       0       0    .033       0     9.5    .033       0
#XS Ineff= 2 , 0
               0      25     9.5            24.8
Permanent Ineff=
       F       F
Bank Sta=0,9.5
XS Rating Curve= 0
Exp/Cntr=.3,.1

Type RM Length L Ch R = 1 ,234.00  ,34,34,34
BEGIN DESCRIPTION:
4.034
END DESCRIPTION:
#Sta/Elev= 6
     -10   24.74       0   24.74       0   23.24       3   23.24       3   24.74
      13   24.74
#Mann= 3 , 0 , 0
     -10    .033       0       0    .033       0       3    .033       0
#XS Ineff= 2 , 0
               0   24.74       3           24.74
Permanent Ineff=
       F       F
Bank Sta=0,3
XS Rating Curve= 0
Exp/Cntr=.3,.1

Type RM Length L Ch R = 1 ,200.00  ,16,16,16
BEGIN DESCRIPTION:
4
END DESCRIPTION:
#Sta/Elev= 7
     -10   24.62       0   24.62      .3   23.12     2.6   23.12     3.6   27.02
     5.8   28.02    15.8   28.02
#Mann= 3 , 0 , 0
     -10    .033       0       0    .033       0     5.8    .033       0
#XS Ineff= 2 , 0
               0   24.62     5.8           28.02
Permanent Ineff=
       F       F
Bank Sta=0,5.8
XS Rating Curve= 0
Exp/Cntr=.3,.1

Type RM Length L Ch R = 1 ,184.00  ,34,34,34
BEGIN DESCRIPTION:
3.034
END DESCRIPTION:
#Sta/Elev= 8
     -10   24.81       0   24.81     1.2   24.21     1.2   22.51       3   22.51
       3   24.21     4.2   24.91    14.2   24.91
#Mann= 3 , 0 , 0
     -10    .033       0       0    .033       0     4.2    .033       0
#XS Ineff= 2 , 0
               0   24.81     4.2           24.91
Permanent Ineff=
       F       F
Bank Sta=0,4.2
XS Rating Curve= 0
Exp/Cntr=.3,.1

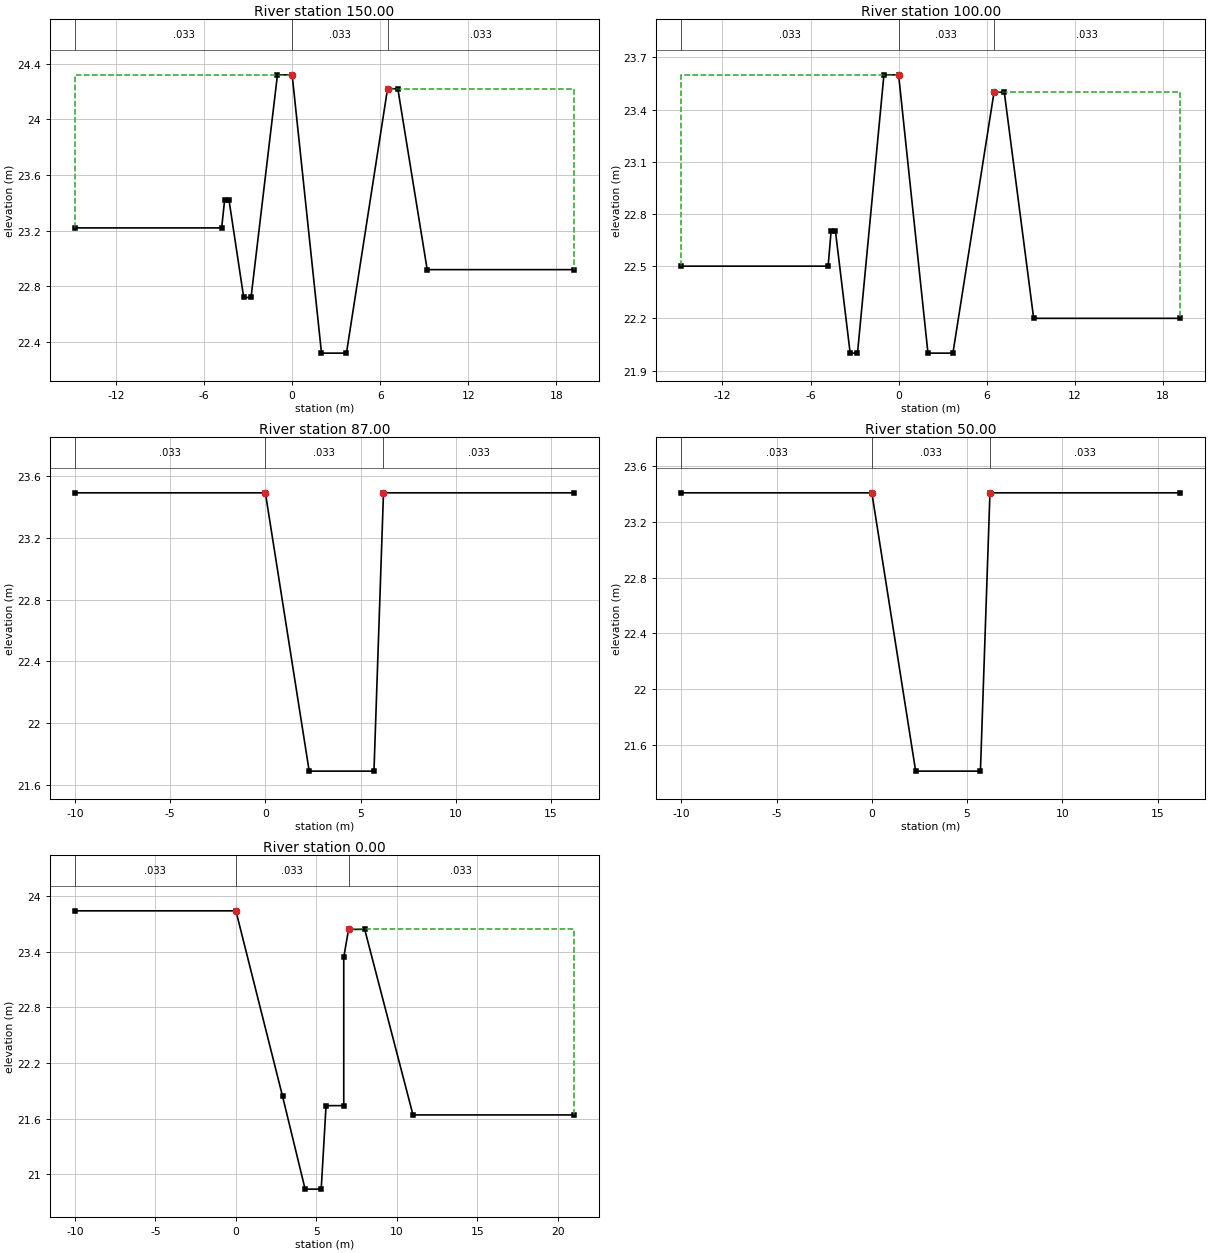
Type RM Length L Ch R = 1 ,150.00  ,50,50,50
BEGIN DESCRIPTION:
3
END DESCRIPTION:
#Sta/Elev= 14
   -14.8   23.22    -4.8   23.22    -4.6   23.42    -4.3   23.42    -3.3   22.72
    -2.8   22.72      -1   24.32       0   24.32       2   22.32     3.7   22.32
     6.5   24.22     7.2   24.22     9.2   22.92    19.2   22.92
#Mann= 3 , 0 , 0
   -14.8    .033       0       0    .033       0     6.5    .033       0
#XS Ineff= 2 , 0
               0   24.32     6.5           24.22
Permanent Ineff=
       F       F
Bank Sta=0,6.5
XS Rating Curve= 0
Exp/Cntr=.3,.1

Type RM Length L Ch R = 1 ,100.00  ,13,13,13
BEGIN DESCRIPTION:
2
END DESCRIPTION:
#Sta/Elev= 14
   -14.8    22.5    -4.8    22.5    -4.6    22.7    -4.3    22.7    -3.3      22
    -2.8      22      -1    23.6       0    23.6       2      22     3.7      22
     6.5    23.5     7.2    23.5     9.2    22.2    19.2    22.2
#Mann= 3 , 0 , 0
   -14.8    .033       0       0    .033       0     6.5    .033       0
#XS Ineff= 2 , 0
               0    23.6     6.5            23.5
Permanent Ineff=
       F       F
Bank Sta=0,6.5
XS Rating Curve= 0
Exp/Cntr=.3,.1

Type RM Length L Ch R = 1 ,87.00   ,37,37,37
BEGIN DESCRIPTION:
1.037
END DESCRIPTION:
#Sta/Elev= 6
     -10   23.49       0   23.49     2.3   21.69     5.7   21.69     6.2   23.49
    16.2   23.49
#Mann= 3 , 0 , 0
     -10    .033       0       0    .033       0     6.2    .033       0
#XS Ineff= 2 , 0
               0   23.49     6.2           23.49
Permanent Ineff=
       F       F
Bank Sta=0,6.2
XS Rating Curve= 0
Exp/Cntr=.3,.1

Type RM Length L Ch R = 1 ,50.00   ,50,50,50
BEGIN DESCRIPTION:
1
END DESCRIPTION:
#Sta/Elev= 6
     -10   23.41       0   23.41     2.3   21.41     5.7   21.41     6.2   23.41
    16.2   23.41
#Mann= 3 , 0 , 0
     -10    .033       0       0    .033       0     6.2    .033       0
#XS Ineff= 2 , 0
               0   23.41     6.2           23.41
Permanent Ineff=
       F       F
Bank Sta=0,6.2
XS Rating Curve= 0
Exp/Cntr=.3,.1

Type RM Length L Ch R = 1 ,0.00    ,0,0,0
BEGIN DESCRIPTION:
0
END DESCRIPTION:
#Sta/Elev= 12
     -10   23.84       0   23.84     2.9   21.84     4.3   20.84     5.3   20.84
     5.6   21.74     6.7   21.74     6.7   23.34       7   23.64       8   23.64
      11   21.64      21   21.64
#Mann= 3 , 0 , 0
     -10    .033       0       0    .033       0       7    .033       0
#XS Ineff= 2 , 0
               0   23.84       7           23.64
Permanent Ineff=
       F       F
Bank Sta=0,7
XS Rating Curve= 0
Exp/Cntr=.3,.1

Chan Stop Cuts=-1