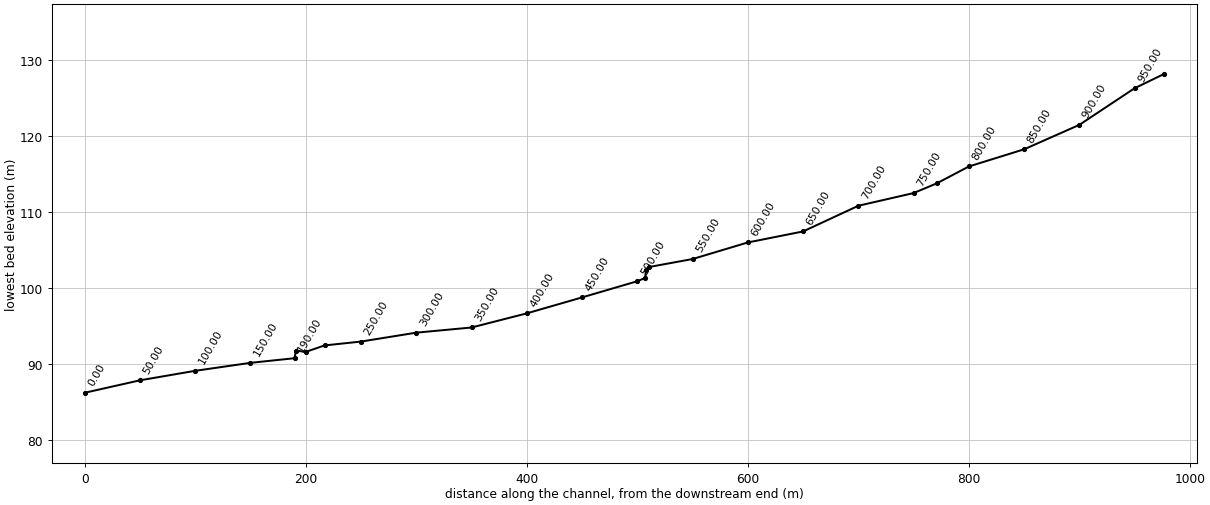
--- SSC.prj (project) ---

Proj Title=sosam-ch
Current Plan=p01
Default Exp/Contr=.3,.1
SI Units
Geom File=g01
Flow File=f01
Plan File=p01
Y Axis Title=Elevation
X Axis Title(PF)=Main Channel Distance
X Axis Title(XS)=Station
BEGIN DESCRIPTION:
           BACK WATER COMPUTATION
      APPLICATION OF HEC-2 BY Samju Construction Engineering
      sosam-ch: 10,20,30,50,80 yr
END DESCRIPTION:
DSS Export Rating Curves= 0
DSS Export Rating Curve Sorted= 0
DSS Export Volume Flow Curves= 0
DXF OffsetX= 0
DXF OffsetY= 0
DXF ScaleX= 1
DXF ScaleY= 10

--- SSC.p01 (plan) ---

Plan Title=Imported Plan 01
Version=Version 3.0.1  Mar 2001
Short Identifier=Imported Pla
Geom File=g01
Flow File=f01
Subcritical Flow
K Sum by GR= 0
Std Step Tol= 0.003
Critical Tol= 0.003
Num of Std Step Trials= 20
Max Error Tol= 0.1
Flow Tol Ratio= 0.001
Split Flow NTrial= 30
Split Flow Tol= 0.02
Split Flow Ratio= 0.02
Log Output Level= 0
Friction Slope Method= 1
Unsteady Friction Slope Method= 2
Parabolic Critical Depth
Global Vel Dist= 0 , 0 , 0
Global Log Level= 0
CheckData=True
Encroach Param=-1 ,0,0, 0
Computation Interval=1HOUR
Output Interval=1HOUR
Run HTab= 0
Run UNet= 0
Run PostProcess= 0
UNET Theta= 1
UNET ZTol= 0.02
UNET ZSATol= 0.1
UNET MxIter= 20
UNET MaxInSteps= 20
UNET DtIC= 0
UNET DtMin= 0
UNET MaxCRTS= 20
UNET WFStab= 2
UNET SFStab= 1
UNET WFX= 1
UNET SFX= 1
UNET Convert EG Bridges=-1
UNET Use Existing IB Tables=-1
Instantaneous Interval=1HOUR
Write IC File= 0
Write Velocity= 0
Write Detailed= 0

--- SSC.f01 (steady flow) ---

Flow Title=Imported Flow 01
Version=Version 3.0.1  Mar 2001
Number of Profiles= 5
Profile Names=10YR,20YR,30YR,50YR,80YR
River Rch & RM=RIVER-1,Reach-1         ,977.00
   29.54   32.53   34.28   36.48   38.51
Boundary for River Rch & Prof#=RIVER-1,Reach-1         , 1
Up Type= 0
Dn Type= 3
Dn Slope=.026
Boundary for River Rch & Prof#=RIVER-1,Reach-1         , 2
Up Type= 0
Dn Type= 3
Dn Slope=.026
Boundary for River Rch & Prof#=RIVER-1,Reach-1         , 3
Up Type= 0
Dn Type= 3
Dn Slope=.026
Boundary for River Rch & Prof#=RIVER-1,Reach-1         , 4
Up Type= 0
Dn Type= 3
Dn Slope=.026
Boundary for River Rch & Prof#=RIVER-1,Reach-1         , 5
Up Type= 0
Dn Type= 3
Dn Slope=.026
DSS Import GetInterval= 0
DSS Import GetPeak= 0
DSS Import FillOption= 0

--- SSC.g01 (geometry) ---

Geom Title=Imported Geom 01
Version=Version 3.0.1  Mar 2001

River Reach=RIVER-1         ,Reach-1
Reach XY= 2
              .5             .95              .5             .05

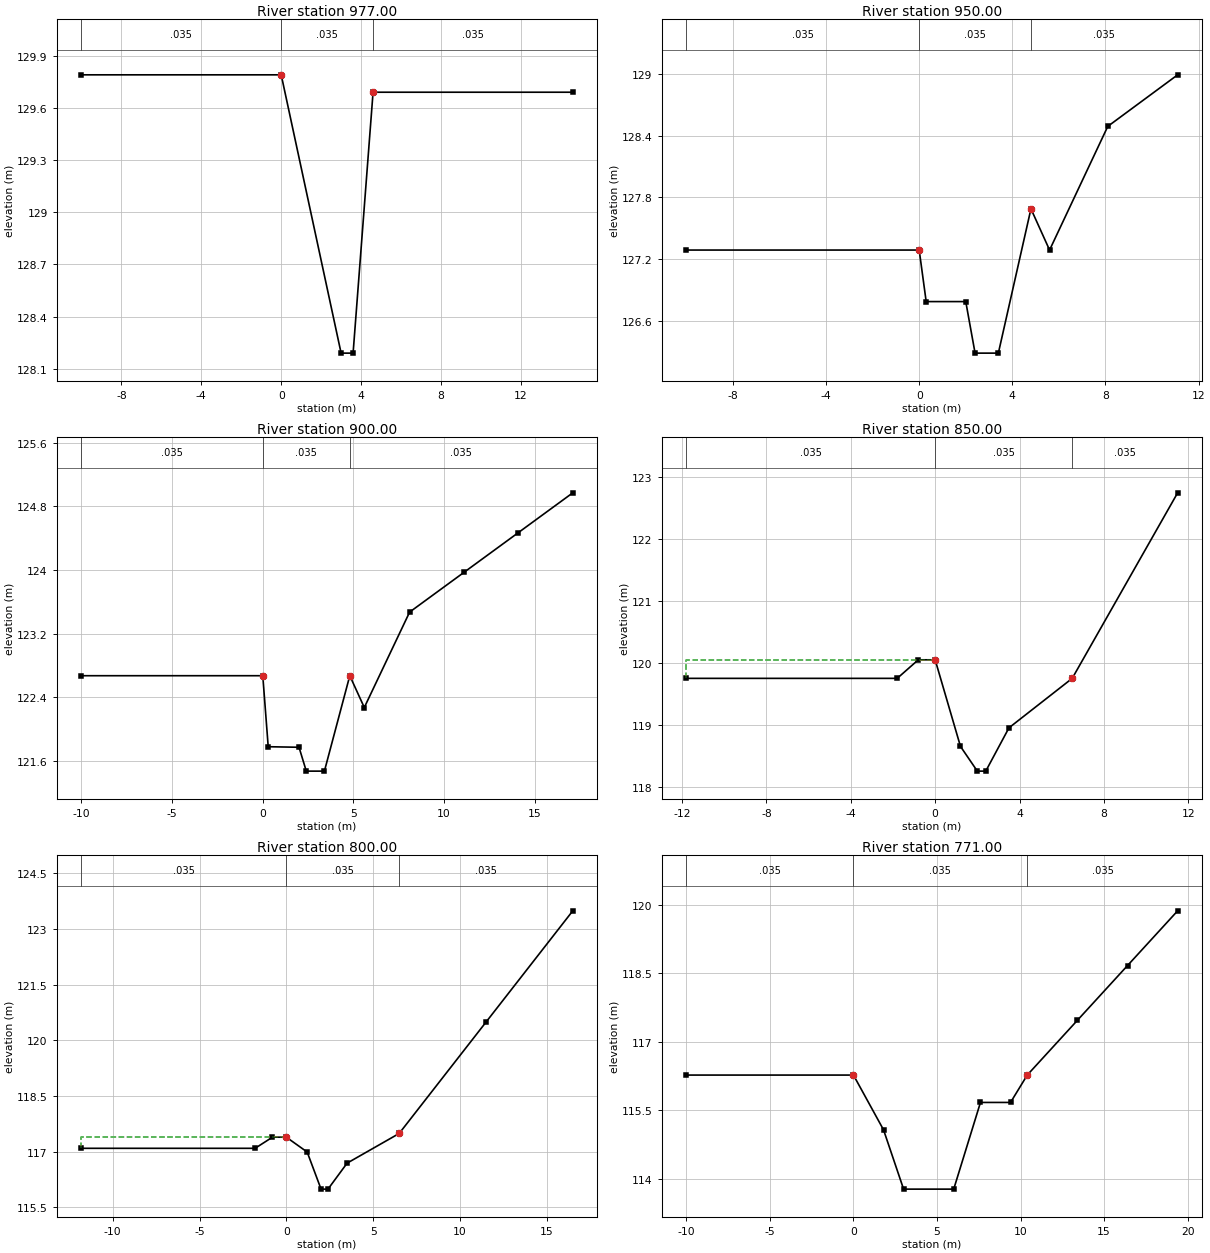
Type RM Length L Ch R = 1 ,977.00  ,27,27,27
BEGIN DESCRIPTION:
19.027
END DESCRIPTION:
#Sta/Elev= 6
     -10  129.79       0  129.79       3  128.19     3.6  128.19     4.6  129.69
    14.6  129.69
#Mann= 3 , 0 , 0
     -10    .035       0       0    .035       0     4.6    .035       0
#XS Ineff= 2 , 0
               0  129.79     4.6          129.69
Permanent Ineff=
       F       F
Bank Sta=0,4.6
XS Rating Curve= 0
Exp/Cntr=.3,.1

Type RM Length L Ch R = 1 ,950.00  ,50,50,50
BEGIN DESCRIPTION:
19
END DESCRIPTION:
#Sta/Elev= 10
     -10  127.29       0  127.29      .3  126.79       2  126.79     2.4  126.29
     3.4  126.29     4.8  127.69     5.6  127.29     8.1  128.49    11.1  128.99
#Mann= 3 , 0 , 0
     -10    .035       0       0    .035       0     4.8    .035       0
#XS Ineff= 2 , 0
               0  127.29     4.8          127.69
Permanent Ineff=
       F       F
Bank Sta=0,4.8
XS Rating Curve= 0
Exp/Cntr=.3,.1

Type RM Length L Ch R = 1 ,900.00  ,50,50,50
BEGIN DESCRIPTION:
18
END DESCRIPTION:
#Sta/Elev= 12
     -10  122.67       0  122.67      .3 121.777       2  121.77     2.4  121.47
     3.4  121.47     4.8  122.67     5.6  122.27     8.1  123.47    11.1  123.97
    14.1  124.47    17.1  124.97
#Mann= 3 , 0 , 0
     -10    .035       0       0    .035       0     4.8    .035       0
#XS Ineff= 2 , 0
               0  122.67     4.8          122.67
Permanent Ineff=
       F       F
Bank Sta=0,4.8
XS Rating Curve= 0
Exp/Cntr=.3,.1

Type RM Length L Ch R = 1 ,850.00  ,50,50,50
BEGIN DESCRIPTION:
17
END DESCRIPTION:
#Sta/Elev= 10
   -11.8  119.75    -1.8  119.75     -.8  120.05       0  120.05     1.2  118.65
       2  118.25     2.4  118.25     3.5  118.95     6.5  119.75    11.5  122.75
#Mann= 3 , 0 , 0
   -11.8    .035       0       0    .035       0     6.5    .035       0
#XS Ineff= 2 , 0
               0  120.05     6.5          119.75
Permanent Ineff=
       F       F
Bank Sta=0,6.5
XS Rating Curve= 0
Exp/Cntr=.3,.1

Type RM Length L Ch R = 1 ,800.00  ,29,29,29
BEGIN DESCRIPTION:
16
END DESCRIPTION:
#Sta/Elev= 11
   -11.8  117.09    -1.8  117.09     -.8  117.39       0  117.39     1.2  116.99
       2  115.99     2.4  115.99     3.5  116.69     6.5  117.49    11.5  120.49
    16.5  123.49
#Mann= 3 , 0 , 0
   -11.8    .035       0       0    .035       0     6.5    .035       0
#XS Ineff= 2 , 0
               0  117.39     6.5          117.49
Permanent Ineff=
       F       F
Bank Sta=0,6.5
XS Rating Curve= 0
Exp/Cntr=.3,.1

Type RM Length L Ch R = 1 ,771.00  ,21,21,21
BEGIN DESCRIPTION:
15.021
END DESCRIPTION:
#Sta/Elev= 11
     -10  116.27       0  116.27     1.8  115.07       3  113.77       6  113.77
     7.6  115.67     9.4  115.67    10.4  116.27    13.4  117.47    16.4  118.67
    19.4  119.87
#Mann= 3 , 0 , 0
     -10    .035       0       0    .035       0    10.4    .035       0
#XS Ineff= 2 , 0
               0  116.27    10.4          116.27
Permanent Ineff=
       F       F
Bank Sta=0,10.4
XS Rating Curve= 0
Exp/Cntr=.3,.1

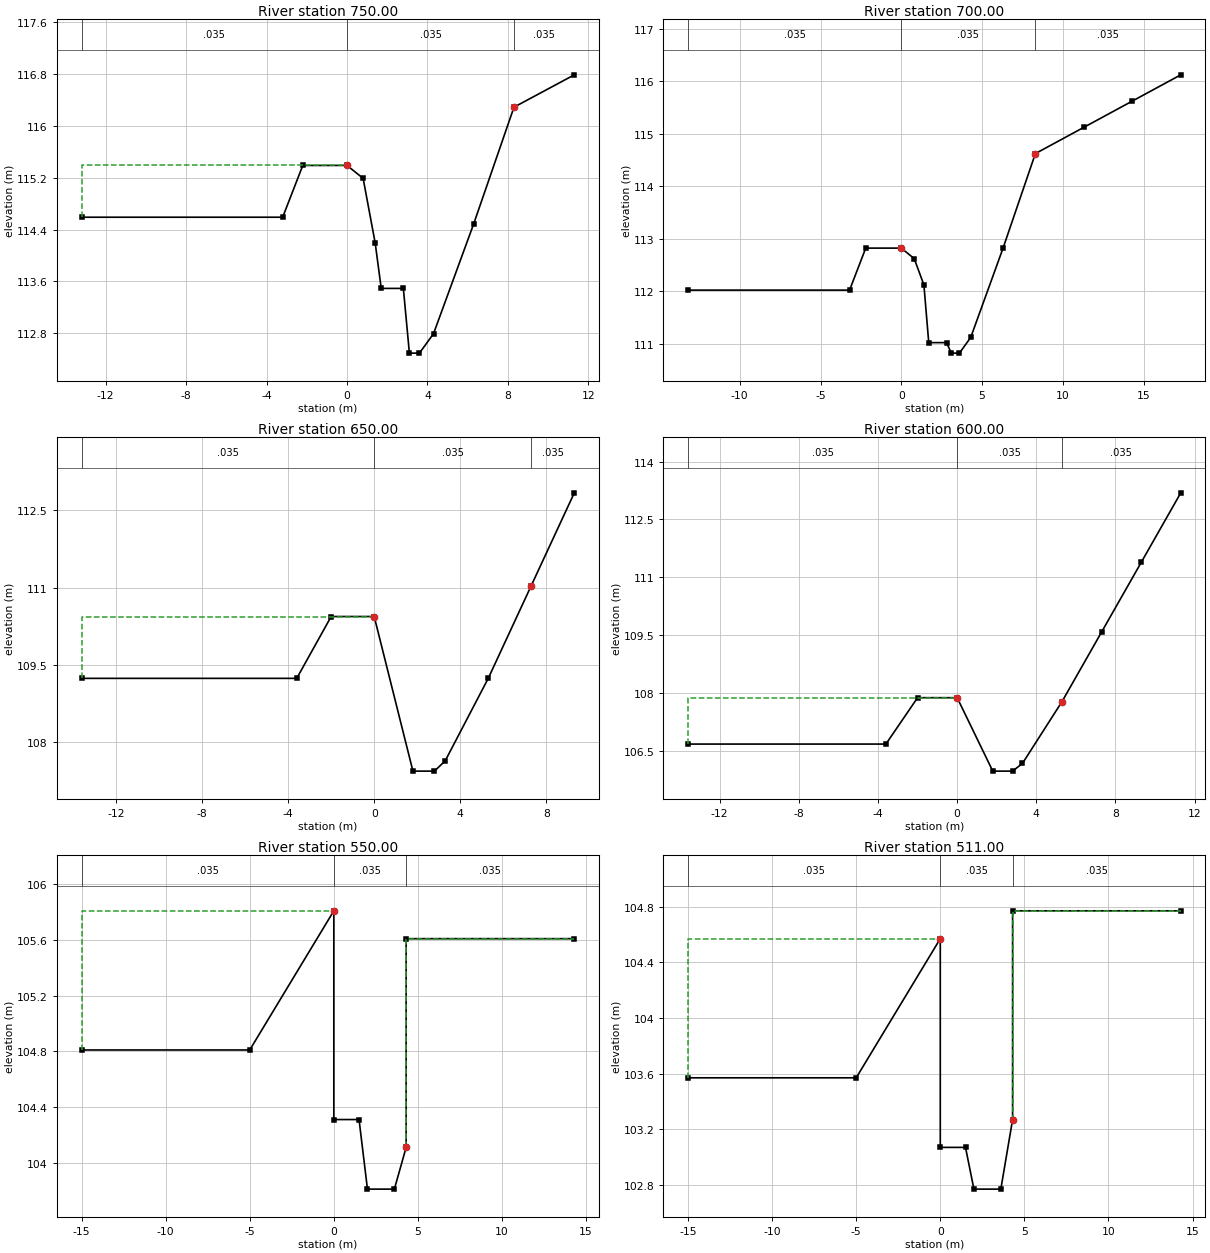
Type RM Length L Ch R = 1 ,750.00  ,50,50,50
BEGIN DESCRIPTION:
15
END DESCRIPTION:
#Sta/Elev= 14
   -13.2  114.59    -3.2  114.59    -2.2  115.39       0  115.39      .8  115.19
     1.4  114.19     1.7  113.49     2.8  113.49     3.1  112.49     3.6  112.49
     4.3  112.79     6.3  114.49     8.3  116.29    11.3  116.79
#Mann= 3 , 0 , 0
   -13.2    .035       0       0    .035       0     8.3    .035       0
#XS Ineff= 2 , 0
               0  115.39     8.3          116.29
Permanent Ineff=
       F       F
Bank Sta=0,8.3
XS Rating Curve= 0
Exp/Cntr=.3,.1

Type RM Length L Ch R = 1 ,700.00  ,50,50,50
BEGIN DESCRIPTION:
14
END DESCRIPTION:
#Sta/Elev= 16
   -13.2  112.02    -3.2  112.02    -2.2  112.82       0  112.82      .8  112.62
     1.4  112.12     1.7  111.02     2.8  111.02     3.1  110.82     3.6  110.82
     4.3  111.12     6.3  112.82     8.3  114.62    11.3  115.12    14.3  115.62
    17.3  116.12
#Mann= 3 , 0 , 0
   -13.2    .035       0       0    .035       0     8.3    .035       0
#XS Ineff= 2 , 0
       0       0  112.82     8.3       0  114.62
Permanent Ineff=
       F       F
Bank Sta=0,8.3
XS Rating Curve= 0
Exp/Cntr=.3,.1

Type RM Length L Ch R = 1 ,650.00  ,50,50,50
BEGIN DESCRIPTION:
13
END DESCRIPTION:
#Sta/Elev= 10
   -13.6  109.24    -3.6  109.24      -2  110.44       0  110.44     1.8  107.44
     2.8  107.44     3.3  107.64     5.3  109.24     7.3  111.04     9.3  112.84
#Mann= 3 , 0 , 0
   -13.6    .035       0       0    .035       0     7.3    .035       0
#XS Ineff= 2 , 0
               0  110.44     7.3          111.04
Permanent Ineff=
       F       F
Bank Sta=0,7.3
XS Rating Curve= 0
Exp/Cntr=.3,.1

Type RM Length L Ch R = 1 ,600.00  ,50,50,50
BEGIN DESCRIPTION:
12
END DESCRIPTION:
#Sta/Elev= 11
   -13.6  106.69    -3.6  106.69      -2  107.89       0  107.89     1.8  105.99
     2.8  105.99     3.3  106.19     5.3  107.79     7.3  109.59     9.3  111.39
    11.3  113.19
#Mann= 3 , 0 , 0
   -13.6    .035       0       0    .035       0     5.3    .035       0
#XS Ineff= 2 , 0
               0  107.89     5.3          107.79
Permanent Ineff=
       F       F
Bank Sta=0,5.3
XS Rating Curve= 0
Exp/Cntr=.3,.1

Type RM Length L Ch R = 1 ,550.00  ,39,39,39
BEGIN DESCRIPTION:
11
END DESCRIPTION:
#Sta/Elev= 10
     -15  104.81      -5  104.81       0  105.81       0  104.31     1.5  104.31
       2  103.81     3.6  103.81     4.3  104.11     4.3  105.61    14.3  105.61
#Mann= 3 , 0 , 0
     -15    .035       0       0    .035       0     4.3    .035       0
#XS Ineff= 2 , 0
               0  105.81     4.3          105.61
Permanent Ineff=
       F       F
Bank Sta=0,4.3
XS Rating Curve= 0
Exp/Cntr=.3,.1

Type RM Length L Ch R = 1 ,511.00  ,3,3,3
BEGIN DESCRIPTION:
10.011
END DESCRIPTION:
#Sta/Elev= 10
     -15  103.57      -5  103.57       0  104.57       0  103.07     1.5  103.07
       2  102.77     3.6  102.77     4.3  103.27     4.3  104.77    14.3  104.77
#Mann= 3 , 0 , 0
     -15    .035       0       0    .035       0     4.3    .035       0
#XS Ineff= 2 , 0
               0  104.57     4.3          104.77
Permanent Ineff=
       F       F
Bank Sta=0,4.3
XS Rating Curve= 0
Exp/Cntr=.3,.1

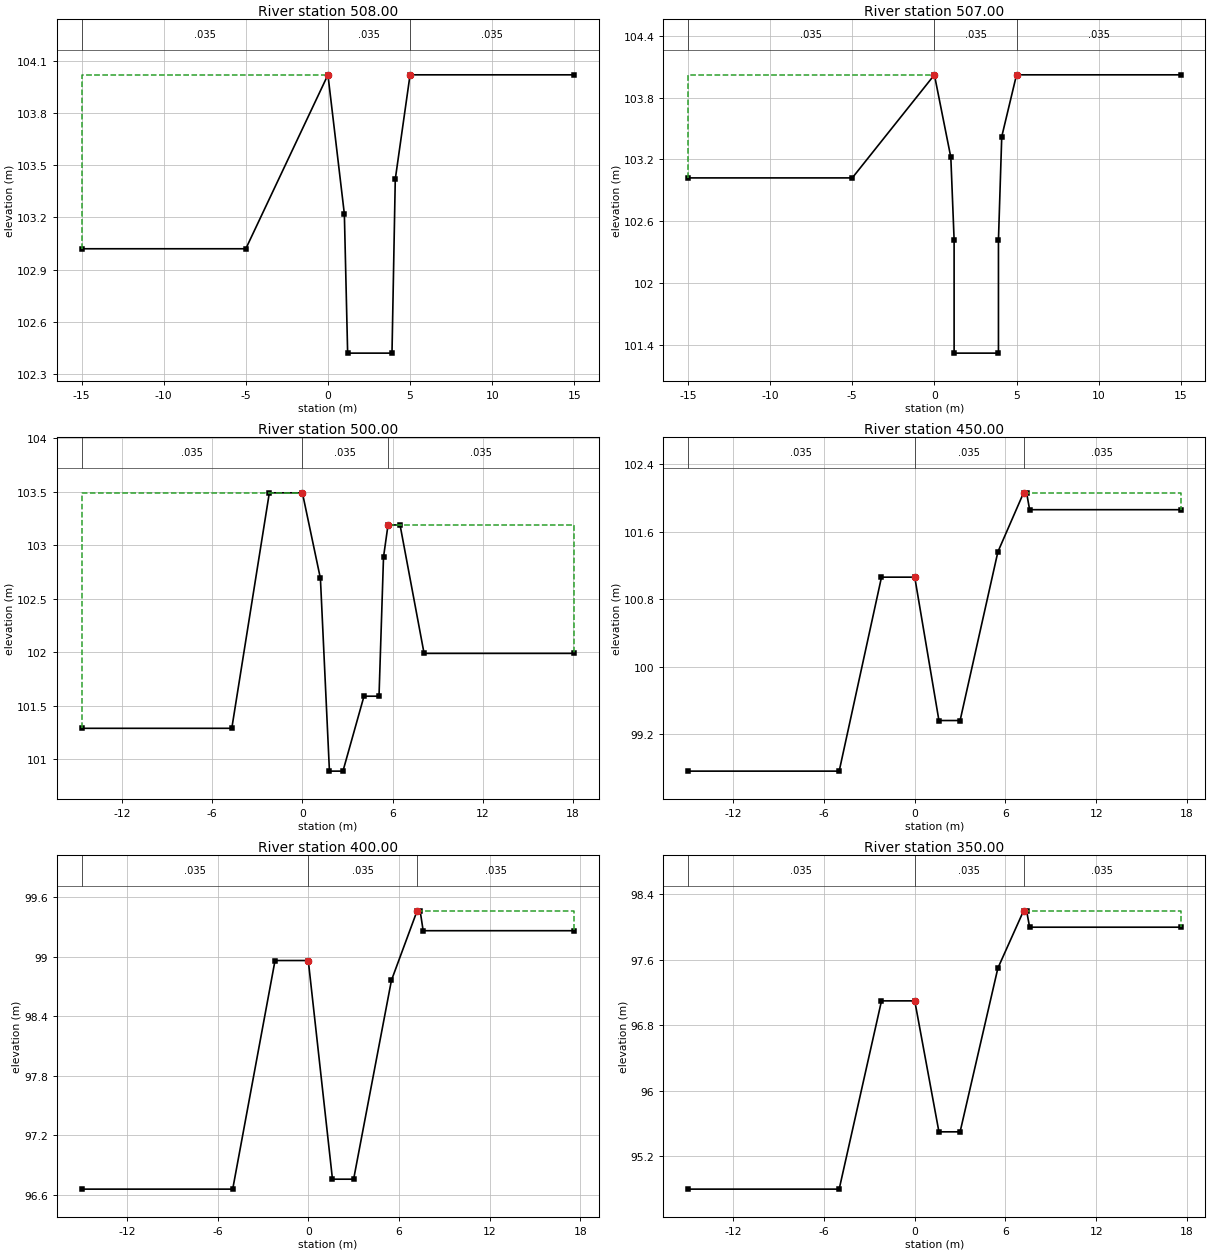
Type RM Length L Ch R = 1 ,508.00  ,1,1,1
BEGIN DESCRIPTION:
10.008
END DESCRIPTION:
#Sta/Elev= 9
     -15  103.02      -5  103.02       0  104.02       1  103.22     1.2  102.42
     3.9  102.42     4.1  103.42       5  104.02      15  104.02
#Mann= 3 , 0 , 0
     -15    .035       0       0    .035       0       5    .035       0
#XS Ineff= 2 , 0
               0  104.02       5          104.02
Permanent Ineff=
       F       F
Bank Sta=0,5
XS Rating Curve= 0
Exp/Cntr=.3,.1

Type RM Length L Ch R = 1 ,507.00  ,7,7,7
BEGIN DESCRIPTION:
10.007
END DESCRIPTION:
#Sta/Elev= 11
     -15  103.02      -5  103.02       0  104.02       1  103.22     1.2  102.42
     1.2  101.32     3.9  101.32     3.9  102.42     4.1  103.42       5  104.02
      15  104.02
#Mann= 3 , 0 , 0
     -15    .035       0       0    .035       0       5    .035       0
#XS Ineff= 2 , 0
               0  104.02       5          104.02
Permanent Ineff=
       F       F
Bank Sta=0,5
XS Rating Curve= 0
Exp/Cntr=.3,.1

Type RM Length L Ch R = 1 ,500.00  ,50,50,50
BEGIN DESCRIPTION:
10
END DESCRIPTION:
#Sta/Elev= 14
   -14.7  101.29    -4.7  101.29    -2.2  103.49       0  103.49     1.2  102.69
     1.8  100.89     2.7  100.89     4.1  101.59     5.1  101.59     5.4  102.89
     5.7  103.19     6.5  103.19     8.1  101.99    18.1  101.99
#Mann= 3 , 0 , 0
   -14.7    .035       0       0    .035       0     5.7    .035       0
#XS Ineff= 2 , 0
               0  103.49     5.7          103.19
Permanent Ineff=
       F       F
Bank Sta=0,5.7
XS Rating Curve= 0
Exp/Cntr=.3,.1

Type RM Length L Ch R = 1 ,450.00  ,50,50,50
BEGIN DESCRIPTION:
9
END DESCRIPTION:
#Sta/Elev= 11
     -15   98.76      -5   98.76    -2.2  101.06       0  101.06     1.6   99.36
       3   99.36     5.5  101.36     7.2  102.06     7.4  102.06     7.6  101.86
    17.6  101.86
#Mann= 3 , 0 , 0
     -15    .035       0       0    .035       0     7.2    .035       0
#XS Ineff= 2 , 0
       0       0  101.06     7.2       0  102.06
Permanent Ineff=
       F       F
Bank Sta=0,7.2
XS Rating Curve= 0
Exp/Cntr=.3,.1

Type RM Length L Ch R = 1 ,400.00  ,50,50,50
BEGIN DESCRIPTION:
8
END DESCRIPTION:
#Sta/Elev= 11
     -15   96.66      -5   96.66    -2.2   98.96       0   98.96     1.6   96.76
       3   96.76     5.5   98.76     7.2   99.46     7.4   99.46     7.6   99.26
    17.6   99.26
#Mann= 3 , 0 , 0
     -15    .035       0       0    .035       0     7.2    .035       0
#XS Ineff= 2 , 0
       0       0   98.96     7.2       0   99.46
Permanent Ineff=
       F       F
Bank Sta=0,7.2
XS Rating Curve= 0
Exp/Cntr=.3,.1

Type RM Length L Ch R = 1 ,350.00  ,50,50,50
BEGIN DESCRIPTION:
7
END DESCRIPTION:
#Sta/Elev= 11
     -15    94.8      -5    94.8    -2.2    97.1       0    97.1     1.6    95.5
       3    95.5     5.5    97.5     7.2    98.2     7.4    98.2     7.6      98
    17.6      98
#Mann= 3 , 0 , 0
     -15    .035       0       0    .035       0     7.2    .035       0
#XS Ineff= 2 , 0
       0       0    97.1     7.2       0    98.2
Permanent Ineff=
       F       F
Bank Sta=0,7.2
XS Rating Curve= 0
Exp/Cntr=.3,.1

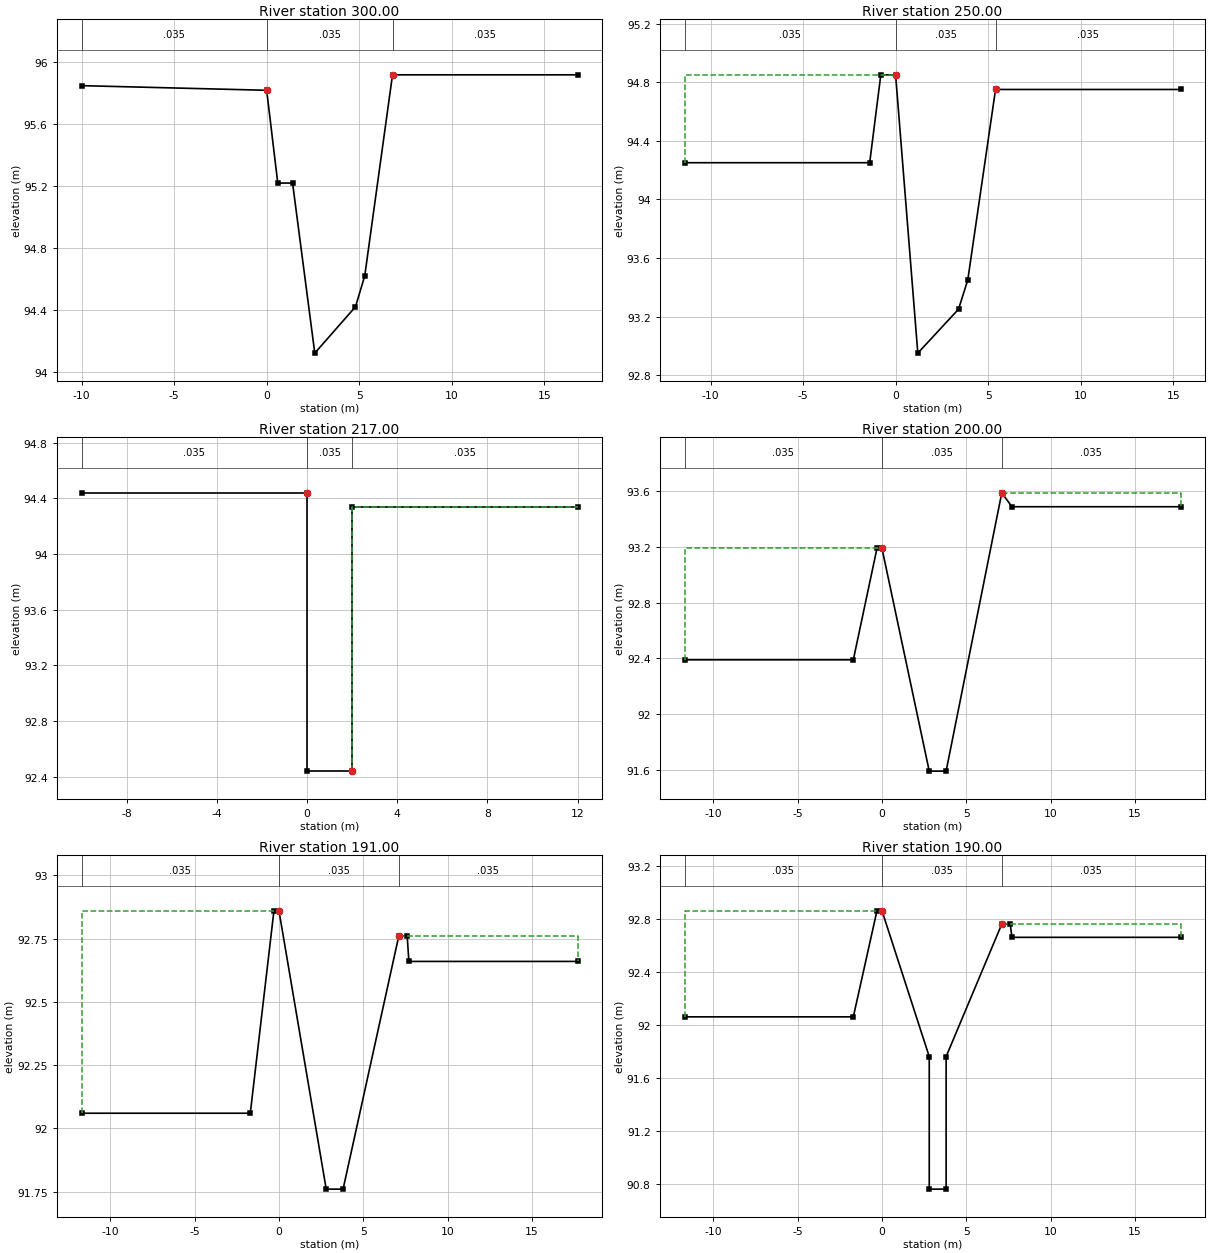
Type RM Length L Ch R = 1 ,300.00  ,50,50,50
BEGIN DESCRIPTION:
6
END DESCRIPTION:
#Sta/Elev= 9
     -10   95.85       0   95.82      .6   95.22     1.4   95.22     2.6   94.12
     4.8   94.42     5.3   94.62     6.8   95.92    16.8   95.92
#Mann= 3 , 0 , 0
     -10    .035       0       0    .035       0     6.8    .035       0
#XS Ineff= 2 , 0
               0   95.82     6.8           95.92
Permanent Ineff=
       F       F
Bank Sta=0,6.8
XS Rating Curve= 0
Exp/Cntr=.3,.1

Type RM Length L Ch R = 1 ,250.00  ,33,33,33
BEGIN DESCRIPTION:
5
END DESCRIPTION:
#Sta/Elev= 9
   -11.4   94.25    -1.4   94.25     -.8   94.85       0   94.85     1.2   92.95
     3.4   93.25     3.9   93.45     5.4   94.75    15.4   94.75
#Mann= 3 , 0 , 0
   -11.4    .035       0       0    .035       0     5.4    .035       0
#XS Ineff= 2 , 0
               0   94.85     5.4           94.75
Permanent Ineff=
       F       F
Bank Sta=0,5.4
XS Rating Curve= 0
Exp/Cntr=.3,.1

Type RM Length L Ch R = 1 ,217.00  ,17,17,17
BEGIN DESCRIPTION:
4.017
END DESCRIPTION:
#Sta/Elev= 6
     -10   94.44       0   94.44       0   92.44       2   92.44       2   94.34
      12   94.34
#Mann= 3 , 0 , 0
     -10    .035       0       0    .035       0       2    .035       0
#XS Ineff= 2 , 0
               0   94.44       2           94.34
Permanent Ineff=
       F       F
Bank Sta=0,2
XS Rating Curve= 0
Exp/Cntr=.3,.1

Type RM Length L Ch R = 1 ,200.00  ,9,9,9
BEGIN DESCRIPTION:
4
END DESCRIPTION:
#Sta/Elev= 9
   -11.7   92.39    -1.7   92.39     -.3   93.19       0   93.19     2.8   91.59
     3.8   91.59     7.1   93.59     7.7   93.49    17.7   93.49
#Mann= 3 , 0 , 0
   -11.7    .035       0       0    .035       0     7.1    .035       0
#XS Ineff= 2 , 0
               0   93.19     7.1           93.59
Permanent Ineff=
       F       F
Bank Sta=0,7.1
XS Rating Curve= 0
Exp/Cntr=.3,.1

Type RM Length L Ch R = 1 ,191.00  ,1,1,1
BEGIN DESCRIPTION:
3.041
END DESCRIPTION:
#Sta/Elev= 10
   -11.7   92.06    -1.7   92.06     -.3   92.86       0   92.86     2.8   91.76
     3.8   91.76     7.1   92.76     7.6   92.76     7.7   92.66    17.7   92.66
#Mann= 3 , 0 , 0
   -11.7    .035       0       0    .035       0     7.1    .035       0
#XS Ineff= 2 , 0
               0   92.86     7.1           92.76
Permanent Ineff=
       F       F
Bank Sta=0,7.1
XS Rating Curve= 0
Exp/Cntr=.3,.1

Type RM Length L Ch R = 1 ,190.00  ,40,40,40
BEGIN DESCRIPTION:
3.04
END DESCRIPTION:
#Sta/Elev= 12
   -11.7   92.06    -1.7   92.06     -.3   92.86       0   92.86     2.8   91.76
     2.8   90.76     3.8   90.76     3.8   91.76     7.1   92.76     7.6   92.76
     7.7   92.66    17.7   92.66
#Mann= 3 , 0 , 0
   -11.7    .035       0       0    .035       0     7.1    .035       0
#XS Ineff= 2 , 0
               0   92.86     7.1           92.76
Permanent Ineff=
       F       F
Bank Sta=0,7.1
XS Rating Curve= 0
Exp/Cntr=.3,.1

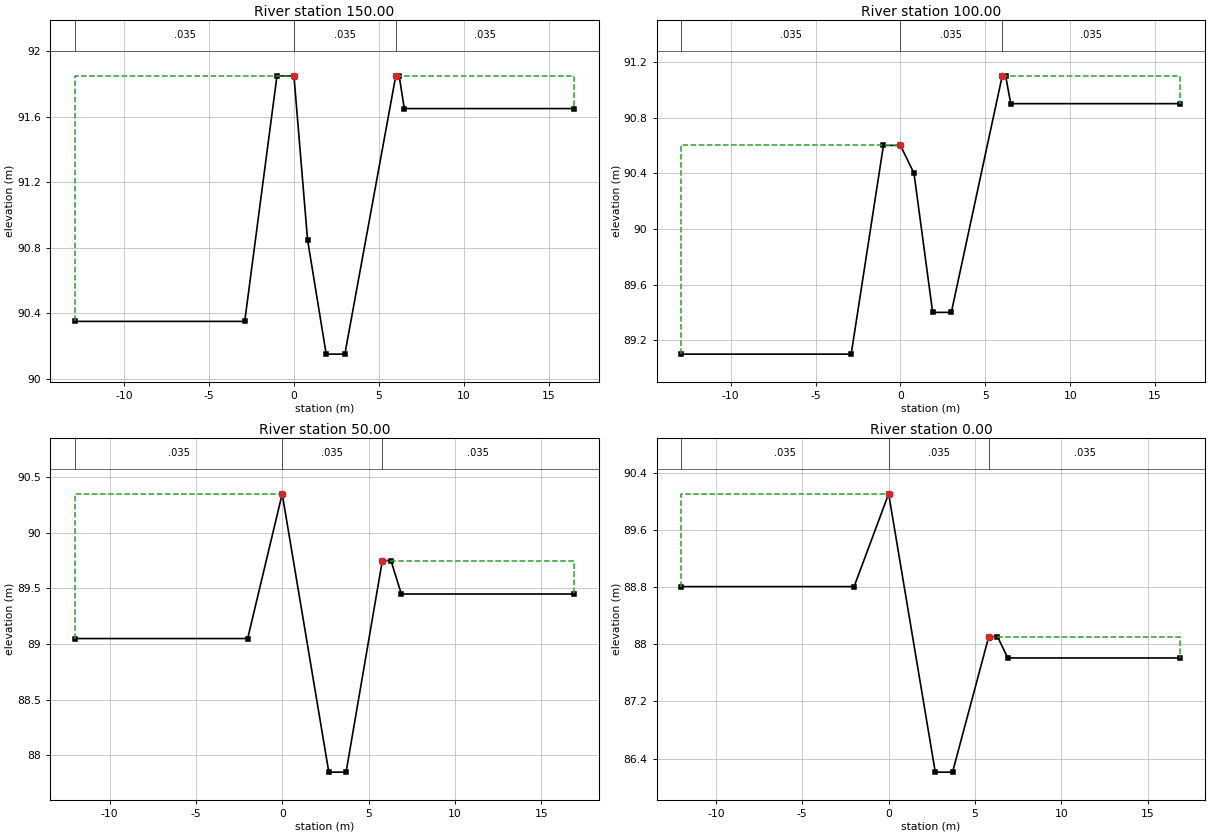
Type RM Length L Ch R = 1 ,150.00  ,50,50,50
BEGIN DESCRIPTION:
3
END DESCRIPTION:
#Sta/Elev= 11
   -12.9   90.35    -2.9   90.35      -1   91.85       0   91.85      .8   90.85
     1.9   90.15       3   90.15       6   91.85     6.2   91.85     6.5   91.65
    16.5   91.65
#Mann= 3 , 0 , 0
   -12.9    .035       0       0    .035       0       6    .035       0
#XS Ineff= 2 , 0
               0   91.85       6           91.85
Permanent Ineff=
       F       F
Bank Sta=0,6
XS Rating Curve= 0
Exp/Cntr=.3,.1

Type RM Length L Ch R = 1 ,100.00  ,50,50,50
BEGIN DESCRIPTION:
2
END DESCRIPTION:
#Sta/Elev= 11
   -12.9    89.1    -2.9    89.1      -1    90.6       0    90.6      .8    90.4
     1.9    89.4       3    89.4       6    91.1     6.2    91.1     6.5    90.9
    16.5    90.9
#Mann= 3 , 0 , 0
   -12.9    .035       0       0    .035       0       6    .035       0
#XS Ineff= 2 , 0
               0    90.6       6            91.1
Permanent Ineff=
       F       F
Bank Sta=0,6
XS Rating Curve= 0
Exp/Cntr=.3,.1

Type RM Length L Ch R = 1 ,50.00   ,50,50,50
BEGIN DESCRIPTION:
1
END DESCRIPTION:
#Sta/Elev= 9
     -12   89.05      -2   89.05       0   90.35     2.7   87.85     3.7   87.85
     5.8   89.75     6.3   89.75     6.9   89.45    16.9   89.45
#Mann= 3 , 0 , 0
     -12    .035       0       0    .035       0     5.8    .035       0
#XS Ineff= 2 , 0
               0   90.35     5.8           89.75
Permanent Ineff=
       F       F
Bank Sta=0,5.8
XS Rating Curve= 0
Exp/Cntr=.3,.1

Type RM Length L Ch R = 1 ,0.00    ,0,0,0
BEGIN DESCRIPTION:
0
END DESCRIPTION:
#Sta/Elev= 9
     -12   88.81      -2   88.81       0   90.11     2.7   86.21     3.7   86.21
     5.8   88.11     6.3   88.11     6.9   87.81    16.9   87.81
#Mann= 3 , 0 , 0
     -12    .035       0       0    .035       0     5.8    .035       0
#XS Ineff= 2 , 0
               0   90.11     5.8           88.11
Permanent Ineff=
       F       F
Bank Sta=0,5.8
XS Rating Curve= 0
Exp/Cntr=.3,.1

Chan Stop Cuts=-1
BackGround Picture=C:\ÀÚ·á½Ç\³ë·¡¹æ\ºñµÍ¹æ\2.jpg, 0 ,0.0467665,0.9254237,0.959,0.041