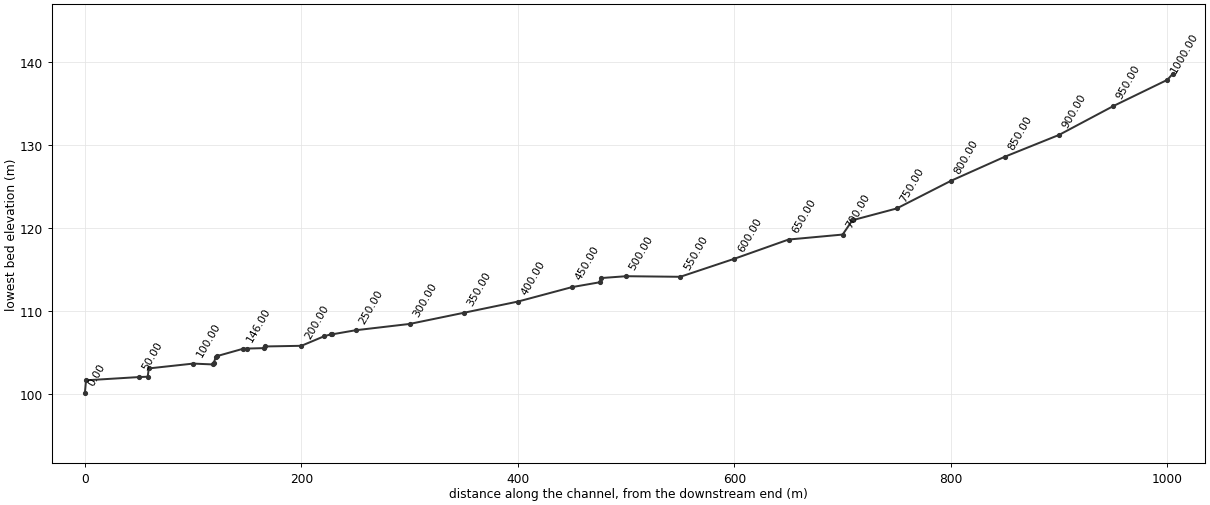
--- TBC.prj (project) ---

Proj Title=taedong-ch
Current Plan=p01
Default Exp/Contr=.3,.1
SI Units
Geom File=g01
Flow File=f01
Plan File=p01
Y Axis Title=Elevation
X Axis Title(PF)=Main Channel Distance
X Axis Title(XS)=Station
BEGIN DESCRIPTION:
           BACK WATER COMPUTATION
      APPLICATION OF HEC-2 BY Samju Construction Engineering
      taedong-ch: 10,20,30,50,80 yr
END DESCRIPTION:
DSS Export Rating Curves= 0
DSS Export Rating Curve Sorted= 0
DSS Export Volume Flow Curves= 0
DXF OffsetX= 0
DXF OffsetY= 0
DXF ScaleX= 1
DXF ScaleY= 10

--- TBC.p01 (plan) ---

Plan Title=Imported Plan 01
Version=Version 3.0.1  Mar 2001
Short Identifier=Imported Pla
Geom File=g01
Flow File=f01
Subcritical Flow
K Sum by GR= 0
Std Step Tol= 0.003
Critical Tol= 0.003
Num of Std Step Trials= 20
Max Error Tol= 0.1
Flow Tol Ratio= 0.001
Split Flow NTrial= 30
Split Flow Tol= 0.02
Split Flow Ratio= 0.02
Log Output Level= 0
Friction Slope Method= 1
Unsteady Friction Slope Method= 2
Parabolic Critical Depth
Global Vel Dist= 0 , 0 , 0
Global Log Level= 0
CheckData=True
Encroach Param=-1 ,0,0, 0
Computation Interval=1HOUR
Output Interval=1HOUR
Run HTab= 0
Run UNet= 0
Run PostProcess= 0
UNET Theta= 1
UNET ZTol= 0.02
UNET ZSATol= 0.1
UNET MxIter= 20
UNET MaxInSteps= 20
UNET DtIC= 0
UNET DtMin= 0
UNET MaxCRTS= 20
UNET WFStab= 2
UNET SFStab= 1
UNET WFX= 1
UNET SFX= 1
UNET Convert EG Bridges=-1
UNET Use Existing IB Tables=-1
Instantaneous Interval=1HOUR
Write IC File= 0
Write Velocity= 0
Write Detailed= 0

--- TBC.f01 (steady flow) ---

Flow Title=Imported Flow 01
Version=Version 3.0.1  Mar 2001
Number of Profiles= 5
Profile Names=10YR,20YR,30YR,50YR,80YR
River Rch & RM=RIVER-1,Reach-1         ,1005.00
   12.64   13.92   14.67   15.62   16.49
Boundary for River Rch & Prof#=RIVER-1,Reach-1         , 1
Up Type= 0
Dn Type= 3
Dn Slope=.022
Boundary for River Rch & Prof#=RIVER-1,Reach-1         , 2
Up Type= 0
Dn Type= 3
Dn Slope=.022
Boundary for River Rch & Prof#=RIVER-1,Reach-1         , 3
Up Type= 0
Dn Type= 3
Dn Slope=.022
Boundary for River Rch & Prof#=RIVER-1,Reach-1         , 4
Up Type= 0
Dn Type= 3
Dn Slope=.022
Boundary for River Rch & Prof#=RIVER-1,Reach-1         , 5
Up Type= 0
Dn Type= 3
Dn Slope=.022
DSS Import GetInterval= 0
DSS Import GetPeak= 0
DSS Import FillOption= 0

--- TBC.g01 (geometry) ---

Geom Title=Imported Geom 01
Version=Version 3.0.1  Mar 2001

River Reach=RIVER-1         ,Reach-1
Reach XY= 2
              .5             .95              .5             .05

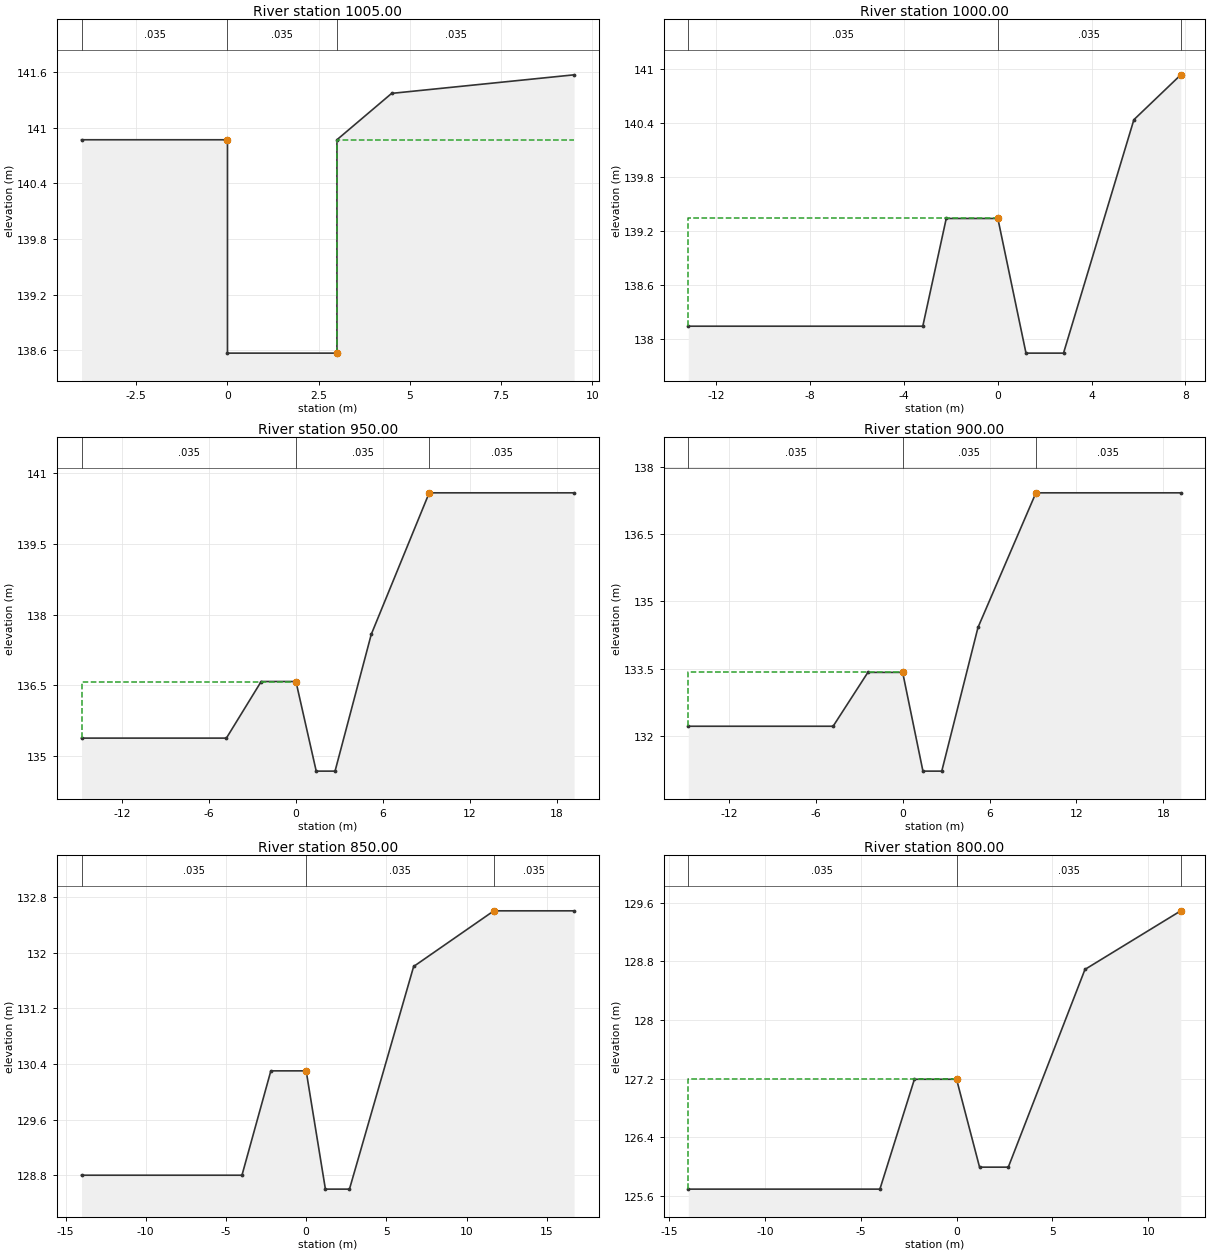
Type RM Length L Ch R = 1 ,1005.00 ,5,5,5
BEGIN DESCRIPTION:
20.005
END DESCRIPTION:
#Sta/Elev= 7
      -4  140.87       0  140.87       0  138.57       3  138.57       3  140.87
     4.5  141.37     9.5  141.57
#Mann= 3 , 0 , 0
      -4    .035       0       0    .035       0       3    .035       0
#XS Ineff= 2 , 0
               0  140.87       3          140.87
Permanent Ineff=
       F       F
Bank Sta=0,3
XS Rating Curve= 0
Exp/Cntr=.3,.1

Type RM Length L Ch R = 1 ,1000.00 ,50,50,50
BEGIN DESCRIPTION:
20
END DESCRIPTION:
#Sta/Elev= 8
   -13.2  138.14    -3.2  138.14    -2.2  139.34       0  139.34     1.2  137.84
     2.8  137.84     5.8  140.44     7.8  140.94
#Mann= 3 , 0 , 0
   -13.2    .035       0       0    .035       0     7.8    .035       0
#XS Ineff= 2 , 0
               0  139.34     7.8          140.94
Permanent Ineff=
       F       F
Bank Sta=0,7.8
XS Rating Curve= 0
Exp/Cntr=.3,.1

Type RM Length L Ch R = 1 ,950.00  ,50,50,50
BEGIN DESCRIPTION:
19
END DESCRIPTION:
#Sta/Elev= 9
   -14.8  135.38    -4.8  135.38    -2.4  136.58       0  136.58     1.4  134.68
     2.7  134.68     5.2  137.58     9.2  140.58    19.2  140.58
#Mann= 3 , 0 , 0
   -14.8    .035       0       0    .035       0     9.2    .035       0
#XS Ineff= 2 , 0
               0  136.58     9.2          140.58
Permanent Ineff=
       F       F
Bank Sta=0,9.2
XS Rating Curve= 0
Exp/Cntr=.3,.1

Type RM Length L Ch R = 1 ,900.00  ,50,50,50
BEGIN DESCRIPTION:
18
END DESCRIPTION:
#Sta/Elev= 9
   -14.8  132.22    -4.8  132.22    -2.4  133.42       0  133.42     1.4  131.22
     2.7  131.22     5.2  134.42     9.2  137.42    19.2  137.42
#Mann= 3 , 0 , 0
   -14.8    .035       0       0    .035       0     9.2    .035       0
#XS Ineff= 2 , 0
               0  133.42     9.2          137.42
Permanent Ineff=
       F       F
Bank Sta=0,9.2
XS Rating Curve= 0
Exp/Cntr=.3,.1

Type RM Length L Ch R = 1 ,850.00  ,50,50,50
BEGIN DESCRIPTION:
17
END DESCRIPTION:
#Sta/Elev= 9
     -14   128.8      -4   128.8    -2.2   130.3       0   130.3     1.2   128.6
     2.7   128.6     6.7   131.8    11.7   132.6    16.7   132.6
#Mann= 3 , 0 , 0
     -14    .035       0       0    .035       0    11.7    .035       0
#XS Ineff= 2 , 0
       0       0   130.3    11.7       0   132.6
Permanent Ineff=
       F       F
Bank Sta=0,11.7
XS Rating Curve= 0
Exp/Cntr=.3,.1

Type RM Length L Ch R = 1 ,800.00  ,50,50,50
BEGIN DESCRIPTION:
16
END DESCRIPTION:
#Sta/Elev= 8
     -14  125.69      -4  125.69    -2.2  127.19       0  127.19     1.2  125.99
     2.7  125.99     6.7  128.69    11.7  129.49
#Mann= 3 , 0 , 0
     -14    .035       0       0    .035       0    11.7    .035       0
#XS Ineff= 2 , 0
               0  127.19    11.7          129.49
Permanent Ineff=
       F       F
Bank Sta=0,11.7
XS Rating Curve= 0
Exp/Cntr=.3,.1

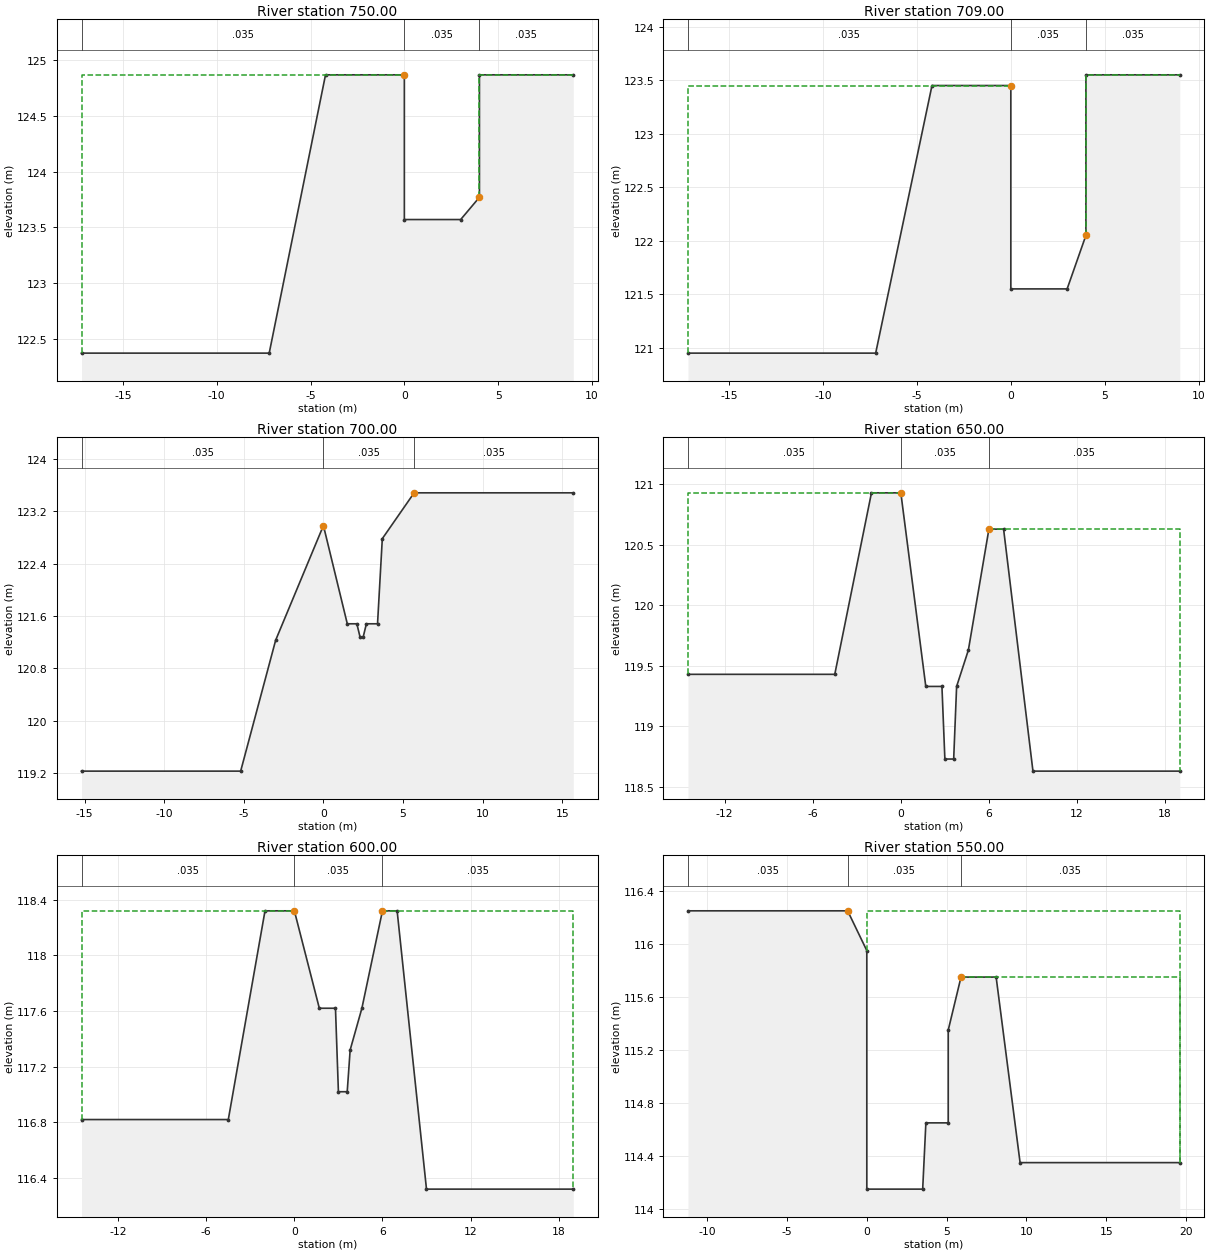
Type RM Length L Ch R = 1 ,750.00  ,41,41,41
BEGIN DESCRIPTION:
15
END DESCRIPTION:
#Sta/Elev= 9
   -17.2  122.37    -7.2  122.37    -4.2  124.87       0  124.87       0  123.57
       3  123.57       4  123.77       4  124.87       9  124.87
#Mann= 3 , 0 , 0
   -17.2    .035       0       0    .035       0       4    .035       0
#XS Ineff= 2 , 0
               0  124.87       4          124.87
Permanent Ineff=
       F       F
Bank Sta=0,4
XS Rating Curve= 0
Exp/Cntr=.3,.1

Type RM Length L Ch R = 1 ,709.00  ,9,9,9
BEGIN DESCRIPTION:
14.009
END DESCRIPTION:
#Sta/Elev= 9
   -17.2  120.95    -7.2  120.95    -4.2  123.45       0  123.45       0  121.55
       3  121.55       4  122.05       4  123.55       9  123.55
#Mann= 3 , 0 , 0
   -17.2    .035       0       0    .035       0       4    .035       0
#XS Ineff= 2 , 0
               0  123.45       4          123.55
Permanent Ineff=
       F       F
Bank Sta=0,4
XS Rating Curve= 0
Exp/Cntr=.3,.1

Type RM Length L Ch R = 1 ,700.00  ,50,50,50
BEGIN DESCRIPTION:
14
END DESCRIPTION:
#Sta/Elev= 13
   -15.2  119.23    -5.2  119.23      -3  121.23       0  122.98     1.5  121.48
     2.1  121.48     2.3  121.28     2.5  121.28     2.7  121.48     3.4  121.48
     3.7  122.78     5.7  123.48    15.7  123.48
#Mann= 3 , 0 , 0
   -15.2    .035       0       0    .035       0     5.7    .035       0
#XS Ineff= 2 , 0
       0       0  122.98     5.7       0  123.48
Permanent Ineff=
       F       F
Bank Sta=0,5.7
XS Rating Curve= 0
Exp/Cntr=.3,.1

Type RM Length L Ch R = 1 ,650.00  ,50,50,50
BEGIN DESCRIPTION:
13
END DESCRIPTION:
#Sta/Elev= 14
   -14.5  119.43    -4.5  119.43      -2  120.93       0  120.93     1.7  119.33
     2.8  119.33       3  118.73     3.6  118.73     3.8  119.33     4.6  119.63
       6  120.63       7  120.63       9  118.63      19  118.63
#Mann= 3 , 0 , 0
   -14.5    .035       0       0    .035       0       6    .035       0
#XS Ineff= 2 , 0
               0  120.93       6          120.63
Permanent Ineff=
       F       F
Bank Sta=0,6
XS Rating Curve= 0
Exp/Cntr=.3,.1

Type RM Length L Ch R = 1 ,600.00  ,50,50,50
BEGIN DESCRIPTION:
12
END DESCRIPTION:
#Sta/Elev= 14
   -14.5  116.82    -4.5  116.82      -2  118.32       0  118.32     1.7  117.62
     2.8  117.62       3  117.02     3.6  117.02     3.8  117.32     4.6  117.62
       6  118.32       7  118.32       9  116.32      19  116.32
#Mann= 3 , 0 , 0
   -14.5    .035       0       0    .035       0       6    .035       0
#XS Ineff= 2 , 0
               0  118.32       6          118.32
Permanent Ineff=
       F       F
Bank Sta=0,6
XS Rating Curve= 0
Exp/Cntr=.3,.1

Type RM Length L Ch R = 1 ,550.00  ,50,50,50
BEGIN DESCRIPTION:
11
END DESCRIPTION:
#Sta/Elev= 12
   -11.2  116.25    -1.2  116.25       0  115.95       0  114.15     3.5  114.15
     3.7  114.65     5.1  114.65     5.1  115.35     5.9  115.75     8.1  115.75
     9.6  114.35    19.6  114.35
#Mann= 3 , 0 , 0
   -11.2    .035       0    -1.2    .035       0     5.9    .035       0
#XS Ineff= 2 , 0
       0    -1.2  116.25     5.9       0  115.75
Permanent Ineff=
       F       F
Bank Sta=-1.2,5.9
XS Rating Curve= 0
Exp/Cntr=.3,.1

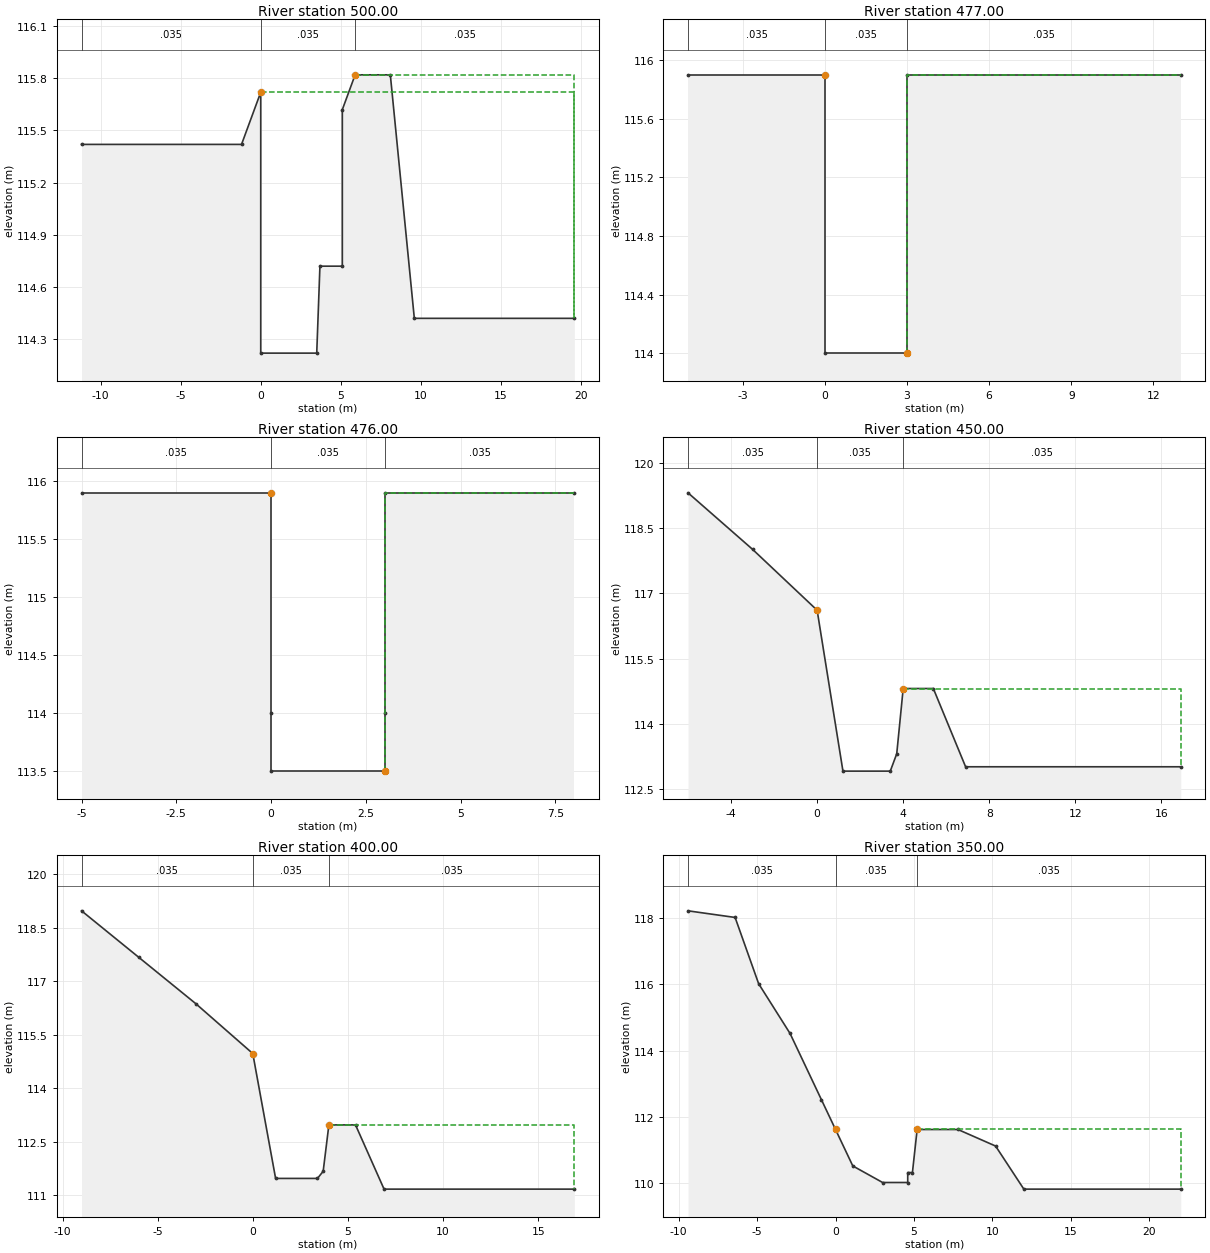
Type RM Length L Ch R = 1 ,500.00  ,23,23,23
BEGIN DESCRIPTION:
10
END DESCRIPTION:
#Sta/Elev= 12
   -11.2  115.42    -1.2  115.42       0  115.72       0  114.22     3.5  114.22
     3.7  114.72     5.1  114.72     5.1  115.62     5.9  115.82     8.1  115.82
     9.6  114.42    19.6  114.42
#Mann= 3 , 0 , 0
   -11.2    .035       0       0    .035       0     5.9    .035       0
#XS Ineff= 2 , 0
       0       0  115.72     5.9       0  115.82
Permanent Ineff=
       F       F
Bank Sta=0,5.9
XS Rating Curve= 0
Exp/Cntr=.3,.1

Type RM Length L Ch R = 1 ,477.00  ,1,1,1
BEGIN DESCRIPTION:
9.027
END DESCRIPTION:
#Sta/Elev= 6
      -5   115.9       0   115.9       0     114       3     114       3   115.9
      13   115.9
#Mann= 3 , 0 , 0
      -5    .035       0       0    .035       0       3    .035       0
#XS Ineff= 2 , 0
               0   115.9       3           115.9
Permanent Ineff=
       F       F
Bank Sta=0,3
XS Rating Curve= 0
Exp/Cntr=.3,.1

Type RM Length L Ch R = 1 ,476.00  ,26,26,26
BEGIN DESCRIPTION:
9.026
END DESCRIPTION:
#Sta/Elev= 8
      -5   115.9       0   115.9       0     114       0   113.5       3   113.5
       3     114       3   115.9       8   115.9
#Mann= 3 , 0 , 0
      -5    .035       0       0    .035       0       3    .035       0
#XS Ineff= 2 , 0
               0   115.9       3           115.9
Permanent Ineff=
       F       F
Bank Sta=0,3
XS Rating Curve= 0
Exp/Cntr=.3,.1

Type RM Length L Ch R = 1 ,450.00  ,50,50,50
BEGIN DESCRIPTION:
9
END DESCRIPTION:
#Sta/Elev= 10
      -6  119.31      -3  118.01       0  116.61     1.2  112.91     3.4  112.91
     3.7  113.31       4  114.81     5.4  114.81     6.9  113.01    16.9  113.01
#Mann= 3 , 0 , 0
      -6    .035       0       0    .035       0       4    .035       0
#XS Ineff= 2 , 0
               0  116.61       4          114.81
Permanent Ineff=
       F       F
Bank Sta=0,4
XS Rating Curve= 0
Exp/Cntr=.3,.1

Type RM Length L Ch R = 1 ,400.00  ,50,50,50
BEGIN DESCRIPTION:
8
END DESCRIPTION:
#Sta/Elev= 11
      -9  118.97      -6  117.67      -3  116.37       0  114.97     1.2  111.47
     3.4  111.47     3.7  111.67       4  112.97     5.4  112.97     6.9  111.17
    16.9  111.17
#Mann= 3 , 0 , 0
      -9    .035       0       0    .035       0       4    .035       0
#XS Ineff= 2 , 0
               0  114.97       4          112.97
Permanent Ineff=
       F       F
Bank Sta=0,4
XS Rating Curve= 0
Exp/Cntr=.3,.1

Type RM Length L Ch R = 1 ,350.00  ,50,50,50
BEGIN DESCRIPTION:
7
END DESCRIPTION:
#Sta/Elev= 16
    -9.4  118.22    -6.4  118.02    -4.9  116.02    -2.9  114.52     -.9  112.52
       0  111.62     1.1  110.52       3  110.02     4.6  110.02     4.6  110.32
     4.9  110.32     5.2  111.62     7.8  111.62    10.2  111.12      12  109.82
      22  109.82
#Mann= 3 , 0 , 0
    -9.4    .035       0       0    .035       0     5.2    .035       0
#XS Ineff= 2 , 0
               0  111.62     5.2          111.62
Permanent Ineff=
       F       F
Bank Sta=0,5.2
XS Rating Curve= 0
Exp/Cntr=.3,.1

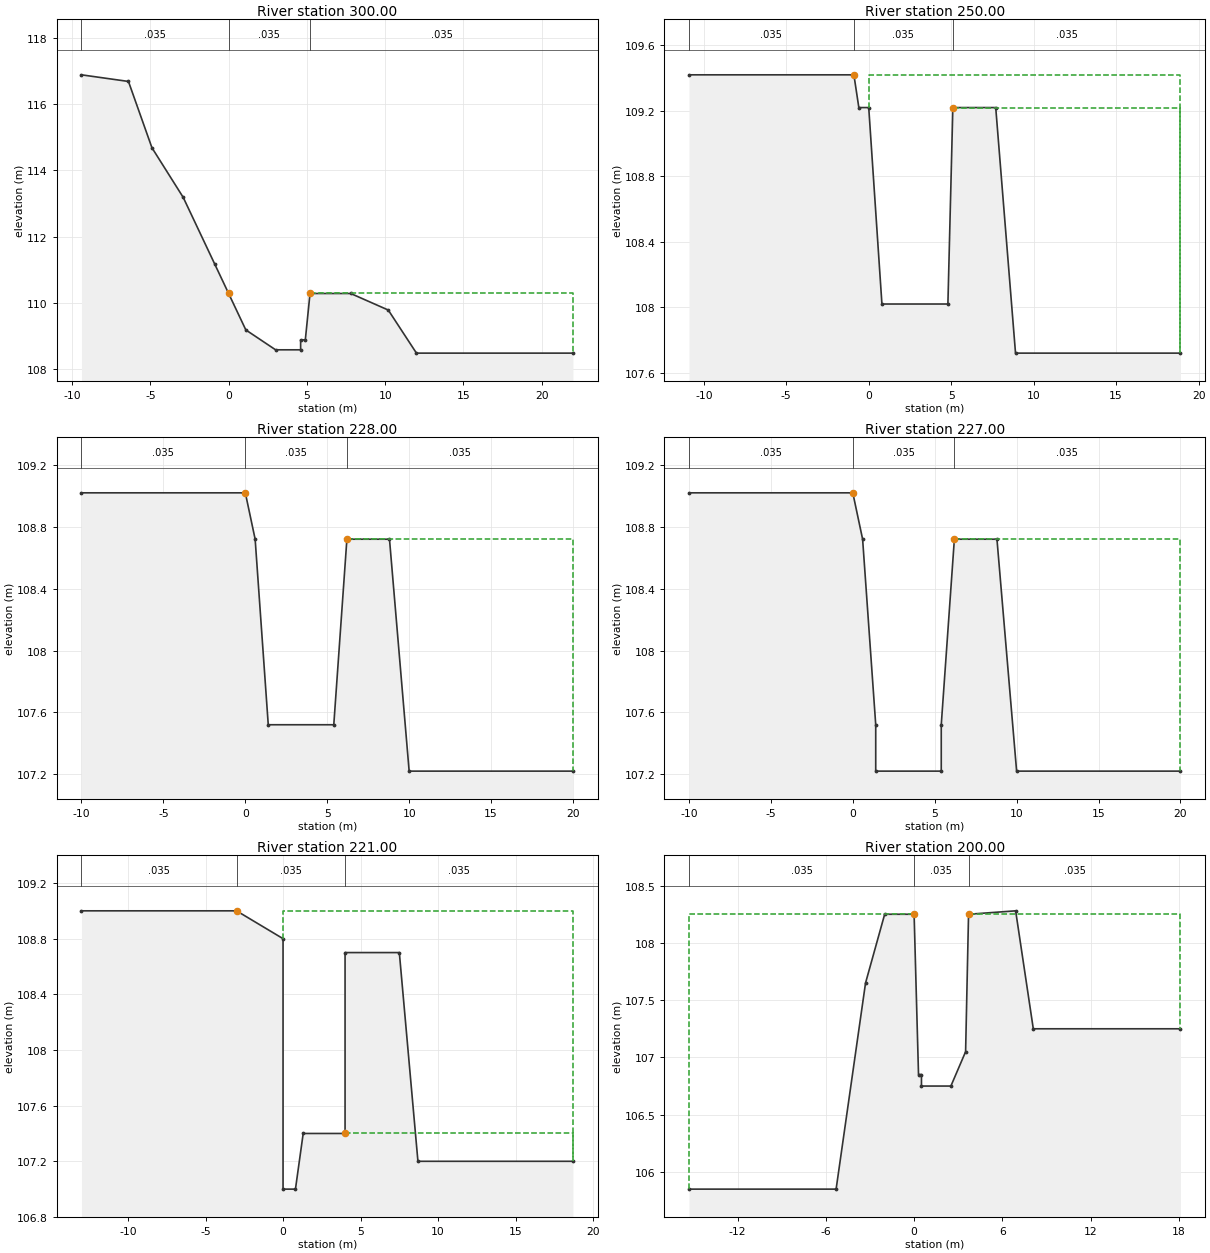
Type RM Length L Ch R = 1 ,300.00  ,50,50,50
BEGIN DESCRIPTION:
6
END DESCRIPTION:
#Sta/Elev= 16
    -9.4  116.88    -6.4  116.68    -4.9  114.68    -2.9  113.18     -.9  111.18
       0  110.28     1.1  109.18       3  108.58     4.6  108.58     4.6  108.88
     4.9  108.88     5.2  110.28     7.8  110.28    10.2  109.78      12  108.48
      22  108.48
#Mann= 3 , 0 , 0
    -9.4    .035       0       0    .035       0     5.2    .035       0
#XS Ineff= 2 , 0
               0  110.28     5.2          110.28
Permanent Ineff=
       F       F
Bank Sta=0,5.2
XS Rating Curve= 0
Exp/Cntr=.3,.1

Type RM Length L Ch R = 1 ,250.00  ,22,22,22
BEGIN DESCRIPTION:
5
END DESCRIPTION:
#Sta/Elev= 10
   -10.9  109.42     -.9  109.42     -.6  109.22       0  109.22      .8  108.02
     4.8  108.02     5.1  109.22     7.7  109.22     8.9  107.72    18.9  107.72
#Mann= 3 , 0 , 0
   -10.9    .035       0     -.9    .035       0     5.1    .035       0
#XS Ineff= 2 , 0
       0     -.9  109.42     5.1       0  109.22
Permanent Ineff=
       F       F
Bank Sta=-.9,5.1
XS Rating Curve= 0
Exp/Cntr=.3,.1

Type RM Length L Ch R = 1 ,228.00  ,1,1,1
BEGIN DESCRIPTION:
4.028
END DESCRIPTION:
#Sta/Elev= 9
     -10  109.02       0  109.02      .6  108.72     1.4  107.52     5.4  107.52
     6.2  108.72     8.8  108.72      10  107.22      20  107.22
#Mann= 3 , 0 , 0
     -10    .035       0       0    .035       0     6.2    .035       0
#XS Ineff= 2 , 0
               0  109.02     6.2          108.72
Permanent Ineff=
       F       F
Bank Sta=0,6.2
XS Rating Curve= 0
Exp/Cntr=.3,.1

Type RM Length L Ch R = 1 ,227.00  ,6,6,6
BEGIN DESCRIPTION:
4.027
END DESCRIPTION:
#Sta/Elev= 11
     -10  109.02       0  109.02      .6  108.72     1.4  107.52     1.4  107.22
     5.4  107.22     5.4  107.52     6.2  108.72     8.8  108.72      10  107.22
      20  107.22
#Mann= 3 , 0 , 0
     -10    .035       0       0    .035       0     6.2    .035       0
#XS Ineff= 2 , 0
               0  109.02     6.2          108.72
Permanent Ineff=
       F       F
Bank Sta=0,6.2
XS Rating Curve= 0
Exp/Cntr=.3,.1

Type RM Length L Ch R = 1 ,221.00  ,21,21,21
BEGIN DESCRIPTION:
4.021
END DESCRIPTION:
#Sta/Elev= 11
     -13     109      -3     109       0   108.8       0     107      .8     107
     1.3   107.4       4   107.4       4   108.7     7.5   108.7     8.7   107.2
    18.7   107.2
#Mann= 3 , 0 , 0
     -13    .035       0      -3    .035       0       4    .035       0
#XS Ineff= 2 , 0
       0      -3     109       4       0   107.4
Permanent Ineff=
       F       F
Bank Sta=-3,4
XS Rating Curve= 0
Exp/Cntr=.3,.1

Type RM Length L Ch R = 1 ,200.00  ,34,34,34
BEGIN DESCRIPTION:
4
END DESCRIPTION:
#Sta/Elev= 14
   -15.3  105.85    -5.3  105.85    -3.3  107.65      -2  108.25       0  108.25
      .3  106.85      .5  106.85      .5  106.75     2.5  106.75     3.5  107.05
     3.7  108.25     6.9  108.28     8.1  107.25    18.1  107.25
#Mann= 3 , 0 , 0
   -15.3    .035       0       0    .035       0     3.7    .035       0
#XS Ineff= 2 , 0
               0  108.25     3.7          108.25
Permanent Ineff=
       F       F
Bank Sta=0,3.7
XS Rating Curve= 0
Exp/Cntr=.3,.1

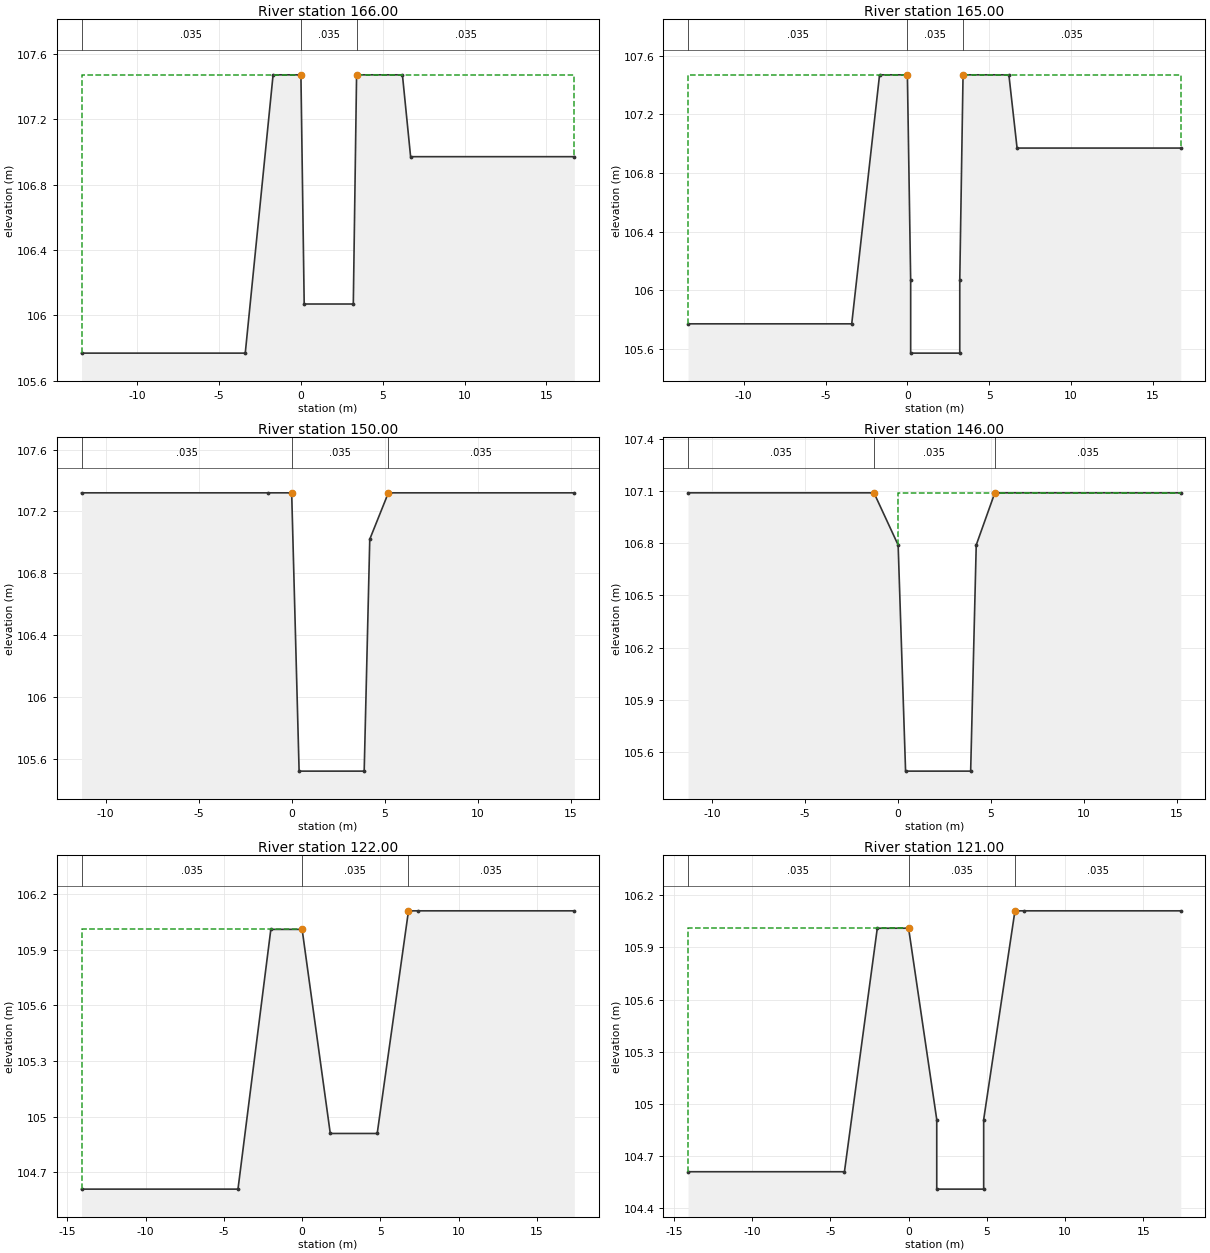
Type RM Length L Ch R = 1 ,166.00  ,1,1,1
BEGIN DESCRIPTION:
3.016
END DESCRIPTION:
#Sta/Elev= 10
   -13.4  105.77    -3.4  105.77    -1.7  107.47       0  107.47      .2  106.07
     3.2  106.07     3.4  107.47     6.2  107.47     6.7  106.97    16.7  106.97
#Mann= 3 , 0 , 0
   -13.4    .035       0       0    .035       0     3.4    .035       0
#XS Ineff= 2 , 0
               0  107.47     3.4          107.47
Permanent Ineff=
       F       F
Bank Sta=0,3.4
XS Rating Curve= 0
Exp/Cntr=.3,.1

Type RM Length L Ch R = 1 ,165.00  ,15,15,15
BEGIN DESCRIPTION:
3.015
END DESCRIPTION:
#Sta/Elev= 12
   -13.4  105.77    -3.4  105.77    -1.7  107.47       0  107.47      .2  106.07
      .2  105.57     3.2  105.57     3.2  106.07     3.4  107.47     6.2  107.47
     6.7  106.97    16.7  106.97
#Mann= 3 , 0 , 0
   -13.4    .035       0       0    .035       0     3.4    .035       0
#XS Ineff= 2 , 0
               0  107.47     3.4          107.47
Permanent Ineff=
       F       F
Bank Sta=0,3.4
XS Rating Curve= 0
Exp/Cntr=.3,.1

Type RM Length L Ch R = 1 ,150.00  ,4,4,4
BEGIN DESCRIPTION:
3
END DESCRIPTION:
#Sta/Elev= 8
   -11.3  107.32    -1.3  107.32       0  107.32      .4  105.52     3.9  105.52
     4.2  107.02     5.2  107.32    15.2  107.32
#Mann= 3 , 0 , 0
   -11.3    .035       0       0    .035       0     5.2    .035       0
#XS Ineff= 2 , 0
               0  107.32     5.2          107.32
Permanent Ineff=
       F       F
Bank Sta=0,5.2
XS Rating Curve= 0
Exp/Cntr=.3,.1

Type RM Length L Ch R = 1 ,146.00  ,24,24,24
BEGIN DESCRIPTION:
2.046
END DESCRIPTION:
#Sta/Elev= 8
   -11.3  107.09    -1.3  107.09       0  106.79      .4  105.49     3.9  105.49
     4.2  106.79     5.2  107.09    15.2  107.09
#Mann= 3 , 0 , 0
   -11.3    .035       0    -1.3    .035       0     5.2    .035       0
#XS Ineff= 2 , 0
       0    -1.3  107.09     5.2       0  107.09
Permanent Ineff=
       F       F
Bank Sta=-1.3,5.2
XS Rating Curve= 0
Exp/Cntr=.3,.1

Type RM Length L Ch R = 1 ,122.00  ,1,1,1
BEGIN DESCRIPTION:
2.022
END DESCRIPTION:
#Sta/Elev= 9
   -14.1  104.61    -4.1  104.61      -2  106.01       0  106.01     1.8  104.91
     4.8  104.91     6.8  106.11     7.4  106.11    17.4  106.11
#Mann= 3 , 0 , 0
   -14.1    .035       0       0    .035       0     6.8    .035       0
#XS Ineff= 2 , 0
               0  106.01     6.8          106.11
Permanent Ineff=
       F       F
Bank Sta=0,6.8
XS Rating Curve= 0
Exp/Cntr=.3,.1

Type RM Length L Ch R = 1 ,121.00  ,2,2,2
BEGIN DESCRIPTION:
2.021
END DESCRIPTION:
#Sta/Elev= 11
   -14.1  104.61    -4.1  104.61      -2  106.01       0  106.01     1.8  104.91
     1.8  104.51     4.8  104.51     4.8  104.91     6.8  106.11     7.4  106.11
    17.4  106.11
#Mann= 3 , 0 , 0
   -14.1    .035       0       0    .035       0     6.8    .035       0
#XS Ineff= 2 , 0
               0  106.01     6.8          106.11
Permanent Ineff=
       F       F
Bank Sta=0,6.8
XS Rating Curve= 0
Exp/Cntr=.3,.1

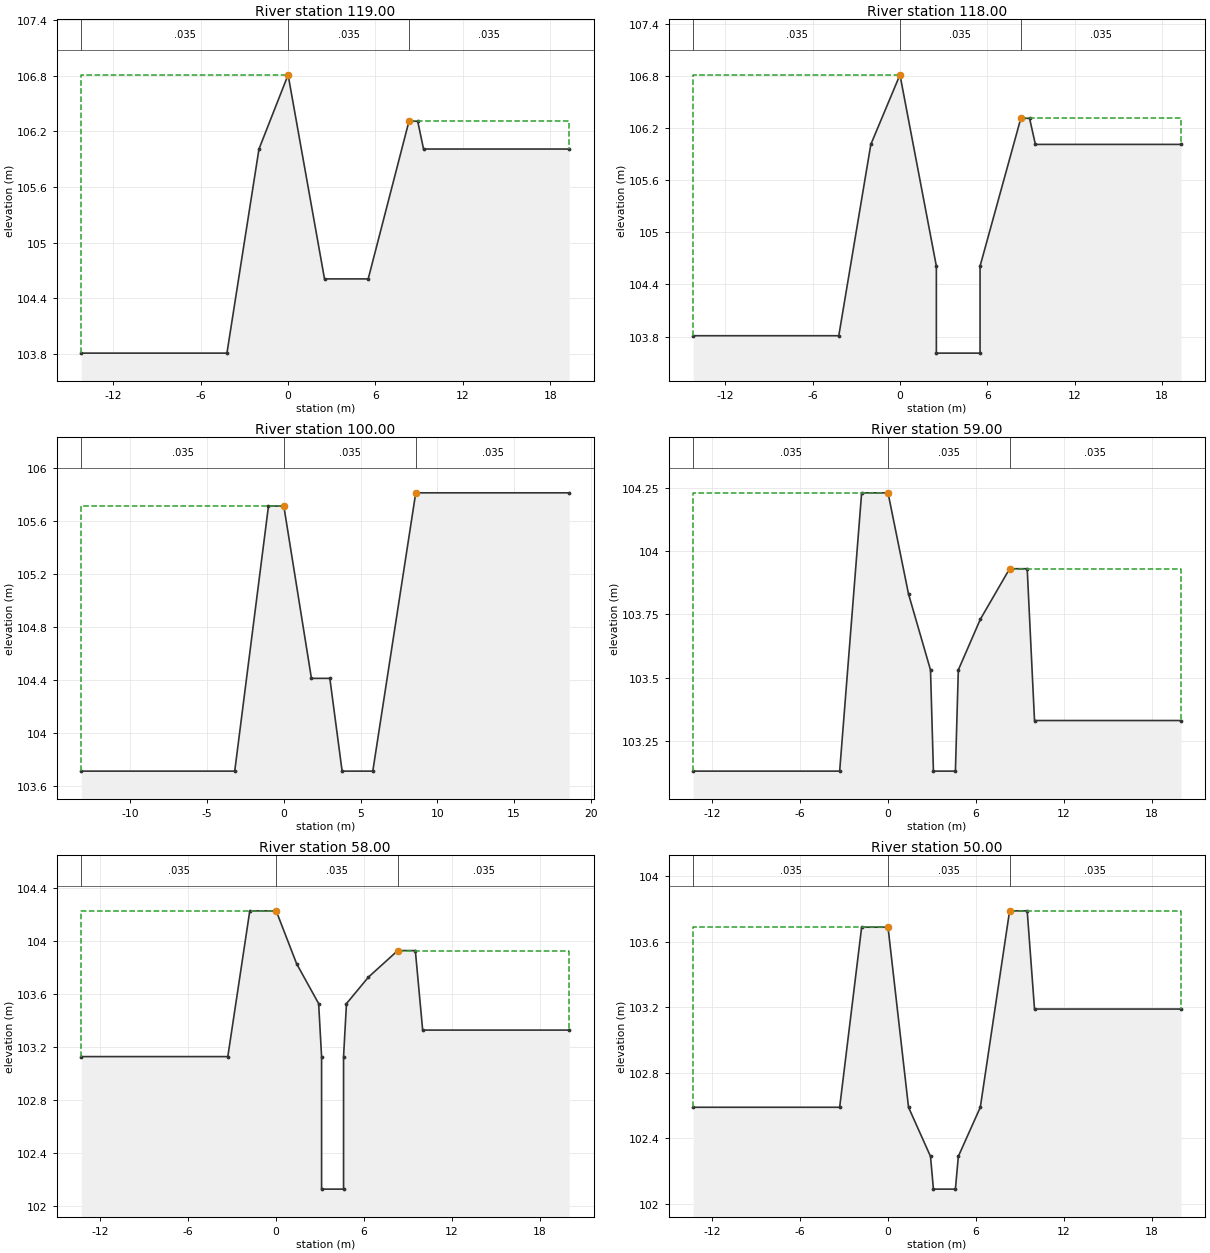
Type RM Length L Ch R = 1 ,119.00  ,1,1,1
BEGIN DESCRIPTION:
2.019
END DESCRIPTION:
#Sta/Elev= 10
   -14.2  103.81    -4.2  103.81      -2  106.01       0  106.81     2.5  104.61
     5.5  104.61     8.3  106.31     8.9  106.31     9.3  106.01    19.3  106.01
#Mann= 3 , 0 , 0
   -14.2    .035       0       0    .035       0     8.3    .035       0
#XS Ineff= 2 , 0
               0  106.81     8.3          106.31
Permanent Ineff=
       F       F
Bank Sta=0,8.3
XS Rating Curve= 0
Exp/Cntr=.3,.1

Type RM Length L Ch R = 1 ,118.00  ,18,18,18
BEGIN DESCRIPTION:
2.018
END DESCRIPTION:
#Sta/Elev= 12
   -14.2  103.81    -4.2  103.81      -2  106.01       0  106.81     2.5  104.61
     2.5  103.61     5.5  103.61     5.5  104.61     8.3  106.31     8.9  106.31
     9.3  106.01    19.3  106.01
#Mann= 3 , 0 , 0
   -14.2    .035       0       0    .035       0     8.3    .035       0
#XS Ineff= 2 , 0
               0  106.81     8.3          106.31
Permanent Ineff=
       F       F
Bank Sta=0,8.3
XS Rating Curve= 0
Exp/Cntr=.3,.1

Type RM Length L Ch R = 1 ,100.00  ,41,41,41
BEGIN DESCRIPTION:
2
END DESCRIPTION:
#Sta/Elev= 10
   -13.2  103.71    -3.2  103.71      -1  105.71       0  105.71     1.8  104.41
       3  104.41     3.8  103.71     5.8  103.71     8.6  105.81    18.6  105.81
#Mann= 3 , 0 , 0
   -13.2    .035       0       0    .035       0     8.6    .035       0
#XS Ineff= 2 , 0
               0  105.71     8.6          105.81
Permanent Ineff=
       F       F
Bank Sta=0,8.6
XS Rating Curve= 0
Exp/Cntr=.3,.1

Type RM Length L Ch R = 1 ,59.00   ,1,1,1
BEGIN DESCRIPTION:
1.009
END DESCRIPTION:
#Sta/Elev= 14
   -13.3  103.13    -3.3  103.13    -1.8  104.23       0  104.23     1.4  103.83
     2.9  103.53     3.1  103.13     4.6  103.13     4.8  103.53     6.3  103.73
     8.3  103.93     9.5  103.93      10  103.33      20  103.33
#Mann= 3 , 0 , 0
   -13.3    .035       0       0    .035       0     8.3    .035       0
#XS Ineff= 2 , 0
               0  104.23     8.3          103.93
Permanent Ineff=
       F       F
Bank Sta=0,8.3
XS Rating Curve= 0
Exp/Cntr=.3,.1

Type RM Length L Ch R = 1 ,58.00   ,8,8,8
BEGIN DESCRIPTION:
1.008
END DESCRIPTION:
#Sta/Elev= 16
   -13.3  103.13    -3.3  103.13    -1.8  104.23       0  104.23     1.4  103.83
     2.9  103.53     3.1  103.13     3.1  102.13     4.6  102.13     4.6  103.13
     4.8  103.53     6.3  103.73     8.3  103.93     9.5  103.93      10  103.33
      20  103.33
#Mann= 3 , 0 , 0
   -13.3    .035       0       0    .035       0     8.3    .035       0
#XS Ineff= 2 , 0
               0  104.23     8.3          103.93
Permanent Ineff=
       F       F
Bank Sta=0,8.3
XS Rating Curve= 0
Exp/Cntr=.3,.1

Type RM Length L Ch R = 1 ,50.00   ,49,49,49
BEGIN DESCRIPTION:
1
END DESCRIPTION:
#Sta/Elev= 14
   -13.3  102.59    -3.3  102.59    -1.8  103.69       0  103.69     1.4  102.59
     2.9  102.29     3.1  102.09     4.6  102.09     4.8  102.29     6.3  102.59
     8.3  103.79     9.5  103.79      10  103.19      20  103.19
#Mann= 3 , 0 , 0
   -13.3    .035       0       0    .035       0     8.3    .035       0
#XS Ineff= 2 , 0
               0  103.69     8.3          103.79
Permanent Ineff=
       F       F
Bank Sta=0,8.3
XS Rating Curve= 0
Exp/Cntr=.3,.1

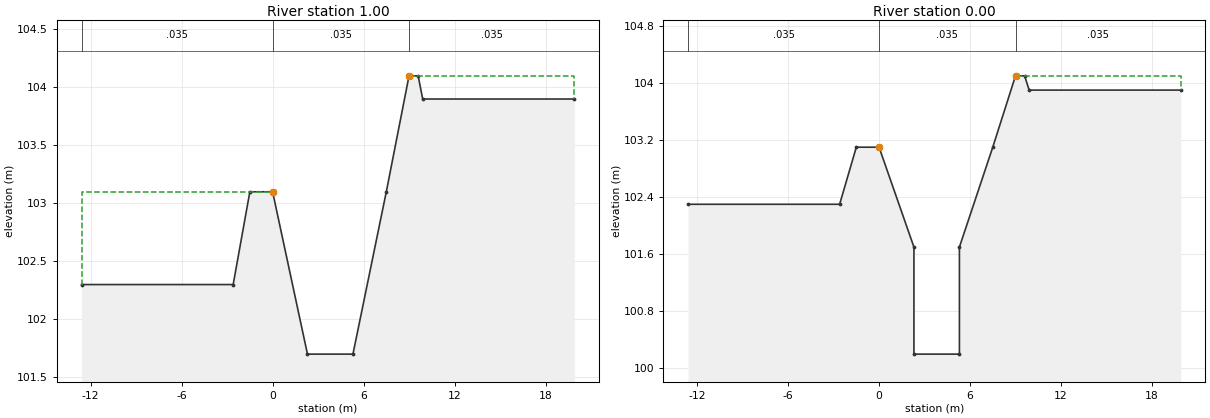
Type RM Length L Ch R = 1 ,1.00    ,1,1,1
BEGIN DESCRIPTION:
0.001
END DESCRIPTION:
#Sta/Elev= 11
   -12.6   102.3    -2.6   102.3    -1.5   103.1       0   103.1     2.3   101.7
     5.3   101.7     7.5   103.1       9   104.1     9.6   104.1     9.9   103.9
    19.9   103.9
#Mann= 3 , 0 , 0
   -12.6    .035       0       0    .035       0       9    .035       0
#XS Ineff= 2 , 0
               0   103.1       9           104.1
Permanent Ineff=
       F       F
Bank Sta=0,9
XS Rating Curve= 0
Exp/Cntr=.3,.1

Type RM Length L Ch R = 1 ,0.00    ,0,0,0
BEGIN DESCRIPTION:
0
END DESCRIPTION:
#Sta/Elev= 13
   -12.6   102.3    -2.6   102.3    -1.5   103.1       0   103.1     2.3   101.7
     2.3   100.2     5.3   100.2     5.3   101.7     7.5   103.1       9   104.1
     9.6   104.1     9.9   103.9    19.9   103.9
#Mann= 3 , 0 , 0
   -12.6    .035       0       0    .035       0       9    .035       0
#XS Ineff= 2 , 0
       0       0   103.1       9       0   104.1
Permanent Ineff=
       F       F
Bank Sta=0,9
XS Rating Curve= 0
Exp/Cntr=.3,.1

Chan Stop Cuts=-1