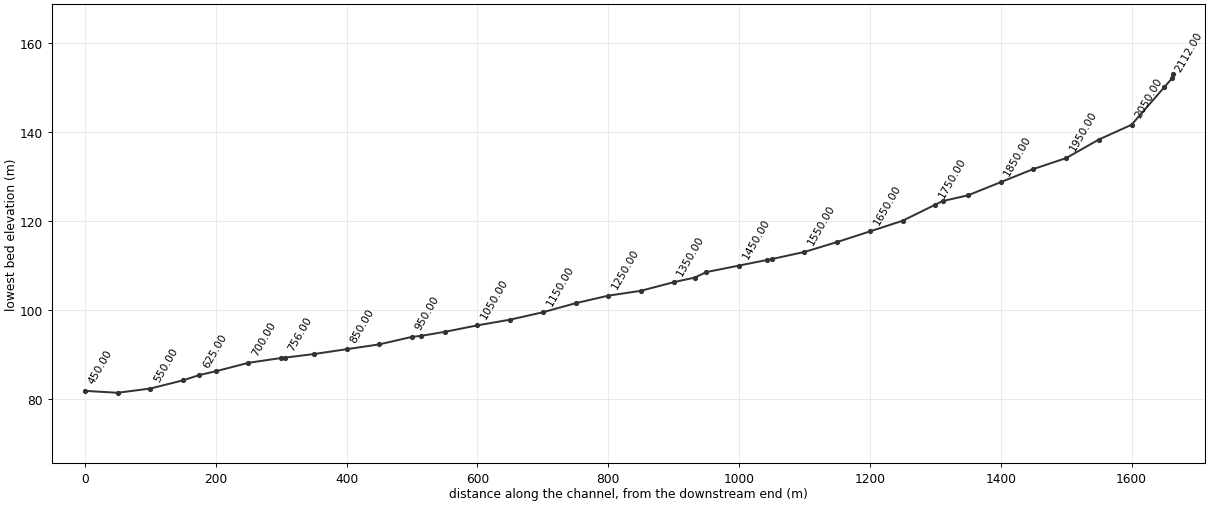
--- DHC.prj (project) ---

Proj Title=buldangdong-ch
Current Plan=p01
Default Exp/Contr=.3,.1
SI Units
Geom File=g01
Flow File=f01
Plan File=p01
Y Axis Title=Elevation
X Axis Title(PF)=Main Channel Distance
X Axis Title(XS)=Station
BEGIN DESCRIPTION:
           BACK WATER COMPUTATION
      APPLICATION OF HEC-2 BY Samju Construction Engineering
      buldangdong-ch: 10,20,30,50,80 yr
END DESCRIPTION:
DSS Export Rating Curves= 0
DSS Export Rating Curve Sorted= 0
DSS Export Volume Flow Curves= 0
DXF OffsetX= 0
DXF OffsetY= 0
DXF ScaleX= 1
DXF ScaleY= 10

--- DHC.p01 (plan) ---

Plan Title=Imported Plan 01
Version=Version 3.0.1  Mar 2001
Short Identifier=Imported Pla
Geom File=g01
Flow File=f01
Subcritical Flow
K Sum by GR= 0
Std Step Tol= 0.003
Critical Tol= 0.003
Num of Std Step Trials= 20
Max Error Tol= 0.1
Flow Tol Ratio= 0.001
Split Flow NTrial= 30
Split Flow Tol= 0.02
Split Flow Ratio= 0.02
Log Output Level= 0
Friction Slope Method= 1
Unsteady Friction Slope Method= 2
Parabolic Critical Depth
Global Vel Dist= 0 , 0 , 0
Global Log Level= 0
CheckData=True
Encroach Param=-1 ,0,0, 0
Computation Interval=1HOUR
Output Interval=1HOUR
Run HTab= 0
Run UNet= 0
Run PostProcess= 0
UNET Theta= 1
UNET ZTol= 0.02
UNET ZSATol= 0.1
UNET MxIter= 20
UNET MaxInSteps= 20
UNET DtIC= 0
UNET DtMin= 0
UNET MaxCRTS= 20
UNET WFStab= 2
UNET SFStab= 1
UNET WFX= 1
UNET SFX= 1
UNET Convert EG Bridges=-1
UNET Use Existing IB Tables=-1
Instantaneous Interval=1HOUR
Write IC File= 0
Write Velocity= 0
Write Detailed= 0

--- DHC.f01 (steady flow) ---

Flow Title=Imported Flow 01
Version=Version 3.0.1  Mar 2001
Number of Profiles= 5
Profile Names=10YR,20YR,30YR,50YR,80YR
River Rch & RM=RIVER-1,Reach-1         ,2113.00
    9.05    9.96    10.5   11.17   11.79
River Rch & RM=RIVER-1,Reach-1         ,2000.00
   20.89   23.02   24.26   25.82   27.26
River Rch & RM=RIVER-1,Reach-1         ,1000.00
   31.09   34.27   36.12   38.46   40.61
Boundary for River Rch & Prof#=RIVER-1,Reach-1         , 1
Up Type= 0
Dn Type= 3
Dn Slope=.032
Boundary for River Rch & Prof#=RIVER-1,Reach-1         , 2
Up Type= 0
Dn Type= 3
Dn Slope=.032
Boundary for River Rch & Prof#=RIVER-1,Reach-1         , 3
Up Type= 0
Dn Type= 3
Dn Slope=.032
Boundary for River Rch & Prof#=RIVER-1,Reach-1         , 4
Up Type= 0
Dn Type= 3
Dn Slope=.032
Boundary for River Rch & Prof#=RIVER-1,Reach-1         , 5
Up Type= 0
Dn Type= 3
Dn Slope=.032
DSS Import GetInterval= 0
DSS Import GetPeak= 0
DSS Import FillOption= 0

--- DHC.g01 (geometry) ---

Geom Title=Imported Geom 01
Version=Version 3.0.1  Mar 2001

River Reach=RIVER-1         ,Reach-1
Reach XY= 2
              .5             .95              .5             .05

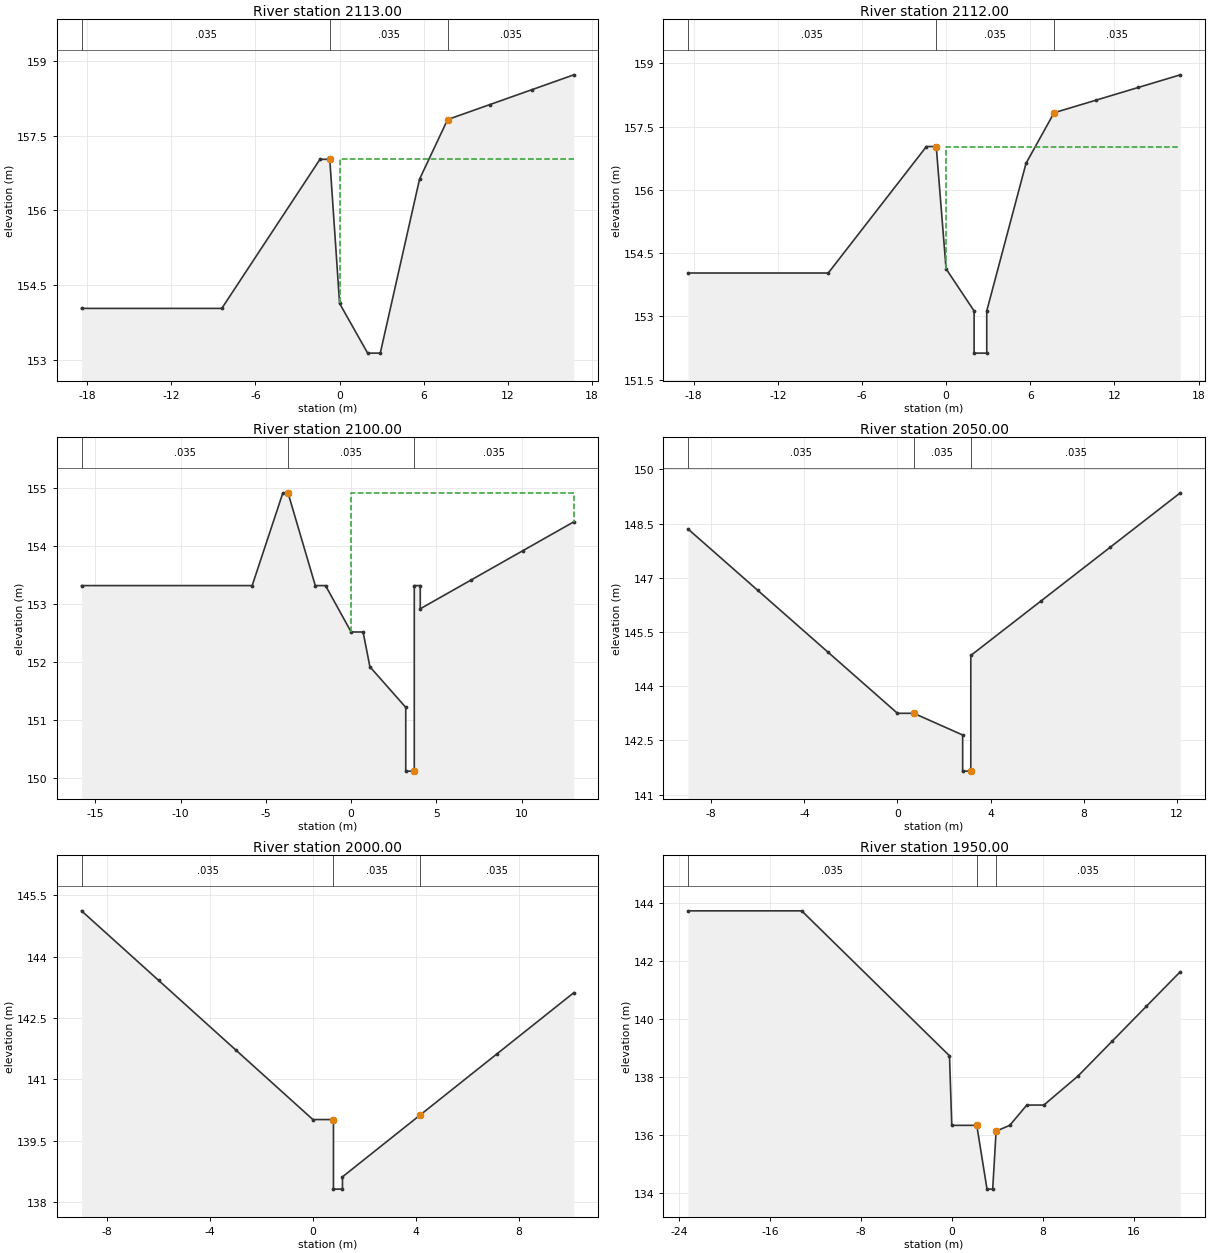
Type RM Length L Ch R = 1 ,2113.00 ,1,1,1
BEGIN DESCRIPTION:
42.013
END DESCRIPTION:
#Sta/Elev= 12
   -18.4  154.03    -8.4  154.03    -1.4  157.03     -.7  157.03       0  154.13
       2  153.13     2.9  153.13     5.7  156.63     7.7  157.83    10.7  158.13
    13.7  158.43    16.7  158.73
#Mann= 3 , 0 , 0
   -18.4    .035       0     -.7    .035       0     7.7    .035       0
#XS Ineff= 2 , 0
       0     -.7  157.03     7.7       0  157.83
Permanent Ineff=
       F       F
Bank Sta=-.7,7.7
XS Rating Curve= 0
Exp/Cntr=.3,.1

Type RM Length L Ch R = 1 ,2112.00 ,12,12,12
BEGIN DESCRIPTION:
42.012
END DESCRIPTION:
#Sta/Elev= 14
   -18.4  154.03    -8.4  154.03    -1.4  157.03     -.7  157.03       0  154.13
       2  153.13       2  152.13     2.9  152.13     2.9  153.13     5.7  156.63
     7.7  157.83    10.7  158.13    13.7  158.43    16.7  158.73
#Mann= 3 , 0 , 0
   -18.4    .035       0     -.7    .035       0     7.7    .035       0
#XS Ineff= 2 , 0
       0     -.7  157.03     7.7       0  157.83
Permanent Ineff=
       F       F
Bank Sta=-.7,7.7
XS Rating Curve= 0
Exp/Cntr=.3,.1

Type RM Length L Ch R = 1 ,2100.00 ,50,50,50
BEGIN DESCRIPTION:
42
END DESCRIPTION:
#Sta/Elev= 18
   -15.8  153.31    -5.8  153.31      -4  154.91    -3.7  154.91    -2.1  153.31
    -1.5  153.31       0  152.51      .7  152.51     1.1  151.91     3.2  151.21
     3.2  150.11     3.7  150.11     3.7  153.31    4.05  153.31    4.05  152.91
    7.05  153.41   10.05  153.91   13.05  154.41
#Mann= 3 , 0 , 0
   -15.8    .035       0    -3.7    .035       0     3.7    .035       0
#XS Ineff= 2 , 0
       0    -3.7  154.91     3.7       0  150.11
Permanent Ineff=
       F       F
Bank Sta=-3.7,3.7
XS Rating Curve= 0
Exp/Cntr=.3,.1

Type RM Length L Ch R = 1 ,2050.00 ,50,50,50
BEGIN DESCRIPTION:
41
END DESCRIPTION:
#Sta/Elev= 12
      -9  148.35      -6  146.65      -3  144.95       0  143.25      .7  143.25
     2.8  142.65     2.8  141.65    3.15  141.65    3.15  144.85    6.15  146.35
    9.15  147.85   12.15  149.35
#Mann= 3 , 0 , 0
      -9    .035       0      .7    .035       0    3.15    .035       0
Bank Sta=.7,3.15
XS Rating Curve= 0
Exp/Cntr=.3,.1

Type RM Length L Ch R = 1 ,2000.00 ,50,50,50
BEGIN DESCRIPTION:
40
END DESCRIPTION:
#Sta/Elev= 11
      -9  145.12      -6  143.42      -3  141.72       0  140.02      .8  140.02
      .8  138.32    1.15  138.32    1.15  138.62    4.15  140.12    7.15  141.62
   10.15  143.12
#Mann= 3 , 0 , 0
      -9    .035       0      .8    .035       0    4.15    .035       0
#XS Ineff= 2 , 0
       0      .8  140.02    4.15       0  140.12
Permanent Ineff=
       F       F
Bank Sta=.8,4.15
XS Rating Curve= 0
Exp/Cntr=.3,.1

Type RM Length L Ch R = 1 ,1950.00 ,50,50,50
BEGIN DESCRIPTION:
39
END DESCRIPTION:
#Sta/Elev= 15
   -23.2  143.74   -13.2  143.74     -.2  138.74       0  136.34     2.2  136.34
     3.1  134.14     3.6  134.14     3.9  136.14     5.1  136.34     6.6  137.04
     8.1  137.04    11.1  138.04    14.1  139.24    17.1  140.44    20.1  141.64
#Mann= 3 , 0 , 0
   -23.2    .035       0     2.2    .035       0     3.9    .035       0
#XS Ineff= 2 , 0
       0     2.2  136.34     3.9       0  136.14
Permanent Ineff=
       F       F
Bank Sta=2.2,3.9
XS Rating Curve= 0
Exp/Cntr=.3,.1

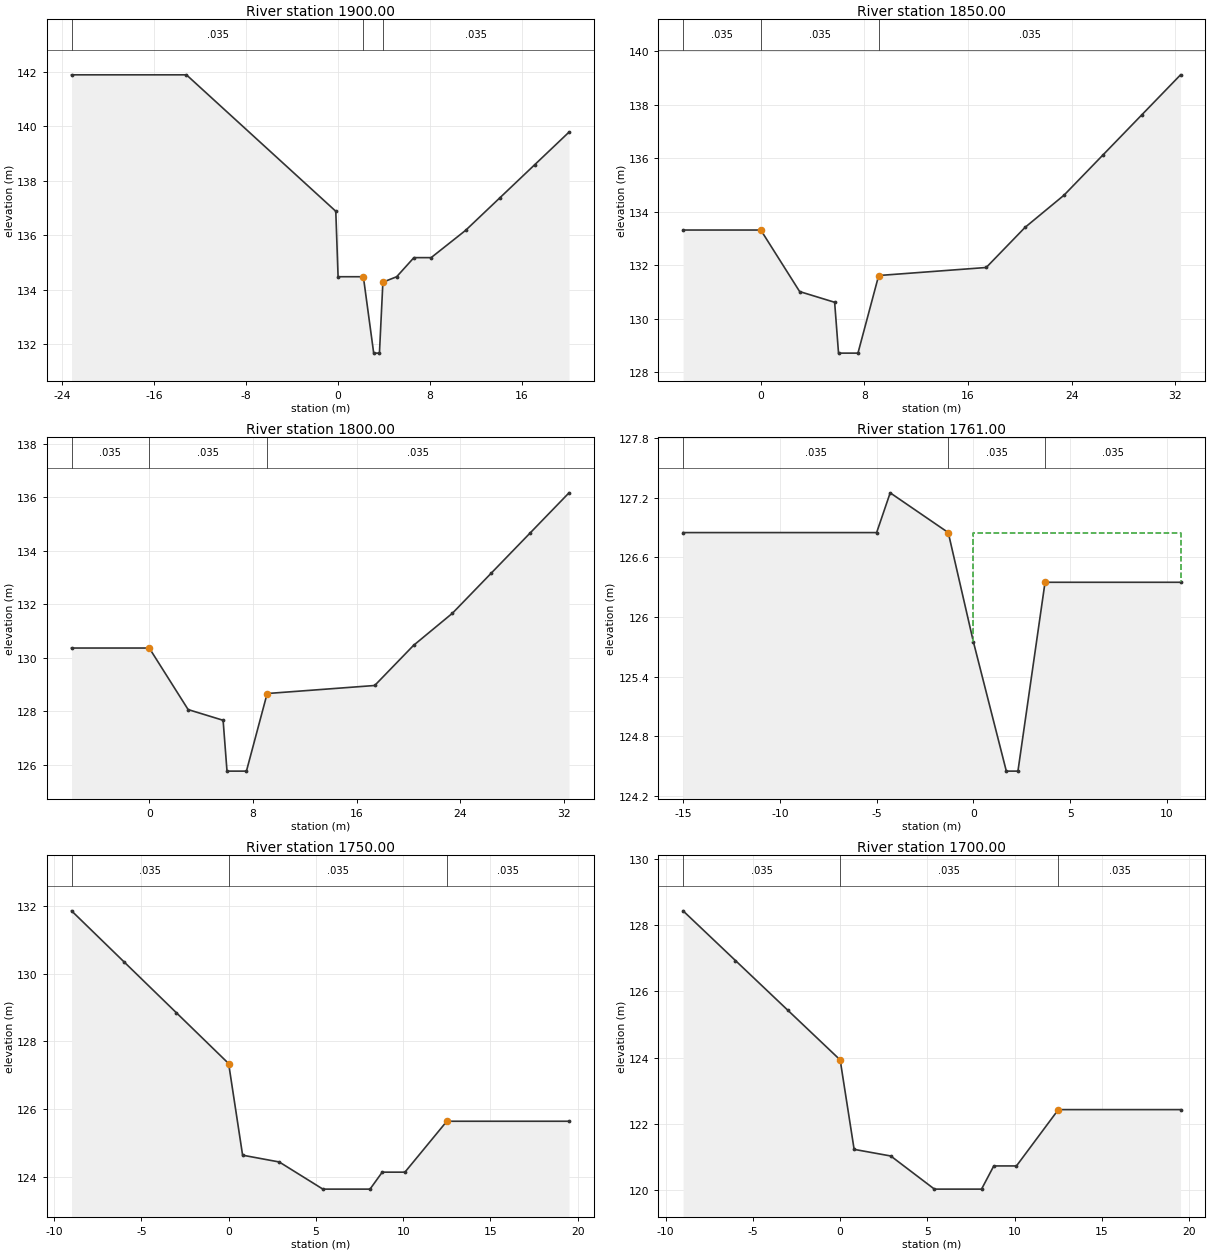
Type RM Length L Ch R = 1 ,1900.00 ,50,50,50
BEGIN DESCRIPTION:
38
END DESCRIPTION:
#Sta/Elev= 15
   -23.2  141.88   -13.2  141.88     -.2  136.88       0  134.48     2.2  134.48
     3.1  131.68     3.6  131.68     3.9  134.28     5.1  134.48     6.6  135.18
     8.1  135.18    11.1  136.18    14.1  137.38    17.1  138.58    20.1  139.78
#Mann= 3 , 0 , 0
   -23.2    .035       0     2.2    .035       0     3.9    .035       0
#XS Ineff= 2 , 0
       0     2.2  134.48     3.9       0  134.28
Permanent Ineff=
       F       F
Bank Sta=2.2,3.9
XS Rating Curve= 0
Exp/Cntr=.3,.1

Type RM Length L Ch R = 1 ,1850.00 ,50,50,50
BEGIN DESCRIPTION:
37
END DESCRIPTION:
#Sta/Elev= 13
      -6  133.32       0  133.32       3  131.02     5.7  130.62       6  128.72
     7.5  128.72     9.1  131.62    17.4  131.92    20.4  133.42    23.4  134.62
    26.4  136.12    29.4  137.62    32.4  139.12
#Mann= 3 , 0 , 0
      -6    .035       0       0    .035       0     9.1    .035       0
#XS Ineff= 2 , 0
       0       0  133.32     9.1       0  131.62
Permanent Ineff=
       F       F
Bank Sta=0,9.1
XS Rating Curve= 0
Exp/Cntr=.3,.1

Type RM Length L Ch R = 1 ,1800.00 ,39,39,39
BEGIN DESCRIPTION:
36
END DESCRIPTION:
#Sta/Elev= 13
      -6  130.36       0  130.36       3  128.06     5.7  127.66       6  125.76
     7.5  125.76     9.1  128.66    17.4  128.96    20.4  130.46    23.4  131.66
    26.4  133.16    29.4  134.66    32.4  136.16
#Mann= 3 , 0 , 0
      -6    .035       0       0    .035       0     9.1    .035       0
#XS Ineff= 2 , 0
       0       0  130.36     9.1       0  128.66
Permanent Ineff=
       F       F
Bank Sta=0,9.1
XS Rating Curve= 0
Exp/Cntr=.3,.1

Type RM Length L Ch R = 1 ,1761.00 ,11,11,11
BEGIN DESCRIPTION:
35.011
END DESCRIPTION:
#Sta/Elev= 9
     -15  126.85      -5  126.85    -4.3  127.25    -1.3  126.85       0  125.75
     1.7  124.45     2.3  124.45     3.7  126.35    10.7  126.35
#Mann= 3 , 0 , 0
     -15    .035       0    -1.3    .035       0     3.7    .035       0
#XS Ineff= 2 , 0
       0    -1.3  126.85     3.7       0  126.35
Permanent Ineff=
       F       F
Bank Sta=-1.3,3.7
XS Rating Curve= 0
Exp/Cntr=.3,.1

Type RM Length L Ch R = 1 ,1750.00 ,50,50,50
BEGIN DESCRIPTION:
35
END DESCRIPTION:
#Sta/Elev= 12
      -9  131.85      -6  130.35      -3  128.85       0  127.35      .8  124.65
     2.9  124.45     5.4  123.65     8.1  123.65     8.8  124.15    10.1  124.15
    12.5  125.65    19.5  125.65
#Mann= 3 , 0 , 0
      -9    .035       0       0    .035       0    12.5    .035       0
#XS Ineff= 2 , 0
               0  127.35    12.5          125.65
Permanent Ineff=
       F       F
Bank Sta=0,12.5
XS Rating Curve= 0
Exp/Cntr=.3,.1

Type RM Length L Ch R = 1 ,1700.00 ,50,50,50
BEGIN DESCRIPTION:
34
END DESCRIPTION:
#Sta/Elev= 12
      -9  128.43      -6  126.93      -3  125.43       0  123.93      .8  121.23
     2.9  121.03     5.4  120.03     8.1  120.03     8.8  120.73    10.1  120.73
    12.5  122.43    19.5  122.43
#Mann= 3 , 0 , 0
      -9    .035       0       0    .035       0    12.5    .035       0
#XS Ineff= 2 , 0
               0  123.93    12.5          122.43
Permanent Ineff=
       F       F
Bank Sta=0,12.5
XS Rating Curve= 0
Exp/Cntr=.3,.1

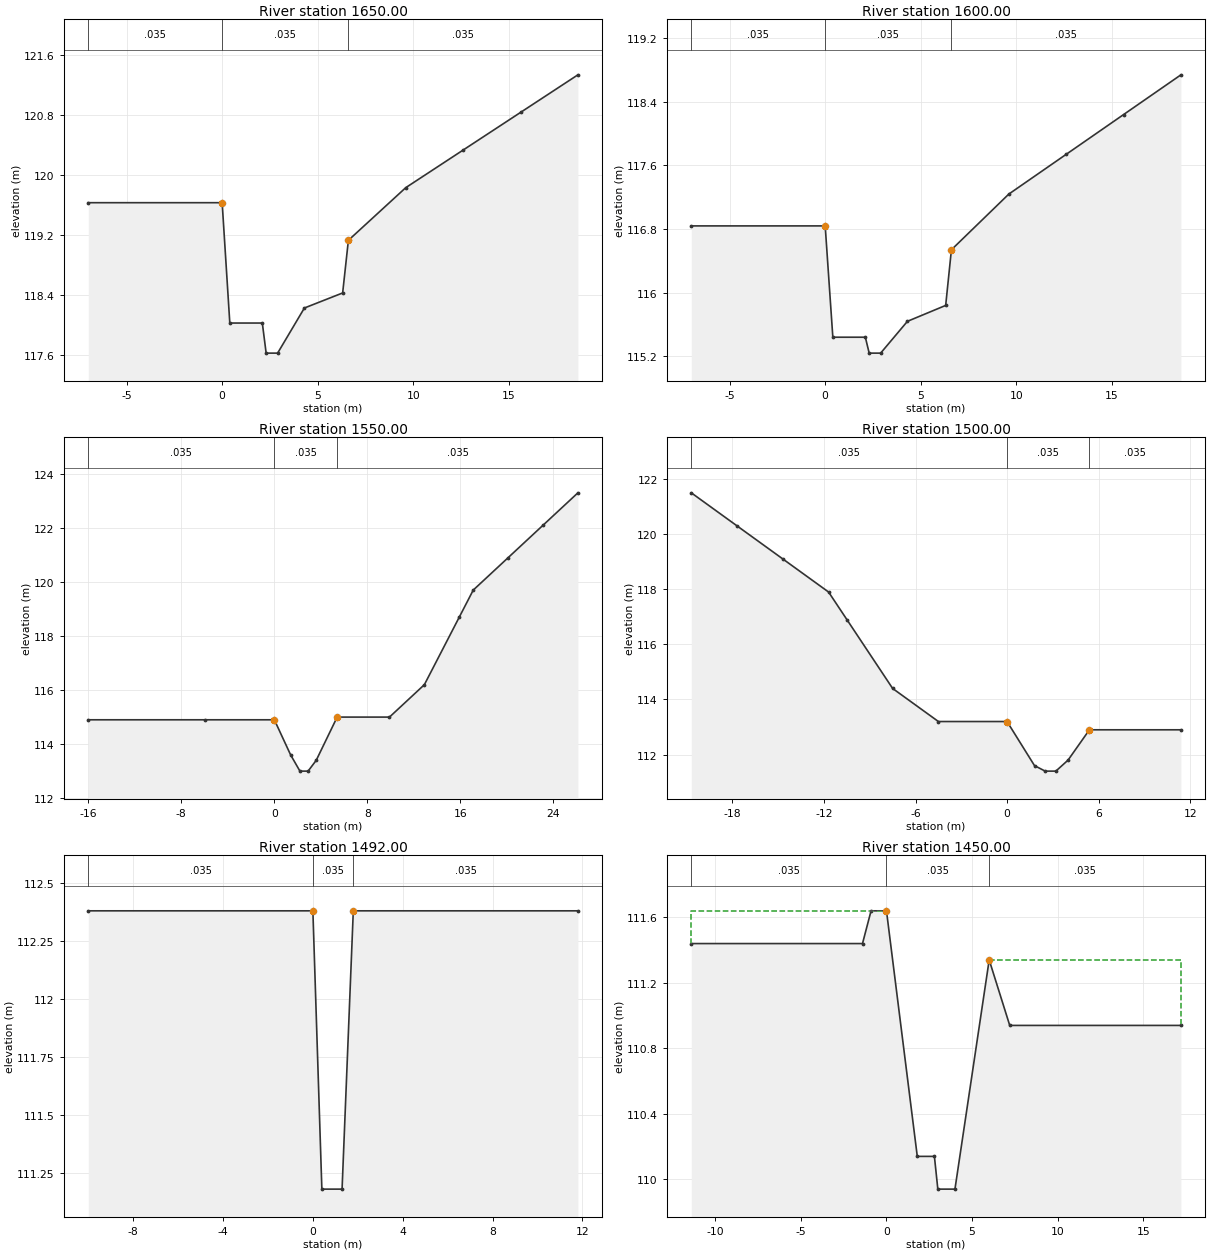
Type RM Length L Ch R = 1 ,1650.00 ,50,50,50
BEGIN DESCRIPTION:
33
END DESCRIPTION:
#Sta/Elev= 13
      -7  119.63       0  119.63      .4  118.03     2.1  118.03     2.3  117.63
     2.9  117.63     4.3  118.23     6.3  118.43     6.6  119.13     9.6  119.83
    12.6  120.33    15.6  120.83    18.6  121.33
#Mann= 3 , 0 , 0
      -7    .035       0       0    .035       0     6.6    .035       0
#XS Ineff= 2 , 0
               0  119.63     6.6          119.13
Permanent Ineff=
       F       F
Bank Sta=0,6.6
XS Rating Curve= 0
Exp/Cntr=.3,.1

Type RM Length L Ch R = 1 ,1600.00 ,50,50,50
BEGIN DESCRIPTION:
32
END DESCRIPTION:
#Sta/Elev= 13
      -7  116.84       0  116.84      .4  115.44     2.1  115.44     2.3  115.24
     2.9  115.24     4.3  115.64     6.3  115.84     6.6  116.54     9.6  117.24
    12.6  117.74    15.6  118.24    18.6  118.74
#Mann= 3 , 0 , 0
      -7    .035       0       0    .035       0     6.6    .035       0
#XS Ineff= 2 , 0
               0  116.84     6.6          116.54
Permanent Ineff=
       F       F
Bank Sta=0,6.6
XS Rating Curve= 0
Exp/Cntr=.3,.1

Type RM Length L Ch R = 1 ,1550.00 ,50,50,50
BEGIN DESCRIPTION:
31
END DESCRIPTION:
#Sta/Elev= 15
     -16  114.91      -6  114.91       0  114.91     1.4  113.61     2.2  113.01
     2.9  113.01     3.6  113.41     5.4  115.01     9.9  115.01    12.9  116.21
    15.9  118.71    17.1  119.71    20.1  120.91    23.1  122.11    26.1  123.31
#Mann= 3 , 0 , 0
     -16    .035       0       0    .035       0     5.4    .035       0
#XS Ineff= 2 , 0
               0  114.91     5.4          115.01
Permanent Ineff=
       F       F
Bank Sta=0,5.4
XS Rating Curve= 0
Exp/Cntr=.3,.1

Type RM Length L Ch R = 1 ,1500.00 ,8,8,8
BEGIN DESCRIPTION:
30
END DESCRIPTION:
#Sta/Elev= 14
   -20.7   121.5   -17.7   120.3   -14.7   119.1   -11.7   117.9   -10.5   116.9
    -7.5   114.4    -4.5   113.2       0   113.2     1.8   111.6     2.5   111.4
     3.2   111.4       4   111.8     5.4   112.9    11.4   112.9
#Mann= 3 , 0 , 0
   -20.7    .035       0       0    .035       0     5.4    .035       0
#XS Ineff= 2 , 0
               0   113.2     5.4           112.9
Permanent Ineff=
       F       F
Bank Sta=0,5.4
XS Rating Curve= 0
Exp/Cntr=.3,.1

Type RM Length L Ch R = 1 ,1492.00 ,42,42,42
BEGIN DESCRIPTION:
29.042
END DESCRIPTION:
#Sta/Elev= 6
     -10  112.38       0  112.38      .4  111.18     1.3  111.18     1.8  112.38
    11.8  112.38
#Mann= 3 , 0 , 0
     -10    .035       0       0    .035       0     1.8    .035       0
#XS Ineff= 2 , 0
               0  112.38     1.8          112.38
Permanent Ineff=
       F       F
Bank Sta=0,1.8
XS Rating Curve= 0
Exp/Cntr=.3,.1

Type RM Length L Ch R = 1 ,1450.00 ,50,50,50
BEGIN DESCRIPTION:
29
END DESCRIPTION:
#Sta/Elev= 11
   -11.4  111.44    -1.4  111.44     -.9  111.64       0  111.64     1.8  110.14
     2.8  110.14       3  109.94       4  109.94       6  111.34     7.2  110.94
    17.2  110.94
#Mann= 3 , 0 , 0
   -11.4    .035       0       0    .035       0       6    .035       0
#XS Ineff= 2 , 0
               0  111.64       6          111.34
Permanent Ineff=
       F       F
Bank Sta=0,6
XS Rating Curve= 0
Exp/Cntr=.3,.1

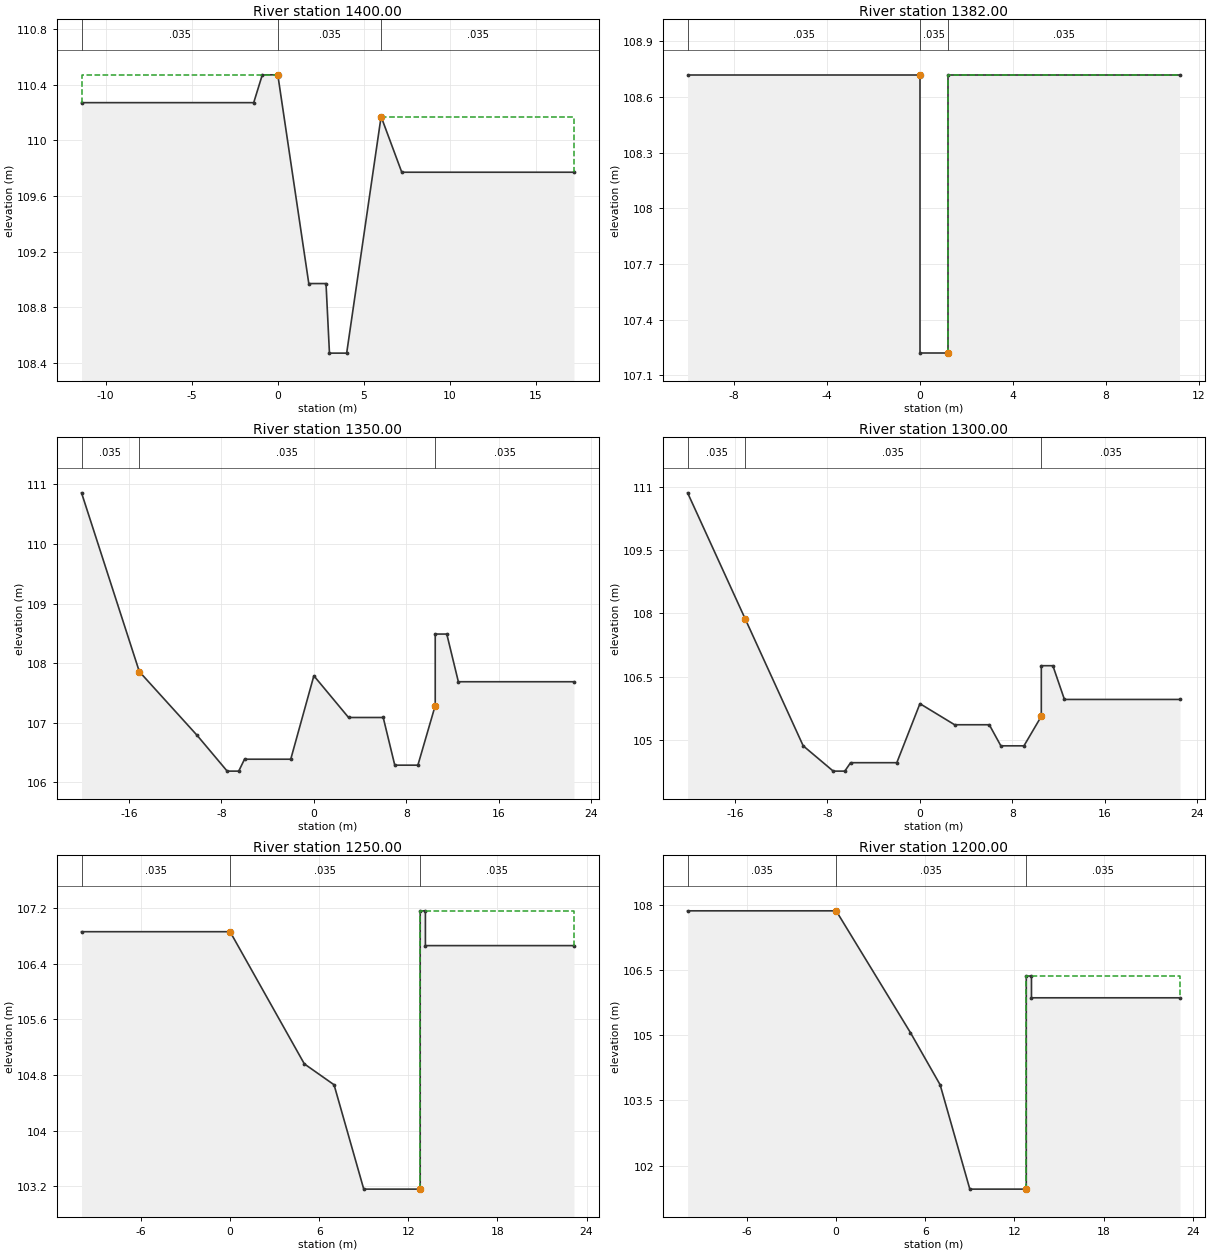
Type RM Length L Ch R = 1 ,1400.00 ,18,18,18
BEGIN DESCRIPTION:
28
END DESCRIPTION:
#Sta/Elev= 11
   -11.4  110.27    -1.4  110.27     -.9  110.47       0  110.47     1.8  108.97
     2.8  108.97       3  108.47       4  108.47       6  110.17     7.2  109.77
    17.2  109.77
#Mann= 3 , 0 , 0
   -11.4    .035       0       0    .035       0       6    .035       0
#XS Ineff= 2 , 0
               0  110.47       6          110.17
Permanent Ineff=
       F       F
Bank Sta=0,6
XS Rating Curve= 0
Exp/Cntr=.3,.1

Type RM Length L Ch R = 1 ,1382.00 ,32,32,32
BEGIN DESCRIPTION:
27.032
END DESCRIPTION:
#Sta/Elev= 6
     -10  108.72       0  108.72       0  107.22     1.2  107.22     1.2  108.72
    11.2  108.72
#Mann= 3 , 0 , 0
     -10    .035       0       0    .035       0     1.2    .035       0
#XS Ineff= 2 , 0
               0  108.72     1.2          108.72
Permanent Ineff=
       F       F
Bank Sta=0,1.2
XS Rating Curve= 0
Exp/Cntr=.3,.1

Type RM Length L Ch R = 1 ,1350.00 ,50,50,50
BEGIN DESCRIPTION:
27
END DESCRIPTION:
#Sta/Elev= 17
   -20.1  110.86   -15.1  107.86   -10.1  106.79    -7.5  106.19    -6.5  106.19
      -6  106.39      -2  106.39       0  107.79       3  107.09       6  107.09
       7  106.29       9  106.29    10.5  107.29    10.5  108.49    11.5  108.49
    12.5  107.69    22.5  107.69
#Mann= 3 , 0 , 0
   -20.1    .035       0   -15.1    .035       0    10.5    .035       0
Bank Sta=-15.1,10.5
XS Rating Curve= 0
Exp/Cntr=.3,.1

Type RM Length L Ch R = 1 ,1300.00 ,50,50,50
BEGIN DESCRIPTION:
26
END DESCRIPTION:
#Sta/Elev= 17
   -20.1  110.86   -15.1  107.86   -10.1  104.86    -7.5  104.26    -6.5  104.26
      -6  104.46      -2  104.46       0  105.86       3  105.36       6  105.36
       7  104.86       9  104.86    10.5  105.56    10.5  106.76    11.5  106.76
    12.5  105.96    22.5  105.96
#Mann= 3 , 0 , 0
   -20.1    .035       0   -15.1    .035       0    10.5    .035       0
Bank Sta=-15.1,10.5
XS Rating Curve= 0
Exp/Cntr=.3,.1

Type RM Length L Ch R = 1 ,1250.00 ,50,50,50
BEGIN DESCRIPTION:
25
END DESCRIPTION:
#Sta/Elev= 10
     -10  106.86       0  106.86       5  104.96       7  104.66       9  103.16
    12.8  103.16    12.8  107.16   13.15  107.16   13.15  106.66   23.15  106.66
#Mann= 3 , 0 , 0
     -10    .035       0       0    .035       0    12.8    .035       0
#XS Ineff= 2 , 0
               0  106.86    12.8          107.16
Permanent Ineff=
       F       F
Bank Sta=0,12.8
XS Rating Curve= 0
Exp/Cntr=.3,.1

Type RM Length L Ch R = 1 ,1200.00 ,50,50,50
BEGIN DESCRIPTION:
24
END DESCRIPTION:
#Sta/Elev= 10
     -10  107.86       0  107.86       5  105.06       7  103.86       9  101.46
    12.8  101.46    12.8  106.36   13.15  106.36   13.15  105.86   23.15  105.86
#Mann= 3 , 0 , 0
     -10    .035       0       0    .035       0    12.8    .035       0
#XS Ineff= 2 , 0
               0  107.86    12.8          106.36
Permanent Ineff=
       F       F
Bank Sta=0,12.8
XS Rating Curve= 0
Exp/Cntr=.3,.1

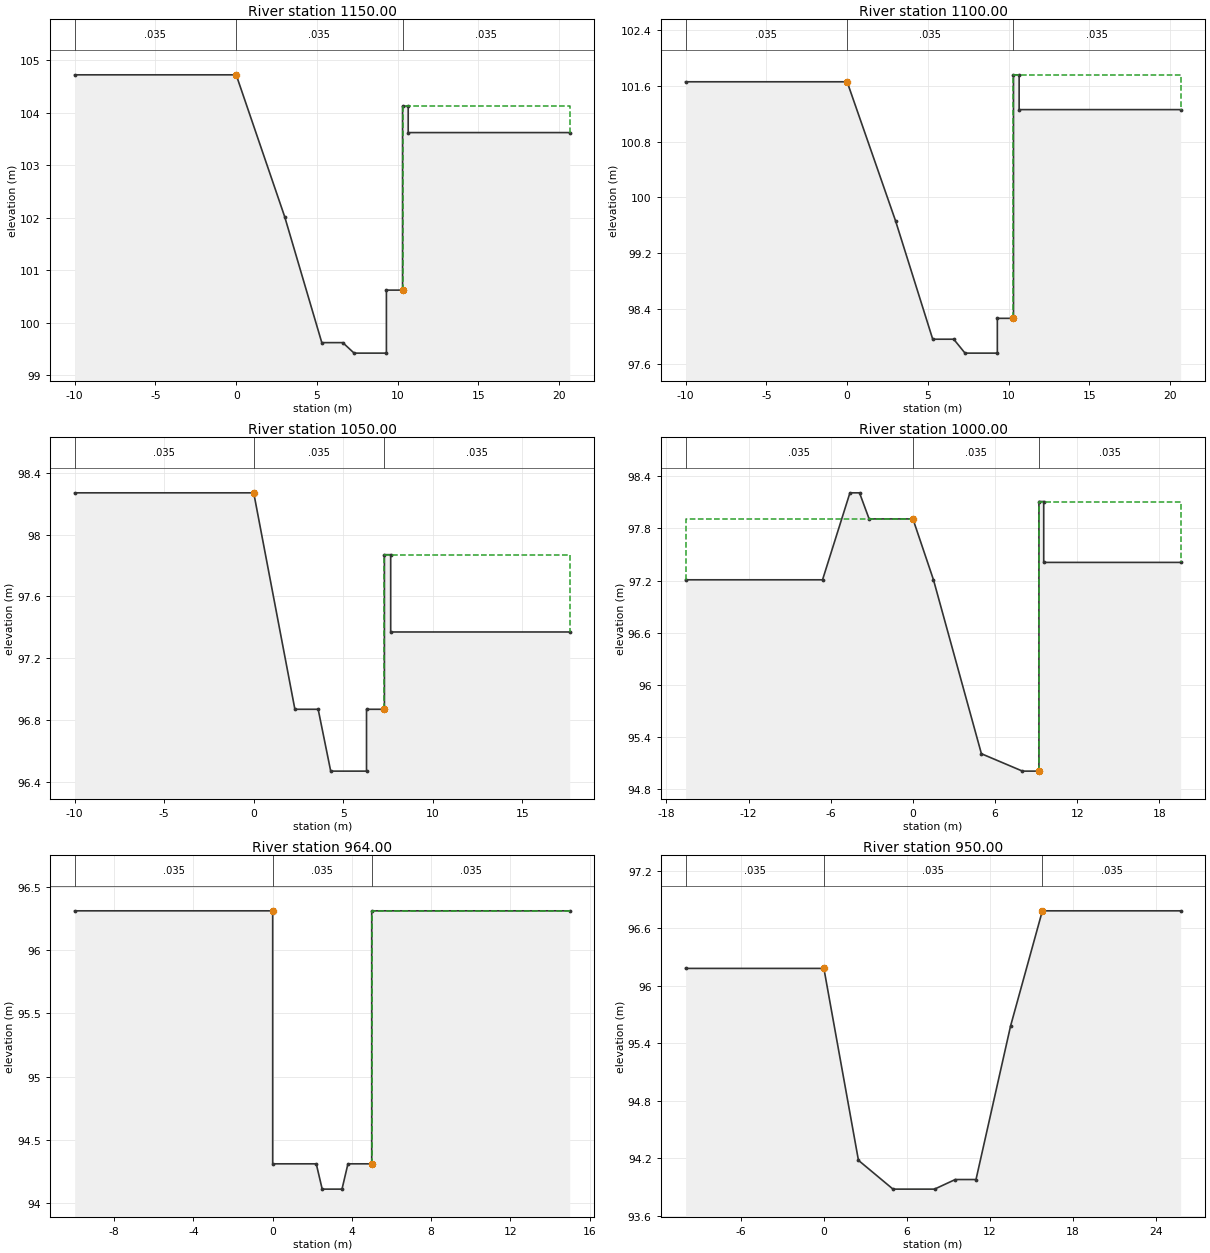
Type RM Length L Ch R = 1 ,1150.00 ,50,50,50
BEGIN DESCRIPTION:
23
END DESCRIPTION:
#Sta/Elev= 13
     -10  104.72       0  104.72       3  102.02     5.3   99.62     6.6   99.62
     7.3   99.42     9.3   99.42     9.3  100.62    10.3  100.62    10.3  104.12
   10.65  104.12   10.65  103.62   20.65  103.62
#Mann= 3 , 0 , 0
     -10    .035       0       0    .035       0    10.3    .035       0
#XS Ineff= 2 , 0
               0  104.72    10.3          104.12
Permanent Ineff=
       F       F
Bank Sta=0,10.3
XS Rating Curve= 0
Exp/Cntr=.3,.1

Type RM Length L Ch R = 1 ,1100.00 ,50,50,50
BEGIN DESCRIPTION:
22
END DESCRIPTION:
#Sta/Elev= 13
     -10  101.66       0  101.66       3   99.66     5.3   97.96     6.6   97.96
     7.3   97.76     9.3   97.76     9.3   98.26    10.3   98.26    10.3  101.76
   10.65  101.76   10.65  101.26   20.65  101.26
#Mann= 3 , 0 , 0
     -10    .035       0       0    .035       0    10.3    .035       0
#XS Ineff= 2 , 0
               0  101.66    10.3          101.76
Permanent Ineff=
       F       F
Bank Sta=0,10.3
XS Rating Curve= 0
Exp/Cntr=.3,.1

Type RM Length L Ch R = 1 ,1050.00 ,50,50,50
BEGIN DESCRIPTION:
21
END DESCRIPTION:
#Sta/Elev= 12
     -10   98.27       0   98.27     2.3   96.87     3.6   96.87     4.3   96.47
     6.3   96.47     6.3   96.87     7.3   96.87     7.3   97.87    7.65   97.87
    7.65   97.37   17.65   97.37
#Mann= 3 , 0 , 0
     -10    .035       0       0    .035       0     7.3    .035       0
#XS Ineff= 2 , 0
               0   98.27     7.3           97.87
Permanent Ineff=
       F       F
Bank Sta=0,7.3
XS Rating Curve= 0
Exp/Cntr=.3,.1

Type RM Length L Ch R = 1 ,1000.00 ,36,36,36
BEGIN DESCRIPTION:
20
END DESCRIPTION:
#Sta/Elev= 14
   -16.6   97.21    -6.6   97.21    -4.6   98.21    -3.9   98.21    -3.2   97.91
       0   97.91     1.5   97.21       5   95.21       8   95.01     9.2   95.01
     9.2   98.11    9.55   98.11    9.55   97.41   19.55   97.41
#Mann= 3 , 0 , 0
   -16.6    .035       0       0    .035       0     9.2    .035       0
#XS Ineff= 2 , 0
               0   97.91     9.2           98.11
Permanent Ineff=
       F       F
Bank Sta=0,9.2
XS Rating Curve= 0
Exp/Cntr=.3,.1

Type RM Length L Ch R = 1 ,964.00  ,14,14,14
BEGIN DESCRIPTION:
19.014
END DESCRIPTION:
#Sta/Elev= 10
     -10   96.31       0   96.31       0   94.31     2.2   94.31     2.5   94.11
     3.5   94.11     3.8   94.31       5   94.31       5   96.31      15   96.31
#Mann= 3 , 0 , 0
     -10    .035       0       0    .035       0       5    .035       0
#XS Ineff= 2 , 0
               0   96.31       5           96.31
Permanent Ineff=
       F       F
Bank Sta=0,5
XS Rating Curve= 0
Exp/Cntr=.3,.1

Type RM Length L Ch R = 1 ,950.00  ,50,50,50
BEGIN DESCRIPTION:
19
END DESCRIPTION:
#Sta/Elev= 10
     -10   96.18       0   96.18     2.5   94.18       5   93.88       8   93.88
     9.5   93.98      11   93.98    13.5   95.58    15.8   96.78    25.8   96.78
#Mann= 3 , 0 , 0
     -10    .035       0       0    .035       0    15.8    .035       0
#XS Ineff= 2 , 0
               0   96.18    15.8           96.78
Permanent Ineff=
       F       F
Bank Sta=0,15.8
XS Rating Curve= 0
Exp/Cntr=.3,.1

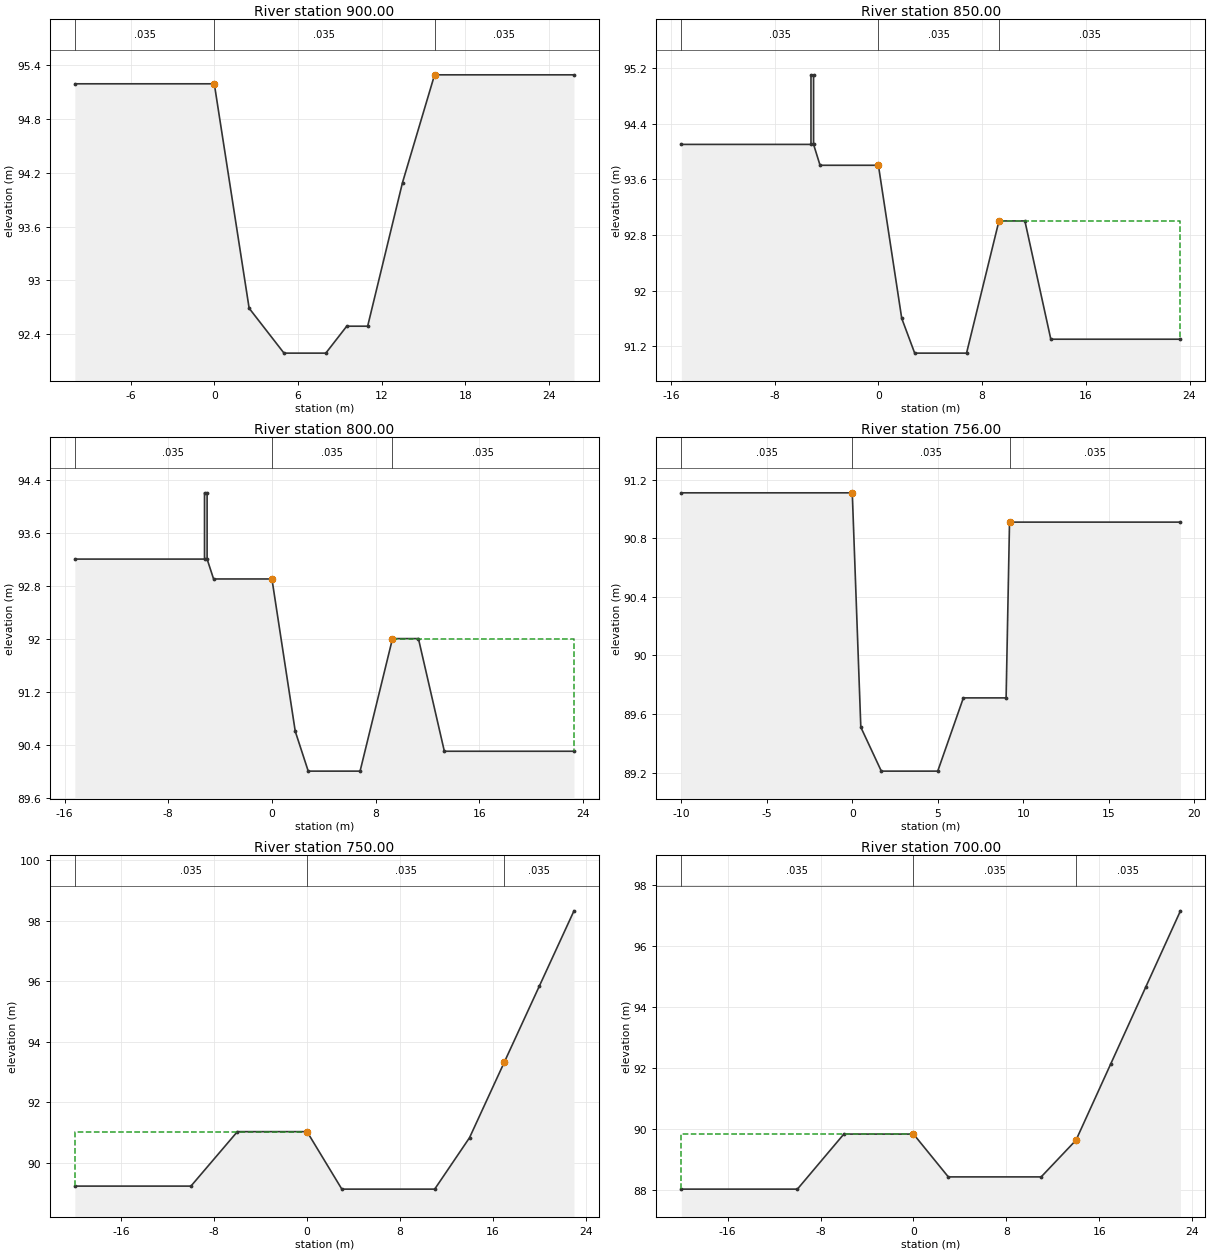
Type RM Length L Ch R = 1 ,900.00  ,50,50,50
BEGIN DESCRIPTION:
18
END DESCRIPTION:
#Sta/Elev= 10
     -10   95.19       0   95.19     2.5   92.69       5   92.19       8   92.19
     9.5   92.49      11   92.49    13.5   94.09    15.8   95.29    25.8   95.29
#Mann= 3 , 0 , 0
     -10    .035       0       0    .035       0    15.8    .035       0
#XS Ineff= 2 , 0
               0   95.19    15.8           95.29
Permanent Ineff=
       F       F
Bank Sta=0,15.8
XS Rating Curve= 0
Exp/Cntr=.3,.1

Type RM Length L Ch R = 1 ,850.00  ,50,50,50
BEGIN DESCRIPTION:
17
END DESCRIPTION:
#Sta/Elev= 14
   -15.2    94.1    -5.2    94.1    -5.2    95.1      -5    95.1      -5    94.1
    -4.5    93.8       0    93.8     1.8    91.6     2.8    91.1     6.8    91.1
     9.3      93    11.3      93    13.3    91.3    23.3    91.3
#Mann= 3 , 0 , 0
   -15.2    .035       0       0    .035       0     9.3    .035       0
#XS Ineff= 2 , 0
               0    93.8     9.3              93
Permanent Ineff=
       F       F
Bank Sta=0,9.3
XS Rating Curve= 0
Exp/Cntr=.3,.1

Type RM Length L Ch R = 1 ,800.00  ,44,44,44
BEGIN DESCRIPTION:
16
END DESCRIPTION:
#Sta/Elev= 14
   -15.2   93.21    -5.2   93.21    -5.2   94.21      -5   94.21      -5   93.21
    -4.5   92.91       0   92.91     1.8   90.61     2.8   90.01     6.8   90.01
     9.3   92.01    11.3   92.01    13.3   90.31    23.3   90.31
#Mann= 3 , 0 , 0
   -15.2    .035       0       0    .035       0     9.3    .035       0
#XS Ineff= 2 , 0
               0   92.91     9.3           92.01
Permanent Ineff=
       F       F
Bank Sta=0,9.3
XS Rating Curve= 0
Exp/Cntr=.3,.1

Type RM Length L Ch R = 1 ,756.00  ,6,6,6
BEGIN DESCRIPTION:
15.006
END DESCRIPTION:
#Sta/Elev= 9
     -10   91.11       0   91.11      .5   89.51     1.7   89.21       5   89.21
     6.5   89.71       9   89.71     9.2   90.91    19.2   90.91
#Mann= 3 , 0 , 0
     -10    .035       0       0    .035       0     9.2    .035       0
#XS Ineff= 2 , 0
               0   91.11     9.2           90.91
Permanent Ineff=
       F       F
Bank Sta=0,9.2
XS Rating Curve= 0
Exp/Cntr=.3,.1

Type RM Length L Ch R = 1 ,750.00  ,50,50,50
BEGIN DESCRIPTION:
15
END DESCRIPTION:
#Sta/Elev= 10
     -20   89.22     -10   89.22      -6   91.02       0   91.02       3   89.12
      11   89.12      14   90.82      17   93.32      20   95.82      23   98.32
#Mann= 3 , 0 , 0
     -20    .035       0       0    .035       0      17    .035       0
#XS Ineff= 2 , 0
               0   91.02      17           93.32
Permanent Ineff=
       F       F
Bank Sta=0,17
XS Rating Curve= 0
Exp/Cntr=.3,.1

Type RM Length L Ch R = 1 ,700.00  ,50,50,50
BEGIN DESCRIPTION:
14
END DESCRIPTION:
#Sta/Elev= 10
     -20   88.04     -10   88.04      -6   89.84       0   89.84       3   88.44
      11   88.44      14   89.64      17   92.14      20   94.64      23   97.14
#Mann= 3 , 0 , 0
     -20    .035       0       0    .035       0      14    .035       0
#XS Ineff= 2 , 0
               0   89.84      14           89.64
Permanent Ineff=
       F       F
Bank Sta=0,14
XS Rating Curve= 0
Exp/Cntr=.3,.1

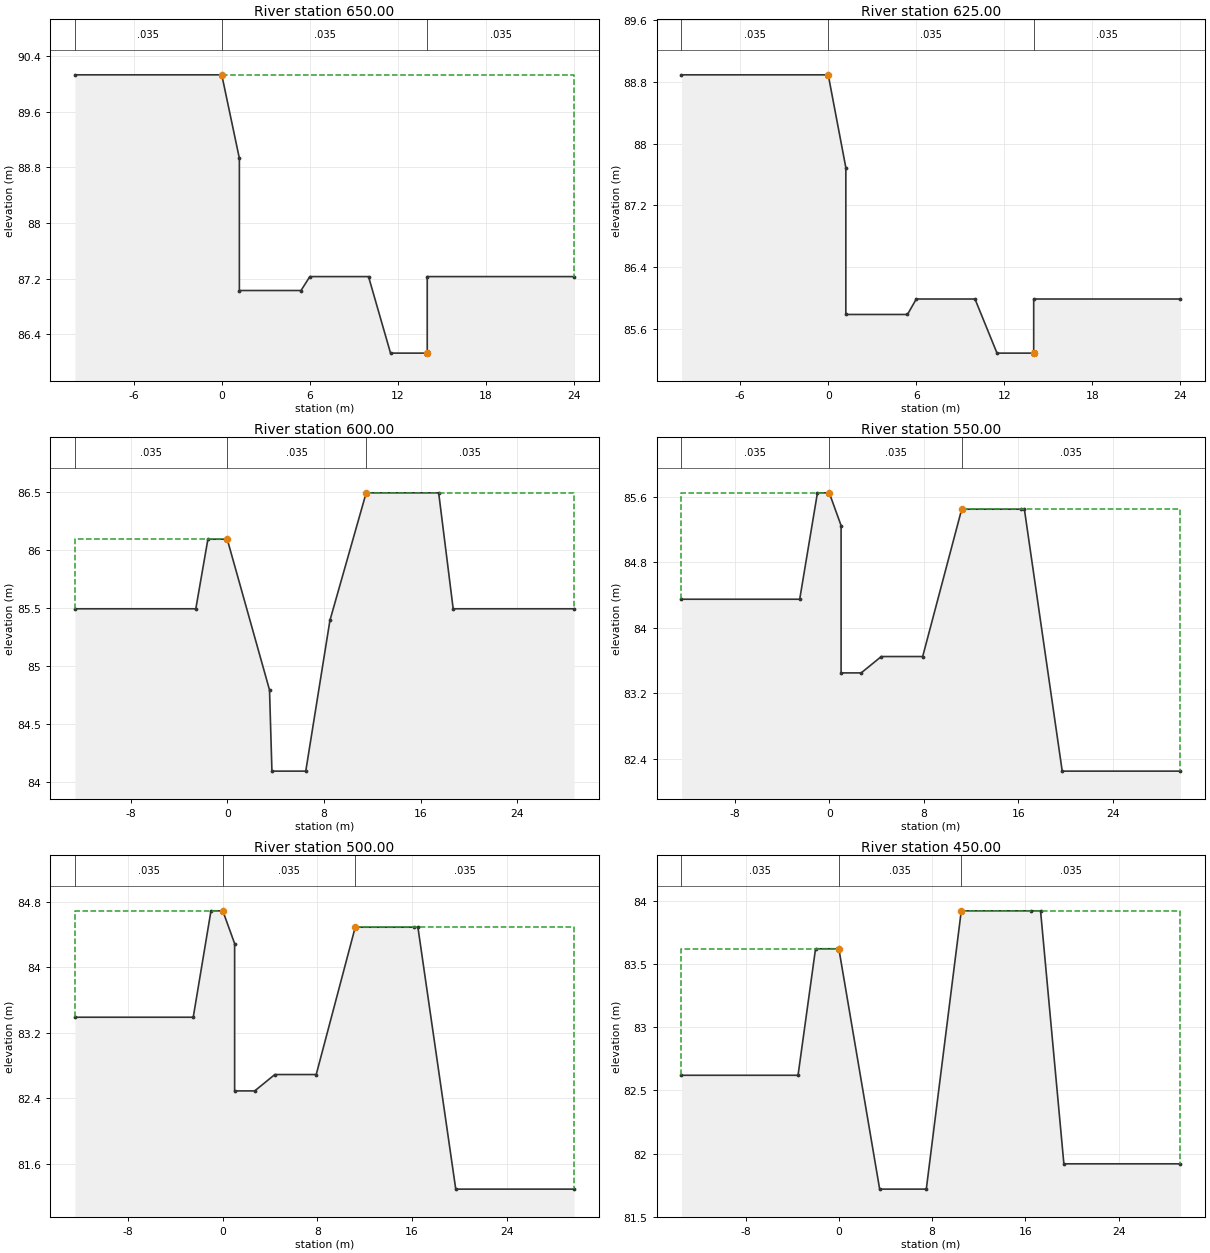
Type RM Length L Ch R = 1 ,650.00  ,25,25,25
BEGIN DESCRIPTION:
13
END DESCRIPTION:
#Sta/Elev= 11
     -10   90.13       0   90.13     1.2   88.93     1.2   87.03     5.4   87.03
       6   87.23      10   87.23    11.5   86.13      14   86.13      14   87.23
      24   87.23
#Mann= 3 , 0 , 0
     -10    .035       0       0    .035       0      14    .035       0
#XS Ineff= 2 , 0
       0       0   90.13      14       0   86.13
Permanent Ineff=
       F       F
Bank Sta=0,14
XS Rating Curve= 0
Exp/Cntr=.3,.1

Type RM Length L Ch R = 1 ,625.00  ,25,25,25
BEGIN DESCRIPTION:
12.025
END DESCRIPTION:
#Sta/Elev= 11
     -10   88.89       0   88.89     1.2   87.69     1.2   85.79     5.4   85.79
       6   85.99      10   85.99    11.5   85.29      14   85.29      14   85.99
      24   85.99
#Mann= 3 , 0 , 0
     -10    .035       0       0    .035       0      14    .035       0
Bank Sta=0,14
XS Rating Curve= 0
Exp/Cntr=.3,.1

Type RM Length L Ch R = 1 ,600.00  ,50,50,50
BEGIN DESCRIPTION:
12
END DESCRIPTION:
#Sta/Elev= 12
   -12.6   85.49    -2.6   85.49    -1.6   86.09       0   86.09     3.5   84.79
     3.7   84.09     6.5   84.09     8.5   85.39    11.5   86.49    17.5   86.49
    18.7   85.49    28.7   85.49
#Mann= 3 , 0 , 0
   -12.6    .035       0       0    .035       0    11.5    .035       0
#XS Ineff= 2 , 0
               0   86.09    11.5           86.49
Permanent Ineff=
       F       F
Bank Sta=0,11.5
XS Rating Curve= 0
Exp/Cntr=.3,.1

Type RM Length L Ch R = 1 ,550.00  ,50,50,50
BEGIN DESCRIPTION:
11
END DESCRIPTION:
#Sta/Elev= 14
   -12.5   84.35    -2.5   84.35      -1   85.65       0   85.65       1   85.25
       1   83.45     2.7   83.45     4.4   83.65     7.9   83.65    11.2   85.45
    16.2   85.45    16.5   85.45    19.7   82.25    29.7   82.25
#Mann= 3 , 0 , 0
   -12.5    .035       0       0    .035       0    11.2    .035       0
#XS Ineff= 2 , 0
               0   85.65    11.2           85.45
Permanent Ineff=
       F       F
Bank Sta=0,11.2
XS Rating Curve= 0
Exp/Cntr=.3,.1

Type RM Length L Ch R = 1 ,500.00  ,50,50,50
BEGIN DESCRIPTION:
10
END DESCRIPTION:
#Sta/Elev= 14
   -12.5   83.39    -2.5   83.39      -1   84.69       0   84.69       1   84.29
       1   82.49     2.7   82.49     4.4   82.69     7.9   82.69    11.2   84.49
    16.2   84.49    16.5   84.49    19.7   81.29    29.7   81.29
#Mann= 3 , 0 , 0
   -12.5    .035       0       0    .035       0    11.2    .035       0
#XS Ineff= 2 , 0
               0   84.69    11.2           84.49
Permanent Ineff=
       F       F
Bank Sta=0,11.2
XS Rating Curve= 0
Exp/Cntr=.3,.1

Type RM Length L Ch R = 1 ,450.00  ,50,50,50
BEGIN DESCRIPTION:
9
END DESCRIPTION:
#Sta/Elev= 11
   -13.5   82.62    -3.5   82.62      -2   83.62       0   83.62     3.5   81.72
     7.5   81.72    10.5   83.92    16.5   83.92    17.3   83.92    19.3   81.92
    29.3   81.92
#Mann= 3 , 0 , 0
   -13.5    .035       0       0    .035       0    10.5    .035       0
#XS Ineff= 2 , 0
               0   83.62    10.5           83.92
Permanent Ineff=
       F       F
Bank Sta=0,10.5
XS Rating Curve= 0
Exp/Cntr=.3,.1