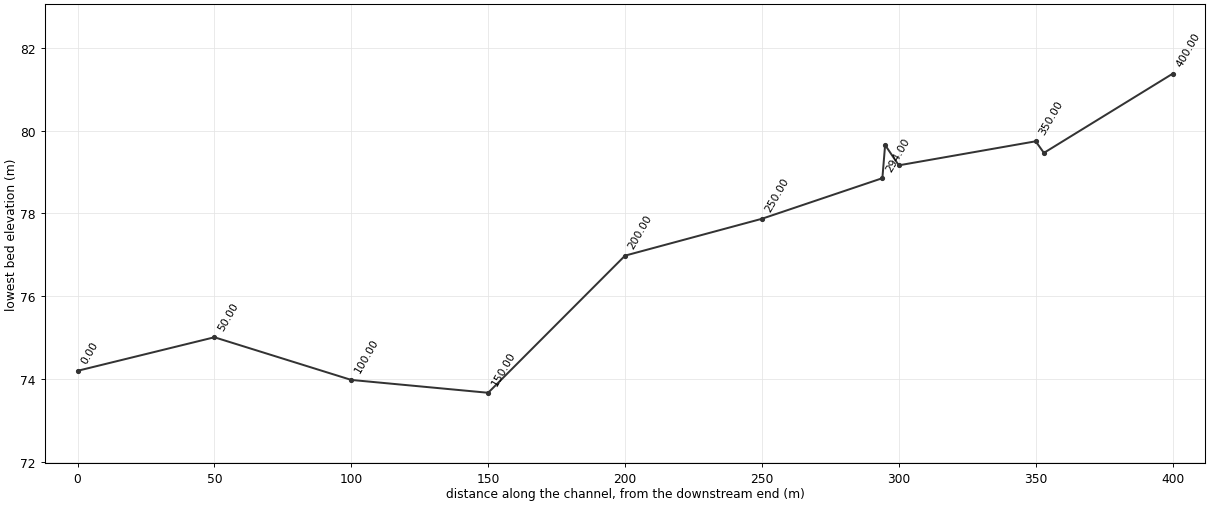
HEC-RAS study DHC.prj: buldangdong-ch

--- DHC.g01 (geometry) --- (continued)

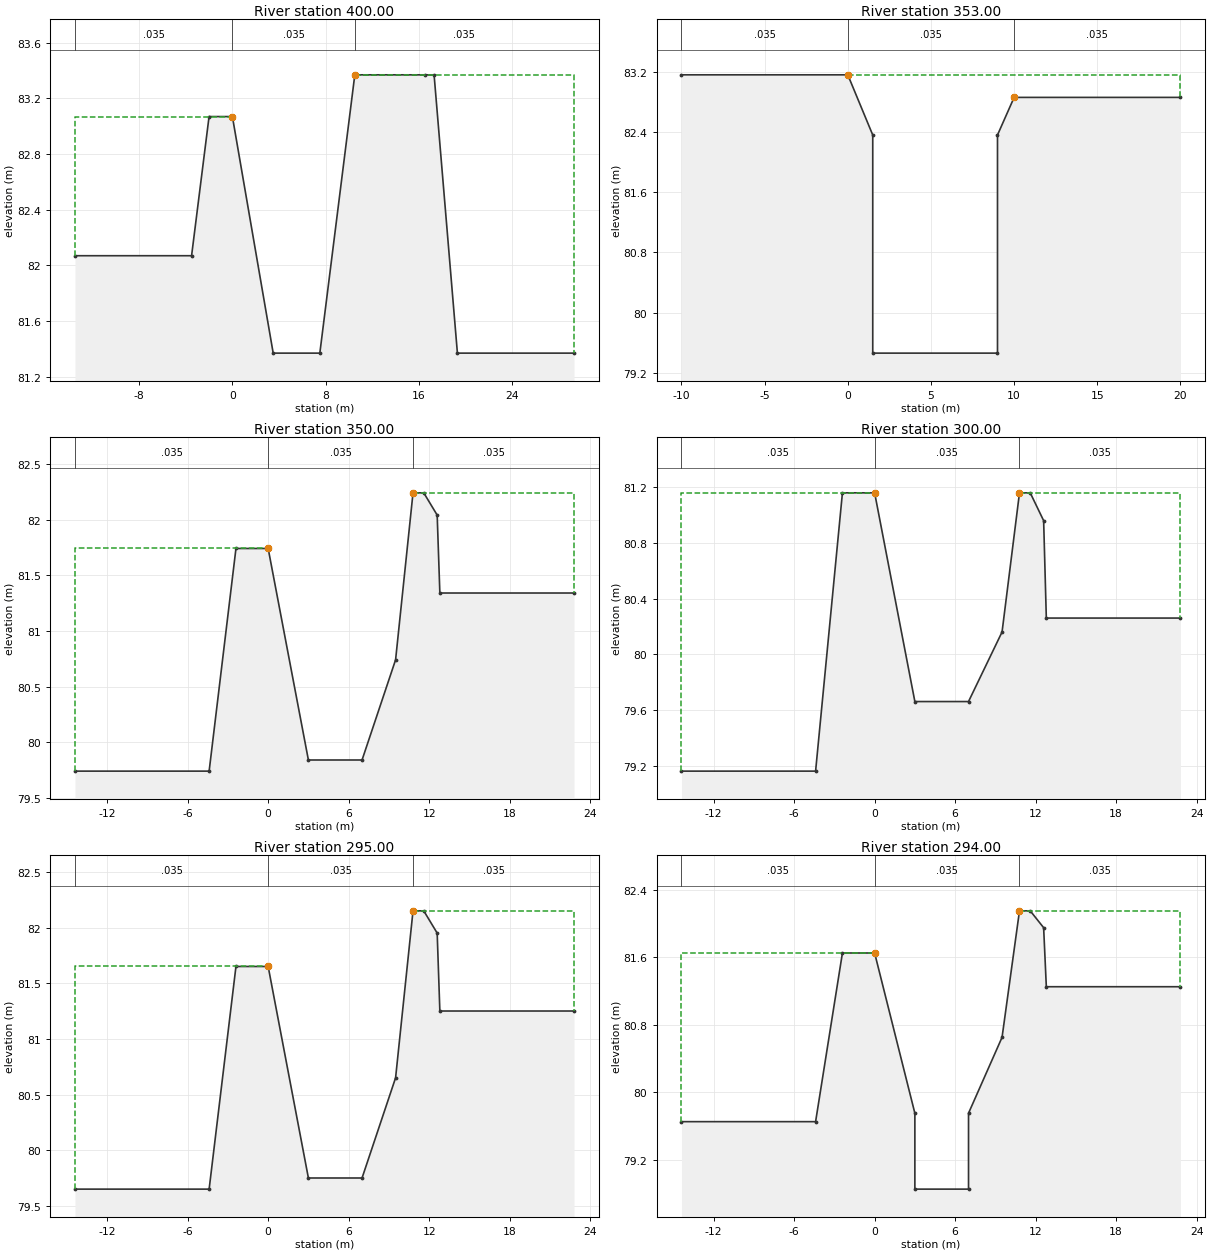
Type RM Length L Ch R = 1 ,400.00  ,47,47,47
BEGIN DESCRIPTION:
8
END DESCRIPTION:
#Sta/Elev= 11
   -13.5   82.07    -3.5   82.07      -2   83.07       0   83.07     3.5   81.37
     7.5   81.37    10.5   83.37    16.5   83.37    17.3   83.37    19.3   81.37
    29.3   81.37
#Mann= 3 , 0 , 0
   -13.5    .035       0       0    .035       0    10.5    .035       0
#XS Ineff= 2 , 0
               0   83.07    10.5           83.37
Permanent Ineff=
       F       F
Bank Sta=0,10.5
XS Rating Curve= 0
Exp/Cntr=.3,.1

Type RM Length L Ch R = 1 ,353.00  ,3,3,3
BEGIN DESCRIPTION:
7.003
END DESCRIPTION:
#Sta/Elev= 8
     -10   83.16       0   83.16     1.5   82.36     1.5   79.46       9   79.46
       9   82.36      10   82.86      20   82.86
#Mann= 3 , 0 , 0
     -10    .035       0       0    .035       0      10    .035       0
#XS Ineff= 2 , 0
       0       0   83.16      10       0   82.86
Permanent Ineff=
       F       F
Bank Sta=0,10
XS Rating Curve= 0
Exp/Cntr=.3,.1

Type RM Length L Ch R = 1 ,350.00  ,50,50,50
BEGIN DESCRIPTION:
7
END DESCRIPTION:
#Sta/Elev= 12
   -14.4   79.74    -4.4   79.74    -2.4   81.74       0   81.74       3   79.84
       7   79.84     9.5   80.74    10.8   82.24    11.6   82.24    12.6   82.04
    12.8   81.34    22.8   81.34
#Mann= 3 , 0 , 0
   -14.4    .035       0       0    .035       0    10.8    .035       0
#XS Ineff= 2 , 0
               0   81.74    10.8           82.24
Permanent Ineff=
       F       F
Bank Sta=0,10.8
XS Rating Curve= 0
Exp/Cntr=.3,.1

Type RM Length L Ch R = 1 ,300.00  ,5,5,5
BEGIN DESCRIPTION:
6
END DESCRIPTION:
#Sta/Elev= 12
   -14.4   79.16    -4.4   79.16    -2.4   81.16       0   81.16       3   79.66
       7   79.66     9.5   80.16    10.8   81.16    11.6   81.16    12.6   80.96
    12.8   80.26    22.8   80.26
#Mann= 3 , 0 , 0
   -14.4    .035       0       0    .035       0    10.8    .035       0
#XS Ineff= 2 , 0
               0   81.16    10.8           81.16
Permanent Ineff=
       F       F
Bank Sta=0,10.8
XS Rating Curve= 0
Exp/Cntr=.3,.1

Type RM Length L Ch R = 1 ,295.00  ,1,1,1
BEGIN DESCRIPTION:
5.045
END DESCRIPTION:
#Sta/Elev= 12
   -14.4   79.65    -4.4   79.65    -2.4   81.65       0   81.65       3   79.75
       7   79.75     9.5   80.65    10.8   82.15    11.6   82.15    12.6   81.95
    12.8   81.25    22.8   81.25
#Mann= 3 , 0 , 0
   -14.4    .035       0       0    .035       0    10.8    .035       0
#XS Ineff= 2 , 0
               0   81.65    10.8           82.15
Permanent Ineff=
       F       F
Bank Sta=0,10.8
XS Rating Curve= 0
Exp/Cntr=.3,.1

Type RM Length L Ch R = 1 ,294.00  ,44,44,44
BEGIN DESCRIPTION:
5.044
END DESCRIPTION:
#Sta/Elev= 14
   -14.4   79.65    -4.4   79.65    -2.4   81.65       0   81.65       3   79.75
       3   78.85       7   78.85       7   79.75     9.5   80.65    10.8   82.15
    11.6   82.15    12.6   81.95    12.8   81.25    22.8   81.25
#Mann= 3 , 0 , 0
   -14.4    .035       0       0    .035       0    10.8    .035       0
#XS Ineff= 2 , 0
               0   81.65    10.8           82.15
Permanent Ineff=
       F       F
Bank Sta=0,10.8
XS Rating Curve= 0
Exp/Cntr=.3,.1

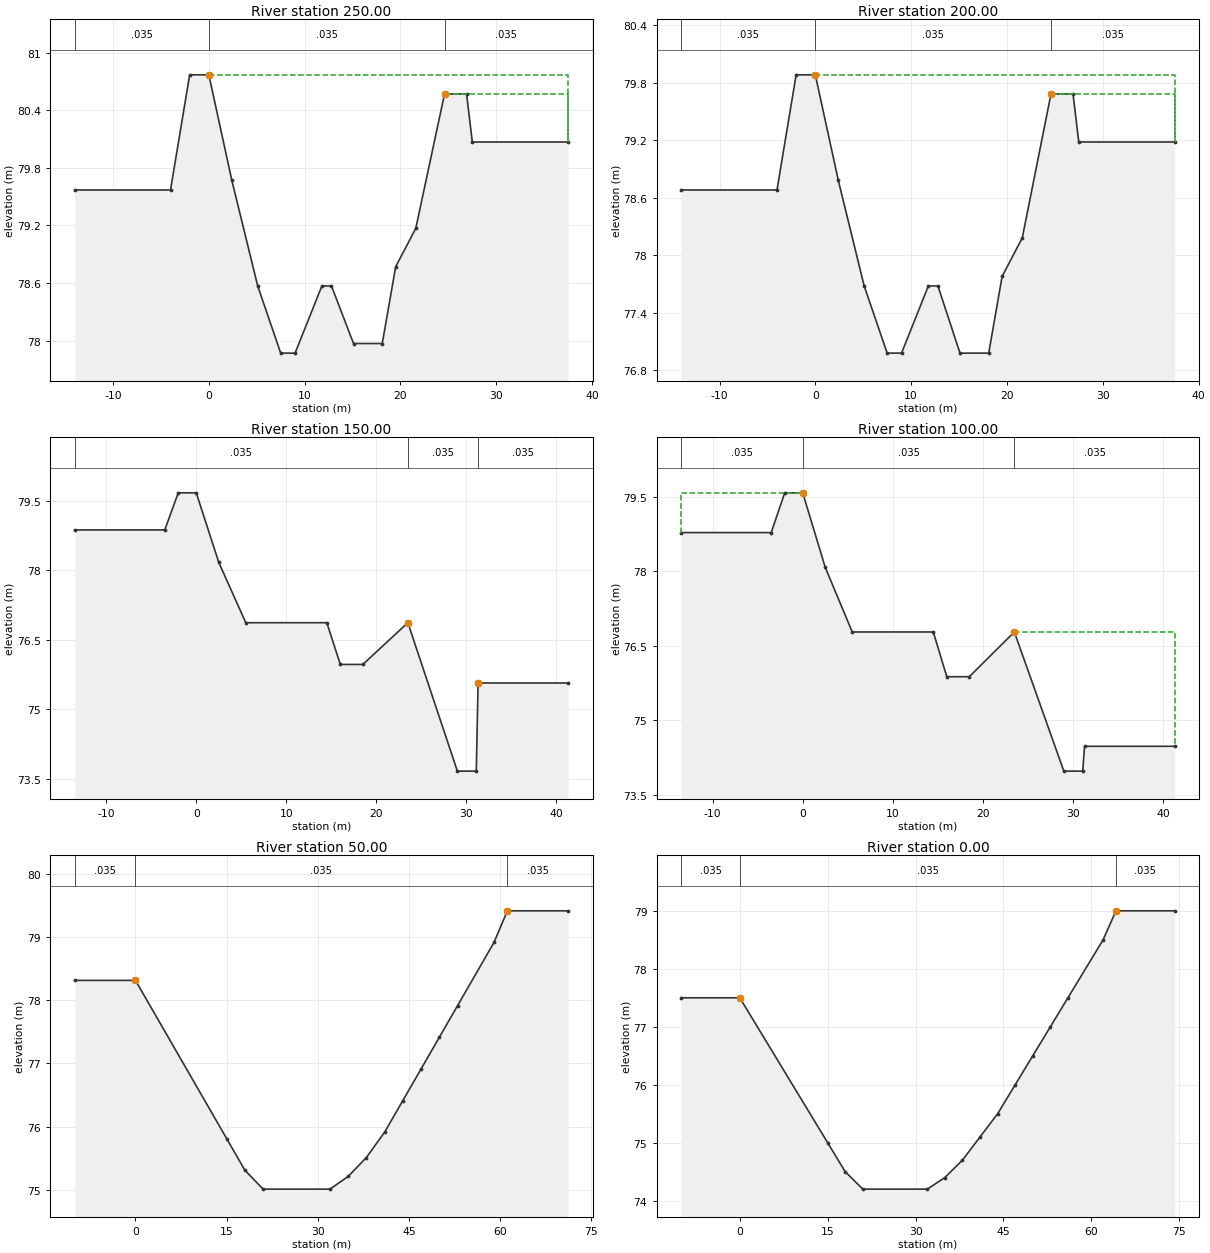
Type RM Length L Ch R = 1 ,250.00  ,50,50,50
BEGIN DESCRIPTION:
5
END DESCRIPTION:
#Sta/Elev= 18
     -14   79.57      -4   79.57      -2   80.77       0   80.77     2.4   79.67
     5.1   78.57     7.5   77.87       9   77.87    11.8   78.57    12.8   78.57
    15.1   77.97    18.1   77.97    19.5   78.77    21.6   79.17    24.6   80.57
    26.9   80.57    27.5   80.07    37.5   80.07
#Mann= 3 , 0 , 0
     -14    .035       0       0    .035       0    24.6    .035       0
#XS Ineff= 2 , 0
       0       0   80.77    24.6       0   80.57
Permanent Ineff=
       F       F
Bank Sta=0,24.6
XS Rating Curve= 0
Exp/Cntr=.3,.1

Type RM Length L Ch R = 1 ,200.00  ,50,50,50
BEGIN DESCRIPTION:
4
END DESCRIPTION:
#Sta/Elev= 18
     -14   78.68      -4   78.68      -2   79.88       0   79.88     2.4   78.78
     5.1   77.68     7.5   76.98       9   76.98    11.8   77.68    12.8   77.68
    15.1   76.98    18.1   76.98    19.5   77.78    21.6   78.18    24.6   79.68
    26.9   79.68    27.5   79.18    37.5   79.18
#Mann= 3 , 0 , 0
     -14    .035       0       0    .035       0    24.6    .035       0
#XS Ineff= 2 , 0
       0       0   79.88    24.6       0   79.68
Permanent Ineff=
       F       F
Bank Sta=0,24.6
XS Rating Curve= 0
Exp/Cntr=.3,.1

Type RM Length L Ch R = 1 ,150.00  ,50,50,50
BEGIN DESCRIPTION:
3
END DESCRIPTION:
#Sta/Elev= 14
   -13.5   78.87    -3.5   78.87      -2   79.67       0   79.67     2.5   78.17
     5.5   76.87    14.5   76.87      16   75.97    18.5   75.97    23.5   76.87
      29   73.67    31.1   73.67    31.3   75.57    41.3   75.57
#Mann= 3 , 0 , 0
   -13.5    .035       0    23.5    .035       0    31.3    .035       0
#XS Ineff= 2 , 0
       0    23.5   76.87    31.3       0   75.57
Permanent Ineff=
       F       F
Bank Sta=23.5,31.3
XS Rating Curve= 0
Exp/Cntr=.3,.1

Type RM Length L Ch R = 1 ,100.00  ,50,50,50
BEGIN DESCRIPTION:
2
END DESCRIPTION:
#Sta/Elev= 14
   -13.5   78.78    -3.5   78.78      -2   79.58       0   79.58     2.5   78.08
     5.5   76.78    14.5   76.78      16   75.88    18.5   75.88    23.5   76.78
      29   73.98    31.1   73.98    31.3   74.48    41.3   74.48
#Mann= 3 , 0 , 0
   -13.5    .035       0       0    .035       0    23.5    .035       0
#XS Ineff= 2 , 0
               0   79.58    23.5           76.78
Permanent Ineff=
       F       F
Bank Sta=0,23.5
XS Rating Curve= 0
Exp/Cntr=.3,.1

Type RM Length L Ch R = 1 ,50.00   ,50,50,50
BEGIN DESCRIPTION:
1
END DESCRIPTION:
#Sta/Elev= 16
     -10   78.31       0   78.31      15   75.81      18   75.31      21   75.01
      32   75.01      35   75.21      38   75.51      41   75.91      44   76.41
      47   76.91      50   77.41      53   77.91      59   78.91    61.2   79.41
    71.2   79.41
#Mann= 3 , 0 , 0
     -10    .035       0       0    .035       0    61.2    .035       0
#XS Ineff= 2 , 0
       0       0   78.31    61.2       0   79.41
Permanent Ineff=
       F       F
Bank Sta=0,61.2
XS Rating Curve= 0
Exp/Cntr=.3,.1

Type RM Length L Ch R = 1 ,0.00    ,0,0,0
BEGIN DESCRIPTION:
0
END DESCRIPTION:
#Sta/Elev= 17
     -10    77.5       0    77.5      15      75      18    74.5      21    74.2
      32    74.2      35    74.4      38    74.7      41    75.1      44    75.5
      47      76      50    76.5      53      77      56    77.5      62    78.5
    64.2      79    74.2      79
#Mann= 3 , 0 , 0
     -10    .035       0       0    .035       0    64.2    .035       0
#XS Ineff= 2 , 0
       0       0    77.5    64.2       0      79
Permanent Ineff=
       F       F
Bank Sta=0,64.2
XS Rating Curve= 0
Exp/Cntr=.3,.1

Chan Stop Cuts=-1