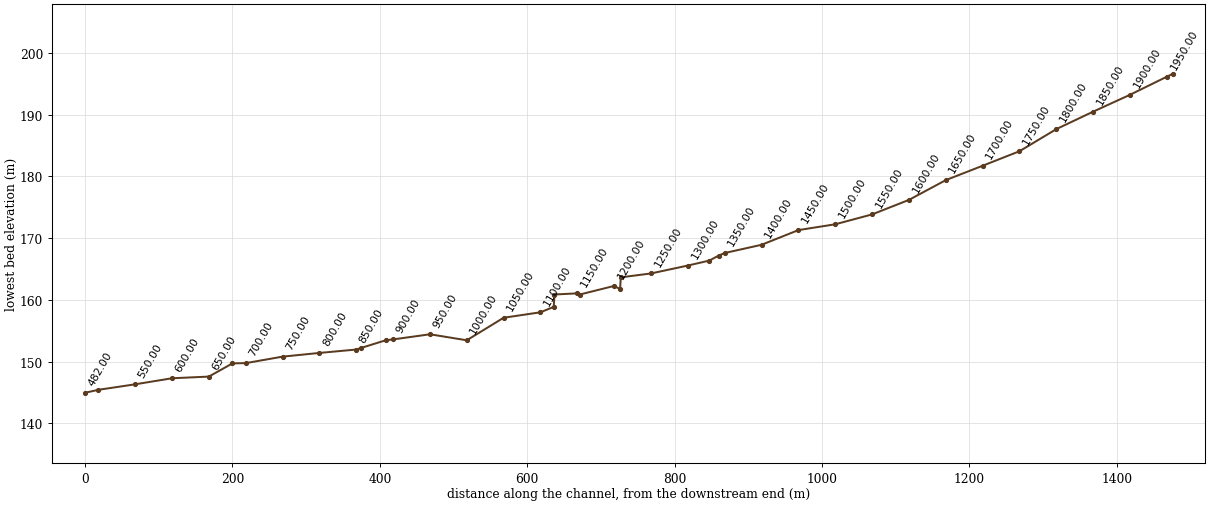
--- DHC.prj (project) ---

Proj Title=doheung-ch
Current Plan=p01
Default Exp/Contr=.3,.1
SI Units
Geom File=g01
Flow File=f01
Plan File=p01
Y Axis Title=Elevation
X Axis Title(PF)=Main Channel Distance
X Axis Title(XS)=Station
BEGIN DESCRIPTION:
           BACK WATER COMPUTATION
      APPLICATION OF HEC-2 BY Samju Construction Engineering
      doheung-ch: 10,20,30,50,80 yr
END DESCRIPTION:
DSS Export Rating Curves= 0
DSS Export Rating Curve Sorted= 0
DSS Export Volume Flow Curves= 0
DXF OffsetX= 0
DXF OffsetY= 0
DXF ScaleX= 1
DXF ScaleY= 10

--- DHC.p01 (plan) ---

Plan Title=Imported Plan 01
Version=Version 3.0.1  Mar 2001
Short Identifier=Imported Pla
Geom File=g01
Flow File=f01
Subcritical Flow
K Sum by GR= 0
Std Step Tol= 0.003
Critical Tol= 0.003
Num of Std Step Trials= 20
Max Error Tol= 0.1
Flow Tol Ratio= 0.001
Split Flow NTrial= 30
Split Flow Tol= 0.02
Split Flow Ratio= 0.02
Log Output Level= 0
Friction Slope Method= 1
Unsteady Friction Slope Method= 2
Parabolic Critical Depth
Global Vel Dist= 0 , 0 , 0
Global Log Level= 0
CheckData=True
Encroach Param=-1 ,0,0, 0
Computation Interval=1HOUR
Output Interval=1HOUR
Run HTab= 0
Run UNet= 0
Run PostProcess= 0
UNET Theta= 1
UNET ZTol= 0.02
UNET ZSATol= 0.1
UNET MxIter= 20
UNET MaxInSteps= 20
UNET DtIC= 0
UNET DtMin= 0
UNET MaxCRTS= 20
UNET WFStab= 2
UNET SFStab= 1
UNET WFX= 1
UNET SFX= 1
UNET Convert EG Bridges=-1
UNET Use Existing IB Tables=-1
Instantaneous Interval=1HOUR
Write IC File= 0
Write Velocity= 0
Write Detailed= 0

--- DHC.f01 (steady flow) ---

Flow Title=Imported Flow 01
Version=Version 3.0.1  Mar 2001
Number of Profiles= 5
Profile Names=10YR,20YR,30YR,50YR,80YR
River Rch & RM=RIVER-1,Reach-1         ,1958.00
   25.01   27.55   29.03    30.9   32.61
River Rch & RM=RIVER-1,Reach-1         ,750.00
   35.51   39.12   41.24    43.9   46.35
Boundary for River Rch & Prof#=RIVER-1,Reach-1         , 1
Up Type= 0
Dn Type= 3
Dn Slope=.02
Boundary for River Rch & Prof#=RIVER-1,Reach-1         , 2
Up Type= 0
Dn Type= 3
Dn Slope=.02
Boundary for River Rch & Prof#=RIVER-1,Reach-1         , 3
Up Type= 0
Dn Type= 3
Dn Slope=.02
Boundary for River Rch & Prof#=RIVER-1,Reach-1         , 4
Up Type= 0
Dn Type= 3
Dn Slope=.02
Boundary for River Rch & Prof#=RIVER-1,Reach-1         , 5
Up Type= 0
Dn Type= 3
Dn Slope=.02
DSS Import GetInterval= 0
DSS Import GetPeak= 0
DSS Import FillOption= 0

--- DHC.g01 (geometry) ---

Geom Title=Imported Geom 01
Version=Version 3.0.1  Mar 2001

River Reach=RIVER-1         ,Reach-1
Reach XY= 2
              .5             .95              .5             .05

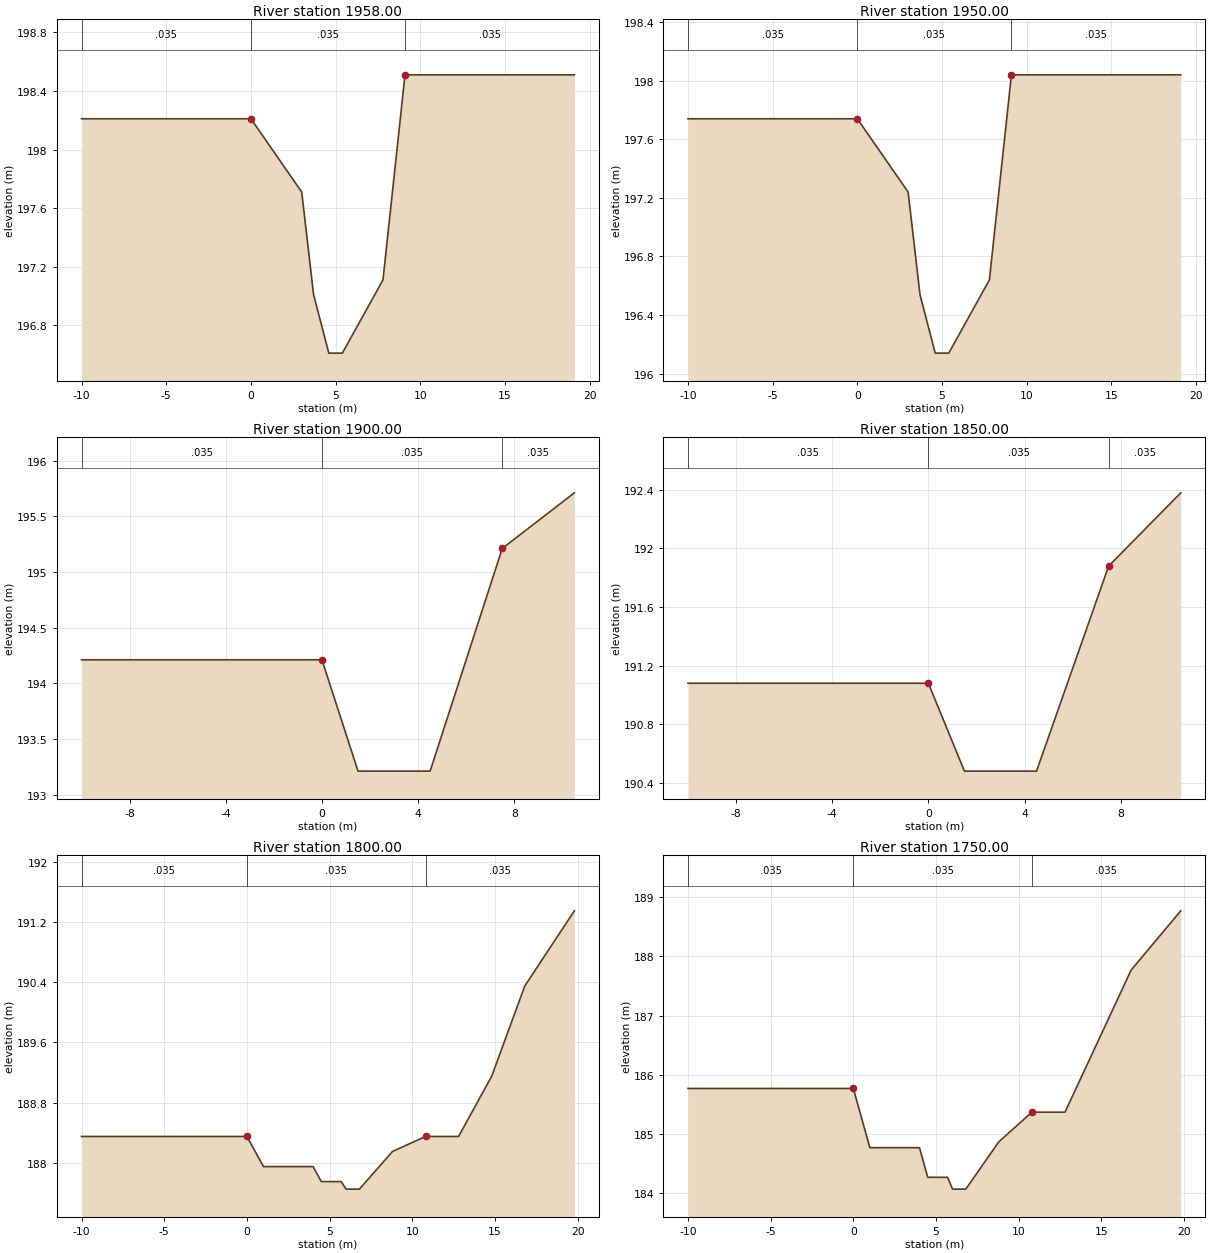
Type RM Length L Ch R = 1 ,1958.00 ,8,8,8
BEGIN DESCRIPTION:
39.008
END DESCRIPTION:
#Sta/Elev= 9
     -10  198.21       0  198.21       3  197.71     3.7  197.01     4.6  196.61
     5.4  196.61     7.8  197.11     9.1  198.51    19.1  198.51
#Mann= 3 , 0 , 0
     -10    .035       0       0    .035       0     9.1    .035       0
#XS Ineff= 2 , 0
               0  198.21     9.1          198.51
Permanent Ineff=
       F       F
Bank Sta=0,9.1
XS Rating Curve= 0
Exp/Cntr=.3,.1

Type RM Length L Ch R = 1 ,1950.00 ,50,50,50
BEGIN DESCRIPTION:
39
END DESCRIPTION:
#Sta/Elev= 9
     -10  197.74       0  197.74       3  197.24     3.7  196.54     4.6  196.14
     5.4  196.14     7.8  196.64     9.1  198.04    19.1  198.04
#Mann= 3 , 0 , 0
     -10    .035       0       0    .035       0     9.1    .035       0
#XS Ineff= 2 , 0
               0  197.74     9.1          198.04
Permanent Ineff=
       F       F
Bank Sta=0,9.1
XS Rating Curve= 0
Exp/Cntr=.3,.1

Type RM Length L Ch R = 1 ,1900.00 ,50,50,50
BEGIN DESCRIPTION:
38
END DESCRIPTION:
#Sta/Elev= 6
     -10  194.21       0  194.21     1.5  193.21     4.5  193.21     7.5  195.21
    10.5  195.71
#Mann= 3 , 0 , 0
     -10    .035       0       0    .035       0     7.5    .035       0
#XS Ineff= 2 , 0
               0  194.21     7.5          195.21
Permanent Ineff=
       F       F
Bank Sta=0,7.5
XS Rating Curve= 0
Exp/Cntr=.3,.1

Type RM Length L Ch R = 1 ,1850.00 ,50,50,50
BEGIN DESCRIPTION:
37
END DESCRIPTION:
#Sta/Elev= 6
     -10  191.08       0  191.08     1.5  190.48     4.5  190.48     7.5  191.88
    10.5  192.38
#Mann= 3 , 0 , 0
     -10    .035       0       0    .035       0     7.5    .035       0
#XS Ineff= 2 , 0
               0  191.08     7.5          191.88
Permanent Ineff=
       F       F
Bank Sta=0,7.5
XS Rating Curve= 0
Exp/Cntr=.3,.1

Type RM Length L Ch R = 1 ,1800.00 ,50,50,50
BEGIN DESCRIPTION:
36
END DESCRIPTION:
#Sta/Elev= 14
     -10  188.35       0  188.35       1  187.95       4  187.95     4.5  187.75
     5.7  187.75       6  187.65     6.8  187.65     8.8  188.15    10.8  188.35
    12.8  188.35    14.8  189.15    16.8  190.35    19.8  191.35
#Mann= 3 , 0 , 0
     -10    .035       0       0    .035       0    10.8    .035       0
#XS Ineff= 2 , 0
       0       0  188.35    10.8       0  188.35
Permanent Ineff=
       F       F
Bank Sta=0,10.8
XS Rating Curve= 0
Exp/Cntr=.3,.1

Type RM Length L Ch R = 1 ,1750.00 ,50,50,50
BEGIN DESCRIPTION:
35
END DESCRIPTION:
#Sta/Elev= 14
     -10  185.77       0  185.77       1  184.77       4  184.77     4.5  184.27
     5.7  184.27       6  184.07     6.8  184.07     8.8  184.87    10.8  185.37
    12.8  185.37    14.8  186.57    16.8  187.77    19.8  188.77
#Mann= 3 , 0 , 0
     -10    .035       0       0    .035       0    10.8    .035       0
#XS Ineff= 2 , 0
               0  185.77    10.8          185.37
Permanent Ineff=
       F       F
Bank Sta=0,10.8
XS Rating Curve= 0
Exp/Cntr=.3,.1

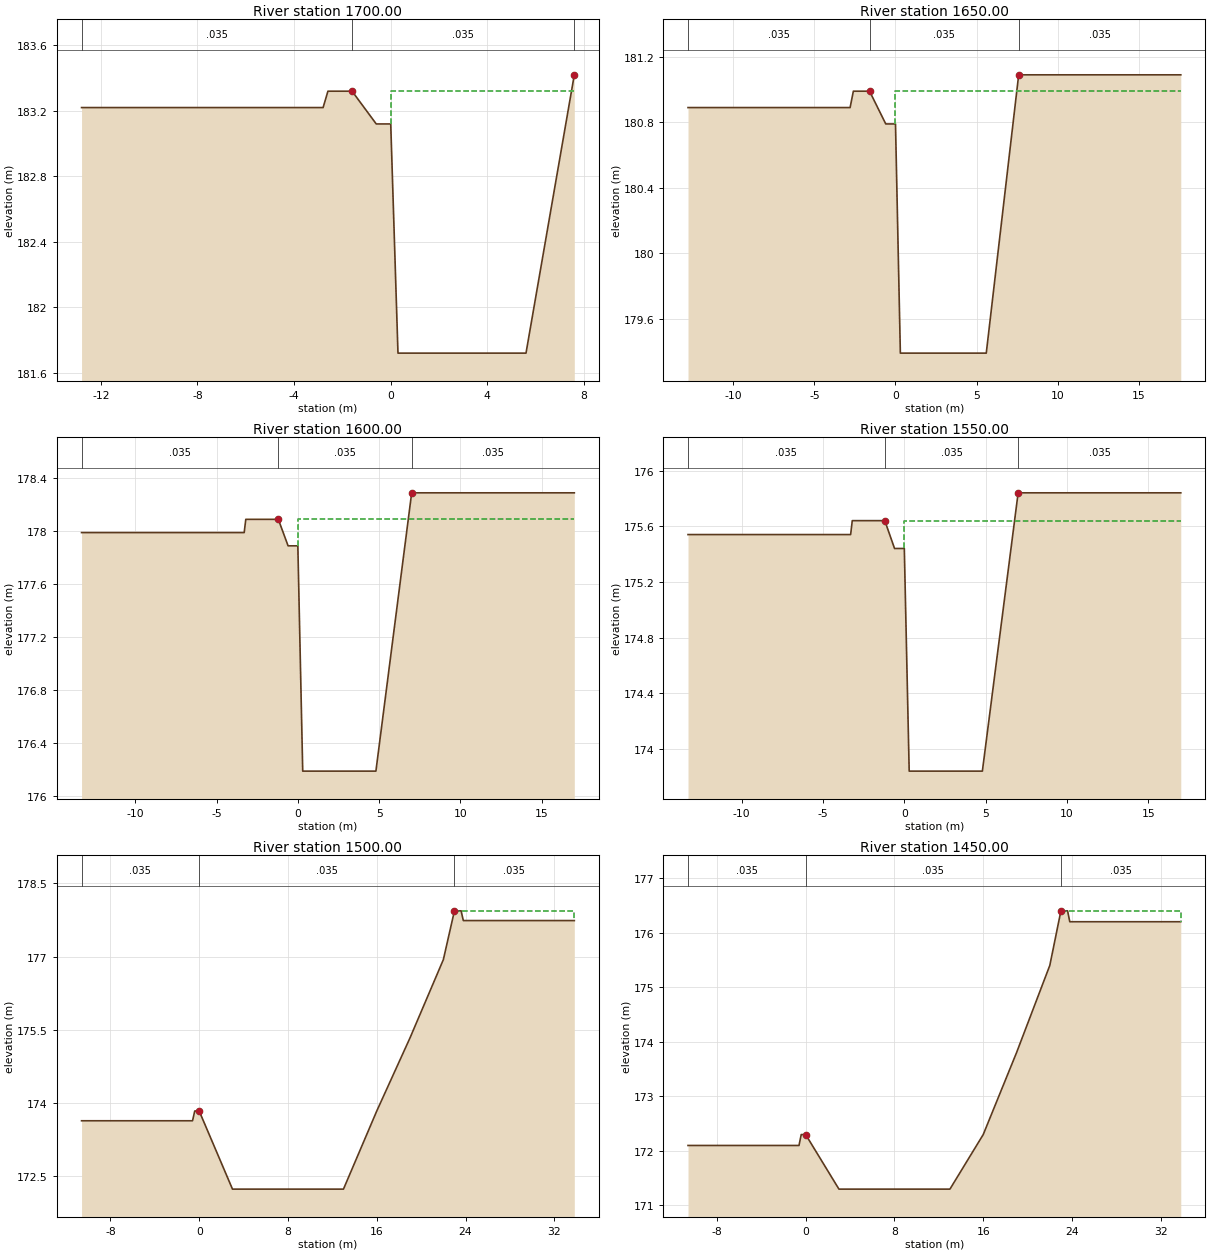
Type RM Length L Ch R = 1 ,1700.00 ,50,50,50
BEGIN DESCRIPTION:
34
END DESCRIPTION:
#Sta/Elev= 9
   -12.8  183.22    -2.8  183.22    -2.6  183.32    -1.6  183.32     -.6  183.12
       0  183.12      .3  181.72     5.6  181.72     7.6  183.42
#Mann= 3 , 0 , 0
   -12.8    .035       0    -1.6    .035       0     7.6    .035       0
#XS Ineff= 2 , 0
       0    -1.6  183.32     7.6       0  183.42
Permanent Ineff=
       F       F
Bank Sta=-1.6,7.6
XS Rating Curve= 0
Exp/Cntr=.3,.1

Type RM Length L Ch R = 1 ,1650.00 ,50,50,50
BEGIN DESCRIPTION:
33
END DESCRIPTION:
#Sta/Elev= 10
   -12.8  180.89    -2.8  180.89    -2.6  180.99    -1.6  180.99     -.6  180.79
       0  180.79      .3  179.39     5.6  179.39     7.6  181.09    17.6  181.09
#Mann= 3 , 0 , 0
   -12.8    .035       0    -1.6    .035       0     7.6    .035       0
#XS Ineff= 2 , 0
       0    -1.6  180.99     7.6       0  181.09
Permanent Ineff=
       F       F
Bank Sta=-1.6,7.6
XS Rating Curve= 0
Exp/Cntr=.3,.1

Type RM Length L Ch R = 1 ,1600.00 ,50,50,50
BEGIN DESCRIPTION:
32
END DESCRIPTION:
#Sta/Elev= 10
   -13.3  177.99    -3.3  177.99    -3.2  178.09    -1.2  178.09     -.6  177.89
       0  177.89      .3  176.19     4.8  176.19       7  178.29      17  178.29
#Mann= 3 , 0 , 0
   -13.3    .035       0    -1.2    .035       0       7    .035       0
#XS Ineff= 2 , 0
       0    -1.2  178.09       7       0  178.29
Permanent Ineff=
       F       F
Bank Sta=-1.2,7
XS Rating Curve= 0
Exp/Cntr=.3,.1

Type RM Length L Ch R = 1 ,1550.00 ,50,50,50
BEGIN DESCRIPTION:
31
END DESCRIPTION:
#Sta/Elev= 10
   -13.3  175.54    -3.3  175.54    -3.2  175.64    -1.2  175.64     -.6  175.44
       0  175.44      .3  173.84     4.8  173.84       7  175.84      17  175.84
#Mann= 3 , 0 , 0
   -13.3    .035       0    -1.2    .035       0       7    .035       0
#XS Ineff= 2 , 0
       0    -1.2  175.64       7       0  175.84
Permanent Ineff=
       F       F
Bank Sta=-1.2,7
XS Rating Curve= 0
Exp/Cntr=.3,.1

Type RM Length L Ch R = 1 ,1500.00 ,50,50,50
BEGIN DESCRIPTION:
30
END DESCRIPTION:
#Sta/Elev= 13
   -10.6  173.64     -.6  173.64     -.4  173.84       0  173.84       3  172.24
      13  172.24      16  173.84      19  175.34      22  176.94      23  177.94
    23.6  177.94    23.8  177.74    33.8  177.74
#Mann= 3 , 0 , 0
   -10.6    .035       0       0    .035       0      23    .035       0
#XS Ineff= 2 , 0
       0       0  173.84      23       0  177.94
Permanent Ineff=
       F       F
Bank Sta=0,23
XS Rating Curve= 0
Exp/Cntr=.3,.1

Type RM Length L Ch R = 1 ,1450.00 ,50,50,50
BEGIN DESCRIPTION:
29
END DESCRIPTION:
#Sta/Elev= 13
   -10.6   172.1     -.6   172.1     -.4   172.3       0   172.3       3   171.3
      13   171.3      16   172.3      19   173.8      22   175.4      23   176.4
    23.6   176.4    23.8   176.2    33.8   176.2
#Mann= 3 , 0 , 0
   -10.6    .035       0       0    .035       0      23    .035       0
#XS Ineff= 2 , 0
       0       0   172.3      23       0   176.4
Permanent Ineff=
       F       F
Bank Sta=0,23
XS Rating Curve= 0
Exp/Cntr=.3,.1

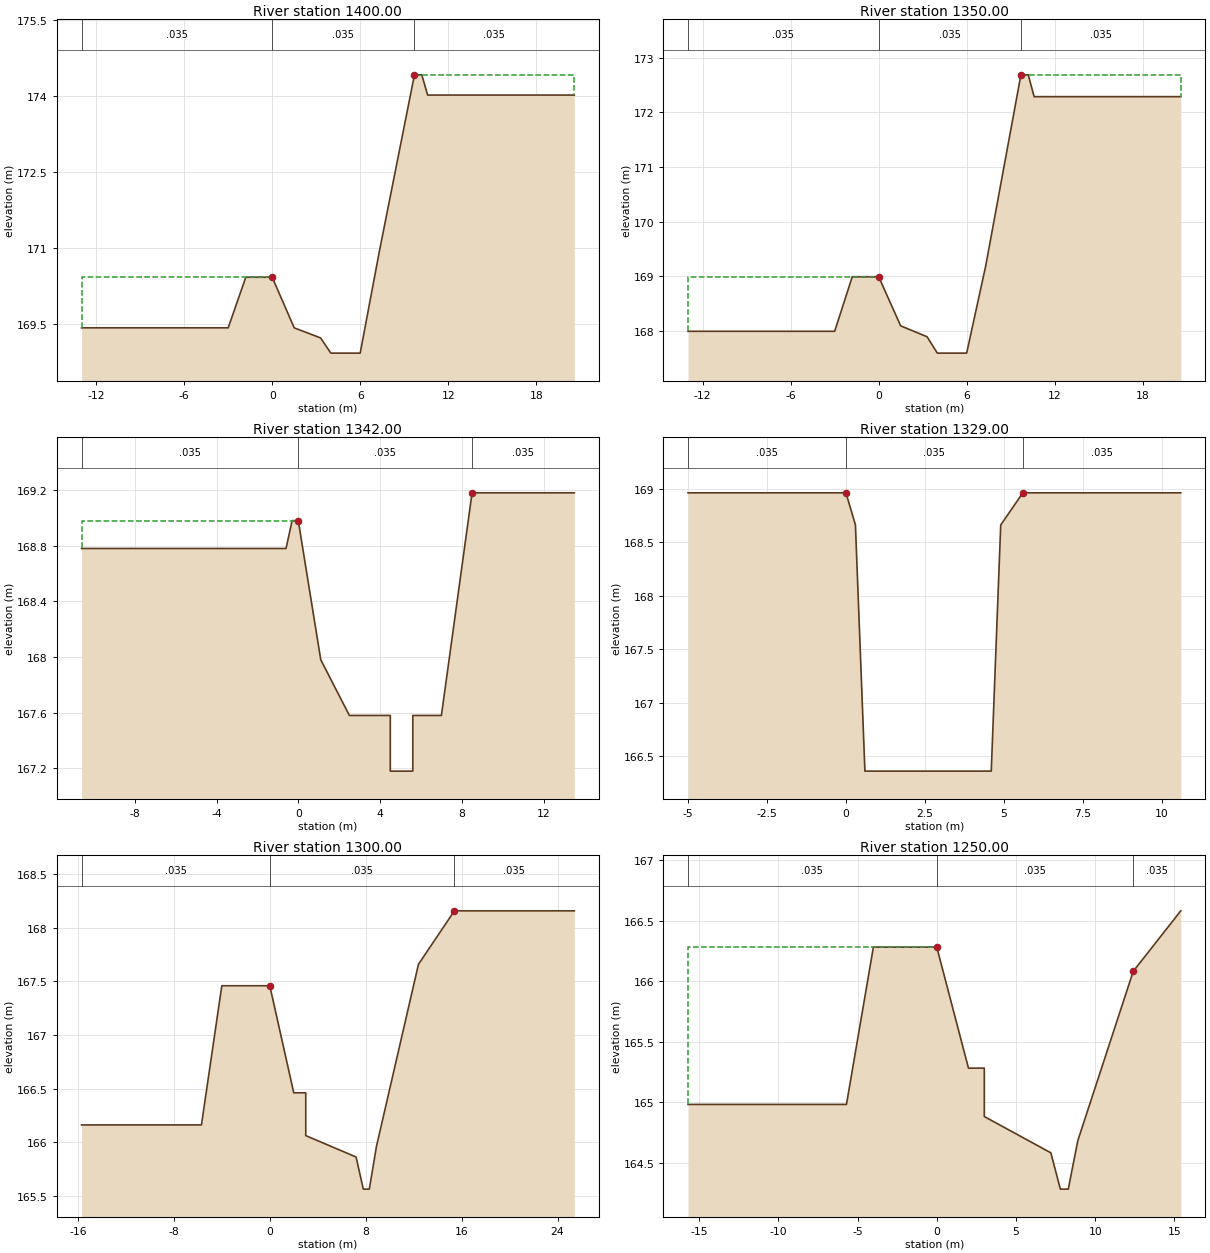
Type RM Length L Ch R = 1 ,1400.00 ,50,50,50
BEGIN DESCRIPTION:
28
END DESCRIPTION:
#Sta/Elev= 13
     -13  169.42      -3  169.42    -1.8  170.42       0  170.42     1.5  169.42
     3.3  169.22       4  168.92       6  168.92     7.3  170.92     9.7  174.42
    10.2  174.42    10.6  174.02    20.6  174.02
#Mann= 3 , 0 , 0
     -13    .035       0       0    .035       0     9.7    .035       0
#XS Ineff= 2 , 0
               0  170.42     9.7          174.42
Permanent Ineff=
       F       F
Bank Sta=0,9.7
XS Rating Curve= 0
Exp/Cntr=.3,.1

Type RM Length L Ch R = 1 ,1350.00 ,8,8,8
BEGIN DESCRIPTION:
27
END DESCRIPTION:
#Sta/Elev= 13
     -13  167.99      -3  167.99    -1.8  168.99       0  168.99     1.5  168.09
     3.3  167.89       4  167.59       6  167.59     7.3  169.19     9.7  172.69
    10.2  172.69    10.6  172.29    20.6  172.29
#Mann= 3 , 0 , 0
     -13    .035       0       0    .035       0     9.7    .035       0
#XS Ineff= 2 , 0
               0  168.99     9.7          172.69
Permanent Ineff=
       F       F
Bank Sta=0,9.7
XS Rating Curve= 0
Exp/Cntr=.3,.1

Type RM Length L Ch R = 1 ,1342.00 ,13,13,13
BEGIN DESCRIPTION:
26.042
END DESCRIPTION:
#Sta/Elev= 13
   -10.6  168.78     -.6  168.78     -.3  168.98       0  168.98     1.1  167.98
     2.5  167.58     4.5  167.58     4.5  167.18     5.6  167.18     5.6  167.58
       7  167.58     8.5  169.18    13.5  169.18
#Mann= 3 , 0 , 0
   -10.6    .035       0       0    .035       0     8.5    .035       0
#XS Ineff= 2 , 0
               0  168.98     8.5          169.18
Permanent Ineff=
       F       F
Bank Sta=0,8.5
XS Rating Curve= 0
Exp/Cntr=.3,.1

Type RM Length L Ch R = 1 ,1329.00 ,29,29,29
BEGIN DESCRIPTION:
26.029
END DESCRIPTION:
#Sta/Elev= 8
      -5  168.96       0  168.96      .3  168.66      .6  166.36     4.6  166.36
     4.9  168.66     5.6  168.96    10.6  168.96
#Mann= 3 , 0 , 0
      -5    .035       0       0    .035       0     5.6    .035       0
#XS Ineff= 2 , 0
       0       0  168.96     5.6       0  168.96
Permanent Ineff=
       F       F
Bank Sta=0,5.6
XS Rating Curve= 0
Exp/Cntr=.3,.1

Type RM Length L Ch R = 1 ,1300.00 ,50,50,50
BEGIN DESCRIPTION:
26
END DESCRIPTION:
#Sta/Elev= 14
   -15.7  166.16    -5.7  166.16      -4  167.46       0  167.46       2  166.46
       3  166.46       3  166.06     7.2  165.86     7.8  165.56     8.3  165.56
     8.9  165.96    12.4  167.66    15.4  168.16    25.4  168.16
#Mann= 3 , 0 , 0
   -15.7    .035       0       0    .035       0    15.4    .035       0
#XS Ineff= 2 , 0
       0       0  167.46    15.4       0  168.16
Permanent Ineff=
       F       F
Bank Sta=0,15.4
XS Rating Curve= 0
Exp/Cntr=.3,.1

Type RM Length L Ch R = 1 ,1250.00 ,41,41,41
BEGIN DESCRIPTION:
25
END DESCRIPTION:
#Sta/Elev= 13
   -15.7  164.98    -5.7  164.98      -4  166.28       0  166.28       2  165.28
       3  165.28       3  164.88     7.2  164.58     7.8  164.28     8.3  164.28
     8.9  164.68    12.4  166.08    15.4  166.58
#Mann= 3 , 0 , 0
   -15.7    .035       0       0    .035       0    12.4    .035       0
#XS Ineff= 2 , 0
               0  166.28    12.4          166.08
Permanent Ineff=
       F       F
Bank Sta=0,12.4
XS Rating Curve= 0
Exp/Cntr=.3,.1

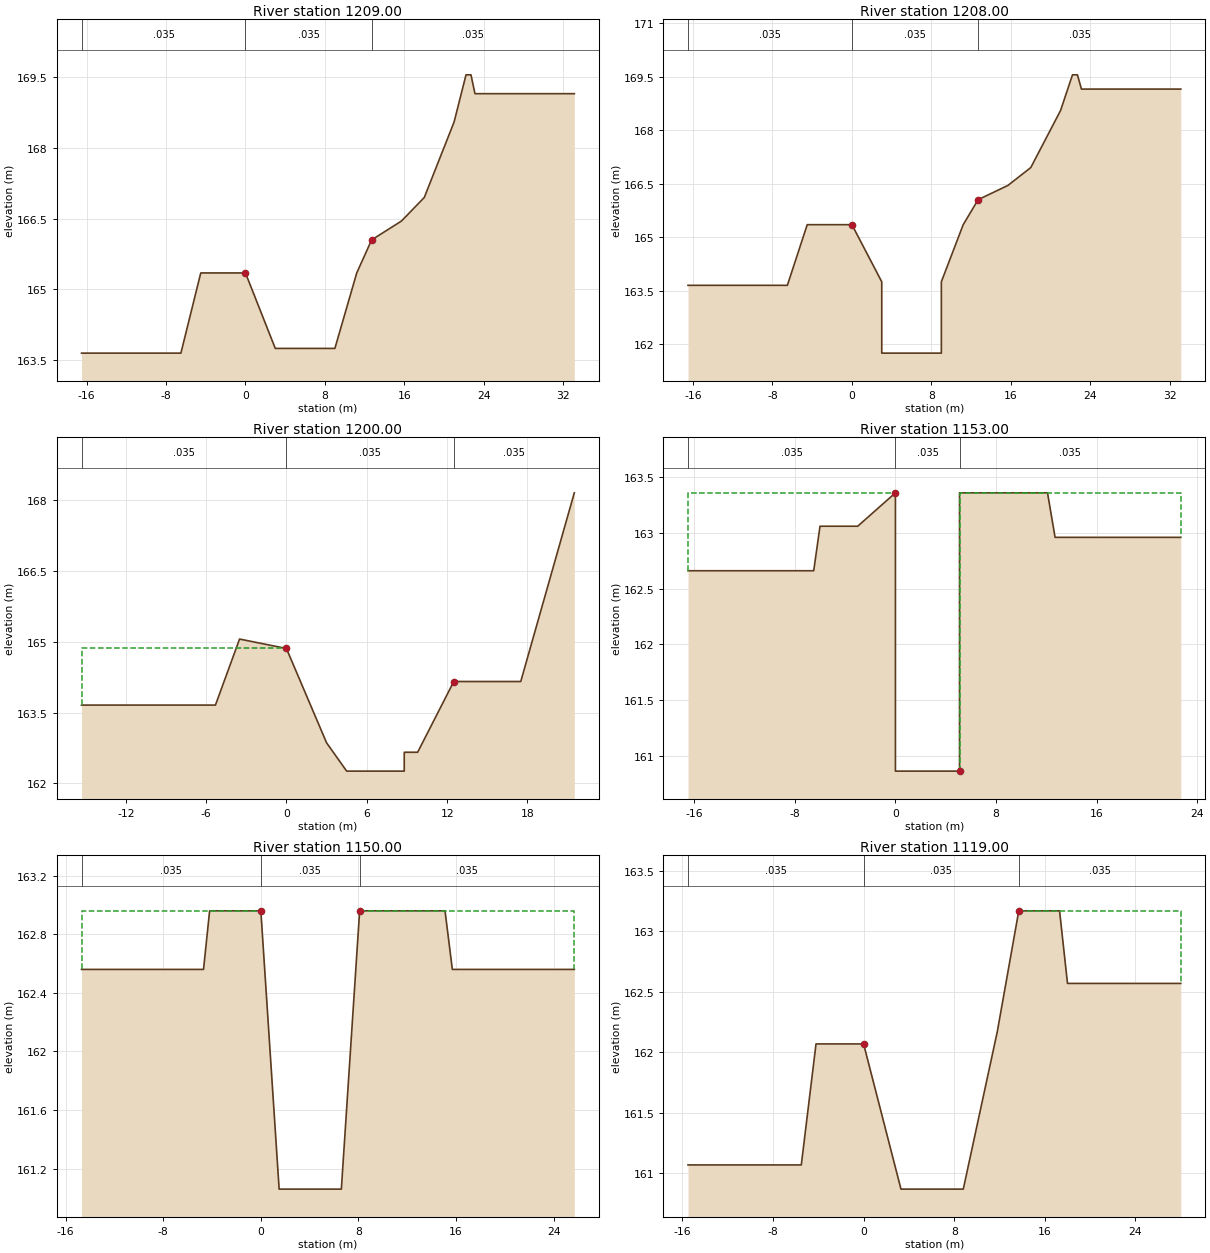
Type RM Length L Ch R = 1 ,1209.00 ,1,1,1
BEGIN DESCRIPTION:
24.009
END DESCRIPTION:
#Sta/Elev= 15
   -16.5  163.65    -6.5  163.65    -4.5  165.35       0  165.35       3  163.75
       9  163.75    11.2  165.35    12.7  166.05    15.7  166.45      18  166.95
      21  168.55    22.2  169.55    22.7  169.55    23.1  169.15    33.1  169.15
#Mann= 3 , 0 , 0
   -16.5    .035       0       0    .035       0    12.7    .035       0
#XS Ineff= 2 , 0
       0       0  165.35    12.7       0  166.05
Permanent Ineff=
       F       F
Bank Sta=0,12.7
XS Rating Curve= 0
Exp/Cntr=.3,.1

Type RM Length L Ch R = 1 ,1208.00 ,8,8,8
BEGIN DESCRIPTION:
24.008
END DESCRIPTION:
#Sta/Elev= 17
   -16.5  163.65    -6.5  163.65    -4.5  165.35       0  165.35       3  163.75
       3  161.75       9  161.75       9  163.75    11.2  165.35    12.7  166.05
    15.7  166.45      18  166.95      21  168.55    22.2  169.55    22.7  169.55
    23.1  169.15    33.1  169.15
#Mann= 3 , 0 , 0
   -16.5    .035       0       0    .035       0    12.7    .035       0
#XS Ineff= 2 , 0
       0       0  165.35    12.7       0  166.05
Permanent Ineff=
       F       F
Bank Sta=0,12.7
XS Rating Curve= 0
Exp/Cntr=.3,.1

Type RM Length L Ch R = 1 ,1200.00 ,47,47,47
BEGIN DESCRIPTION:
24
END DESCRIPTION:
#Sta/Elev= 12
   -15.3  163.66    -5.3  163.66    -3.5  165.06       0  164.86       3  162.86
     4.5  162.26     8.8  162.26     8.8  162.66     9.8  162.66    12.5  164.16
    17.5  164.16    21.5  168.16
#Mann= 3 , 0 , 0
   -15.3    .035       0       0    .035       0    12.5    .035       0
#XS Ineff= 2 , 0
               0  164.86    12.5          164.16
Permanent Ineff=
       F       F
Bank Sta=0,12.5
XS Rating Curve= 0
Exp/Cntr=.3,.1

Type RM Length L Ch R = 1 ,1153.00 ,3,3,3
BEGIN DESCRIPTION:
23.003
END DESCRIPTION:
#Sta/Elev= 11
   -16.5  162.66    -6.5  162.66      -6  163.06      -3  163.06       0  163.36
       0  160.86     5.1  160.86     5.1  163.36    12.1  163.36    12.7  162.96
    22.7  162.96
#Mann= 3 , 0 , 0
   -16.5    .035       0       0    .035       0     5.1    .035       0
#XS Ineff= 2 , 0
               0  163.36     5.1          163.36
Permanent Ineff=
       F       F
Bank Sta=0,5.1
XS Rating Curve= 0
Exp/Cntr=.3,.1

Type RM Length L Ch R = 1 ,1150.00 ,31,31,31
BEGIN DESCRIPTION:
23
END DESCRIPTION:
#Sta/Elev= 10
   -14.7  162.56    -4.7  162.56    -4.2  162.96       0  162.96     1.5  161.06
     6.6  161.06     8.1  162.96    15.1  162.96    15.7  162.56    25.7  162.56
#Mann= 3 , 0 , 0
   -14.7    .035       0       0    .035       0     8.1    .035       0
#XS Ineff= 2 , 0
               0  162.96     8.1          162.96
Permanent Ineff=
       F       F
Bank Sta=0,8.1
XS Rating Curve= 0
Exp/Cntr=.3,.1

Type RM Length L Ch R = 1 ,1119.00 ,1,1,1
BEGIN DESCRIPTION:
22.019
END DESCRIPTION:
#Sta/Elev= 11
   -15.5  161.07    -5.5  161.07    -4.2  162.07       0  162.07     3.3  160.87
     8.8  160.87    11.8  162.17    13.7  163.17    17.3  163.17      18  162.57
      28  162.57
#Mann= 3 , 0 , 0
   -15.5    .035       0       0    .035       0    13.7    .035       0
#XS Ineff= 2 , 0
       0       0  162.07    13.7       0  163.17
Permanent Ineff=
       F       F
Bank Sta=0,13.7
XS Rating Curve= 0
Exp/Cntr=.3,.1

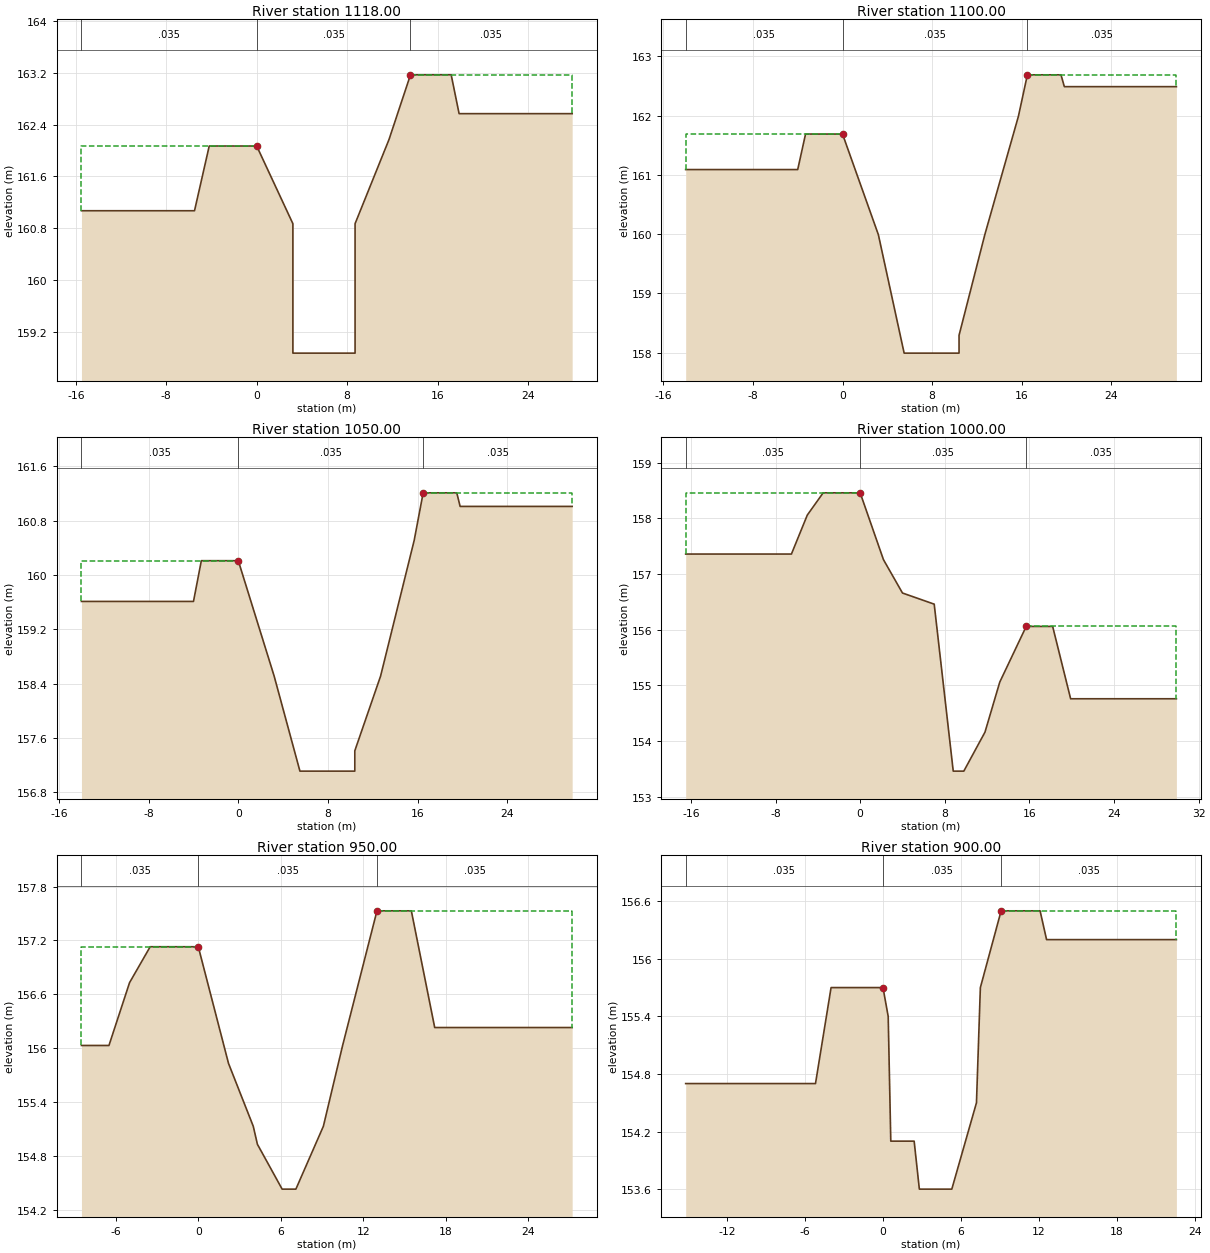
Type RM Length L Ch R = 1 ,1118.00 ,18,18,18
BEGIN DESCRIPTION:
22.018
END DESCRIPTION:
#Sta/Elev= 13
   -15.5  161.07    -5.5  161.07    -4.2  162.07       0  162.07     3.2  160.87
     3.2  158.87     8.7  158.87     8.7  160.87    11.7  162.17    13.6  163.17
    17.2  163.17    17.9  162.57    27.9  162.57
#Mann= 3 , 0 , 0
   -15.5    .035       0       0    .035       0    13.6    .035       0
#XS Ineff= 2 , 0
               0  162.07    13.6          163.17
Permanent Ineff=
       F       F
Bank Sta=0,13.6
XS Rating Curve= 0
Exp/Cntr=.3,.1

Type RM Length L Ch R = 1 ,1100.00 ,50,50,50
BEGIN DESCRIPTION:
22
END DESCRIPTION:
#Sta/Elev= 14
     -14  161.09      -4  161.09    -3.3  161.69       0  161.69     3.2  159.99
     5.5  157.99    10.4  157.99    10.4  158.29    12.7  159.99    15.7  161.99
    16.5  162.69    19.5  162.69    19.8  162.49    29.8  162.49
#Mann= 3 , 0 , 0
     -14    .035       0       0    .035       0    16.5    .035       0
#XS Ineff= 2 , 0
               0  161.69    16.5          162.69
Permanent Ineff=
       F       F
Bank Sta=0,16.5
XS Rating Curve= 0
Exp/Cntr=.3,.1

Type RM Length L Ch R = 1 ,1050.00 ,50,50,50
BEGIN DESCRIPTION:
21
END DESCRIPTION:
#Sta/Elev= 14
     -14  159.61      -4  159.61    -3.3  160.21       0  160.21     3.2  158.51
     5.5  157.11    10.4  157.11    10.4  157.41    12.7  158.51    15.7  160.51
    16.5  161.21    19.5  161.21    19.8  161.01    29.8  161.01
#Mann= 3 , 0 , 0
     -14    .035       0       0    .035       0    16.5    .035       0
#XS Ineff= 2 , 0
               0  160.21    16.5          161.21
Permanent Ineff=
       F       F
Bank Sta=0,16.5
XS Rating Curve= 0
Exp/Cntr=.3,.1

Type RM Length L Ch R = 1 ,1000.00 ,50,50,50
BEGIN DESCRIPTION:
20
END DESCRIPTION:
#Sta/Elev= 16
   -16.5  157.36    -6.5  157.36      -5  158.06    -3.5  158.46       0  158.46
     2.2  157.26       4  156.66       7  156.46     8.8  153.46     9.8  153.46
    11.8  154.16    13.2  155.06    15.7  156.06    18.2  156.06    19.9  154.76
    29.9  154.76
#Mann= 3 , 0 , 0
   -16.5    .035       0       0    .035       0    15.7    .035       0
#XS Ineff= 2 , 0
               0  158.46    15.7          156.06
Permanent Ineff=
       F       F
Bank Sta=0,15.7
XS Rating Curve= 0
Exp/Cntr=.3,.1

Type RM Length L Ch R = 1 ,950.00  ,50,50,50
BEGIN DESCRIPTION:
19
END DESCRIPTION:
#Sta/Elev= 16
    -8.5  156.03    -6.5  156.03      -5  156.73    -3.5  157.13       0  157.13
     2.2  155.83       4  155.13     4.3  154.93     6.1  154.43     7.1  154.43
     9.1  155.13    10.5  156.03      13  157.53    15.5  157.53    17.2  156.23
    27.2  156.23
#Mann= 3 , 0 , 0
    -8.5    .035       0       0    .035       0      13    .035       0
#XS Ineff= 2 , 0
               0  157.13      13          157.53
Permanent Ineff=
       F       F
Bank Sta=0,13
XS Rating Curve= 0
Exp/Cntr=.3,.1

Type RM Length L Ch R = 1 ,900.00  ,10,10,10
BEGIN DESCRIPTION:
18
END DESCRIPTION:
#Sta/Elev= 15
   -15.2   154.7    -5.2   154.7      -4   155.7       0   155.7      .4   155.4
      .6   154.1     2.4   154.1     2.8   153.6     5.3   153.6     7.2   154.5
     7.5   155.7     9.1   156.5    12.1   156.5    12.6   156.2    22.6   156.2
#Mann= 3 , 0 , 0
   -15.2    .035       0       0    .035       0     9.1    .035       0
#XS Ineff= 2 , 0
       0       0   155.7     9.1       0   156.5
Permanent Ineff=
       F       F
Bank Sta=0,9.1
XS Rating Curve= 0
Exp/Cntr=.3,.1

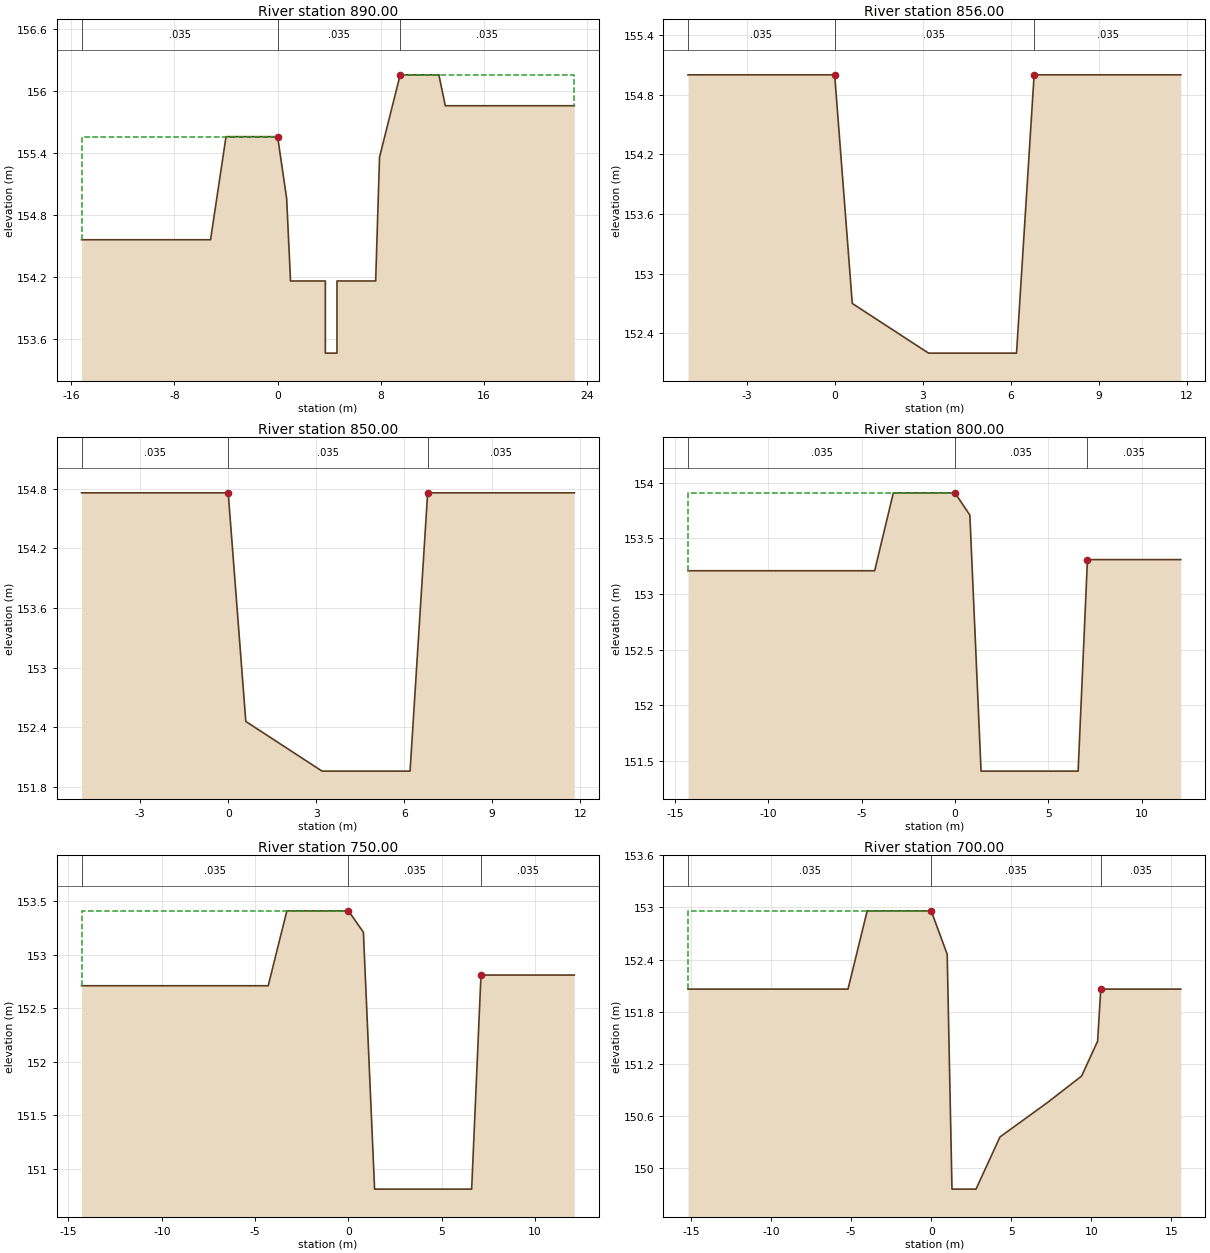
Type RM Length L Ch R = 1 ,890.00  ,34,34,34
BEGIN DESCRIPTION:
17.04
END DESCRIPTION:
#Sta/Elev= 16
   -15.2  154.56    -5.2  154.56      -4  155.56       0  155.56      .7  154.96
       1  154.16     3.7  154.16     3.7  153.46     4.6  153.46     4.6  154.16
     7.6  154.16     7.9  155.36     9.5  156.16    12.5  156.16      13  155.86
      23  155.86
#Mann= 3 , 0 , 0
   -15.2    .035       0       0    .035       0     9.5    .035       0
#XS Ineff= 2 , 0
               0  155.56     9.5          156.16
Permanent Ineff=
       F       F
Bank Sta=0,9.5
XS Rating Curve= 0
Exp/Cntr=.3,.1

Type RM Length L Ch R = 1 ,856.00  ,6,6,6
BEGIN DESCRIPTION:
17.006
END DESCRIPTION:
#Sta/Elev= 7
      -5     155       0     155      .6   152.7     3.2   152.2     6.2   152.2
     6.8     155    11.8     155
#Mann= 3 , 0 , 0
      -5    .035       0       0    .035       0     6.8    .035       0
#XS Ineff= 2 , 0
               0     155     6.8             155
Permanent Ineff=
       F       F
Bank Sta=0,6.8
XS Rating Curve= 0
Exp/Cntr=.3,.1

Type RM Length L Ch R = 1 ,850.00  ,50,50,50
BEGIN DESCRIPTION:
17
END DESCRIPTION:
#Sta/Elev= 7
      -5  154.76       0  154.76      .6  152.46     3.2  151.96     6.2  151.96
     6.8  154.76    11.8  154.76
#Mann= 3 , 0 , 0
      -5    .035       0       0    .035       0     6.8    .035       0
#XS Ineff= 2 , 0
               0  154.76     6.8          154.76
Permanent Ineff=
       F       F
Bank Sta=0,6.8
XS Rating Curve= 0
Exp/Cntr=.3,.1

Type RM Length L Ch R = 1 ,800.00  ,50,50,50
BEGIN DESCRIPTION:
16
END DESCRIPTION:
#Sta/Elev= 10
   -14.3  153.21    -4.3  153.21    -3.3  153.91    -1.3  153.91       0  153.91
      .8  153.71     1.4  151.41     6.6  151.41     7.1  153.31    12.1  153.31
#Mann= 3 , 0 , 0
   -14.3    .035       0       0    .035       0     7.1    .035       0
#XS Ineff= 2 , 0
               0  153.91     7.1          153.31
Permanent Ineff=
       F       F
Bank Sta=0,7.1
XS Rating Curve= 0
Exp/Cntr=.3,.1

Type RM Length L Ch R = 1 ,750.00  ,50,50,50
BEGIN DESCRIPTION:
15
END DESCRIPTION:
#Sta/Elev= 10
   -14.3  152.71    -4.3  152.71    -3.3  153.41    -1.3  153.41       0  153.41
      .8  153.21     1.4  150.81     6.6  150.81     7.1  152.81    12.1  152.81
#Mann= 3 , 0 , 0
   -14.3    .035       0       0    .035       0     7.1    .035       0
#XS Ineff= 2 , 0
               0  153.41     7.1          152.81
Permanent Ineff=
       F       F
Bank Sta=0,7.1
XS Rating Curve= 0
Exp/Cntr=.3,.1

Type RM Length L Ch R = 1 ,700.00  ,18,18,18
BEGIN DESCRIPTION:
14
END DESCRIPTION:
#Sta/Elev= 13
   -15.2  152.06    -5.2  152.06      -4  152.96       0  152.96       1  152.46
     1.3  149.76     2.8  149.76     4.3  150.36     7.3  150.76     9.4  151.06
    10.4  151.46    10.6  152.06    15.6  152.06
#Mann= 3 , 0 , 0
   -15.2    .035       0       0    .035       0    10.6    .035       0
#XS Ineff= 2 , 0
               0  152.96    10.6          152.06
Permanent Ineff=
       F       F
Bank Sta=0,10.6
XS Rating Curve= 0
Exp/Cntr=.3,.1

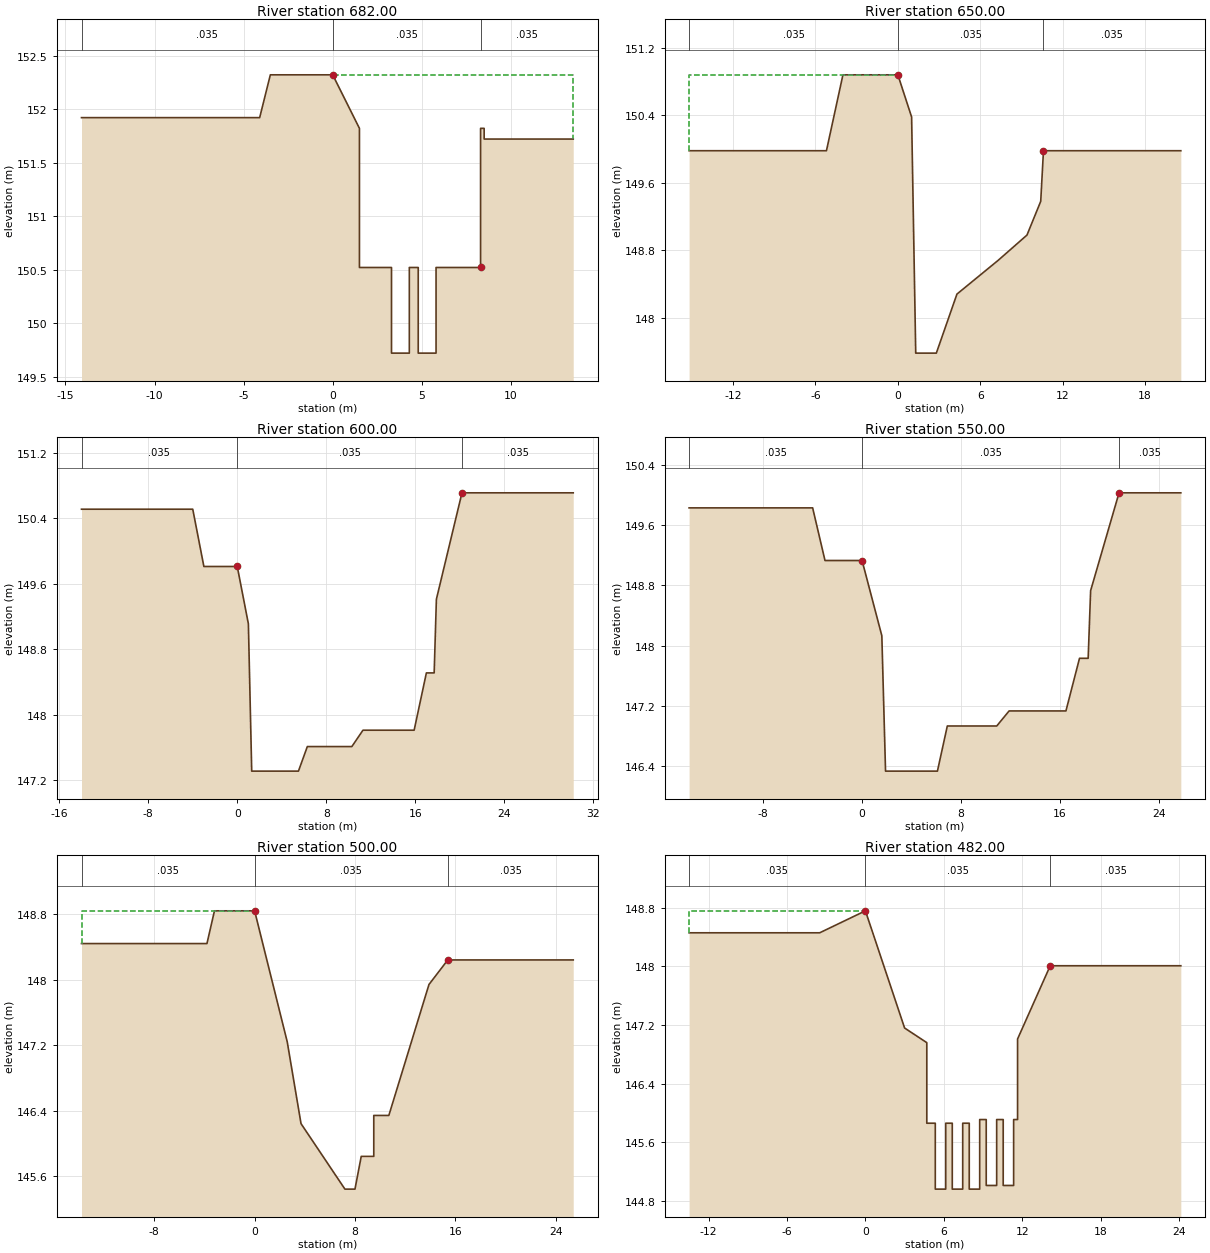
Type RM Length L Ch R = 1 ,682.00  ,32,32,32
BEGIN DESCRIPTION:
13.032
END DESCRIPTION:
#Sta/Elev= 19
   -14.1  151.92    -4.1  151.92    -3.5  152.32       0  152.32     1.5  151.82
     1.5  150.52     3.3  150.52     3.3  149.72     4.3  149.72     4.3  150.52
     4.8  150.52     4.8  149.72     5.8  149.72     5.8  150.52     8.3  150.52
     8.3  151.82     8.5  151.82     8.5  151.72    13.5  151.72
#Mann= 3 , 0 , 0
   -14.1    .035       0       0    .035       0     8.3    .035       0
#XS Ineff= 2 , 0
       0       0  152.32     8.3       0  150.52
Permanent Ineff=
       F       F
Bank Sta=0,8.3
XS Rating Curve= 0
Exp/Cntr=.3,.1

Type RM Length L Ch R = 1 ,650.00  ,50,50,50
BEGIN DESCRIPTION:
13
END DESCRIPTION:
#Sta/Elev= 13
   -15.2  149.98    -5.2  149.98      -4  150.88       0  150.88       1  150.38
     1.3  147.58     2.8  147.58     4.3  148.28     7.3  148.68     9.4  148.98
    10.4  149.38    10.6  149.98    20.6  149.98
#Mann= 3 , 0 , 0
   -15.2    .035       0       0    .035       0    10.6    .035       0
#XS Ineff= 2 , 0
               0  150.88    10.6          149.98
Permanent Ineff=
       F       F
Bank Sta=0,10.6
XS Rating Curve= 0
Exp/Cntr=.3,.1

Type RM Length L Ch R = 1 ,600.00  ,50,50,50
BEGIN DESCRIPTION:
12
END DESCRIPTION:
#Sta/Elev= 16
     -14  150.51      -4  150.51      -3  149.81       0  149.81       1  149.11
     1.3  147.31     5.5  147.31     6.3  147.61    10.3  147.61    11.3  147.81
    15.9  147.81      17  148.51    17.7  148.51    17.9  149.41    20.2  150.71
    30.2  150.71
#Mann= 3 , 0 , 0
     -14    .035       0       0    .035       0    20.2    .035       0
#XS Ineff= 2 , 0
       0       0  149.81    20.2       0  150.71
Permanent Ineff=
       F       F
Bank Sta=0,20.2
XS Rating Curve= 0
Exp/Cntr=.3,.1

Type RM Length L Ch R = 1 ,550.00  ,50,50,50
BEGIN DESCRIPTION:
11
END DESCRIPTION:
#Sta/Elev= 16
     -14  149.83      -4  149.83      -3  149.13       0  149.13     1.6  148.13
     1.9  146.33     6.1  146.33     6.9  146.93    10.9  146.93    11.9  147.13
    16.5  147.13    17.6  147.83    18.3  147.83    18.5  148.73    20.8  150.03
    25.8  150.03
#Mann= 3 , 0 , 0
     -14    .035       0       0    .035       0    20.8    .035       0
#XS Ineff= 2 , 0
       0       0  149.13    20.8       0  150.03
Permanent Ineff=
       F       F
Bank Sta=0,20.8
XS Rating Curve= 0
Exp/Cntr=.3,.1

Type RM Length L Ch R = 1 ,500.00  ,18,18,18
BEGIN DESCRIPTION:
10
END DESCRIPTION:
#Sta/Elev= 15
   -13.8  148.44    -3.8  148.44    -3.2  148.84       0  148.84     2.6  147.24
     3.7  146.24     7.2  145.44       8  145.44     8.5  145.84     9.5  145.84
     9.5  146.34    10.7  146.34    13.9  147.94    15.4  148.24    25.4  148.24
#Mann= 3 , 0 , 0
   -13.8    .035       0       0    .035       0    15.4    .035       0
#XS Ineff= 2 , 0
               0  148.84    15.4          148.24
Permanent Ineff=
       F       F
Bank Sta=0,15.4
XS Rating Curve= 0
Exp/Cntr=.3,.1

Type RM Length L Ch R = 1 ,482.00  ,32,32,32
BEGIN DESCRIPTION:
9.032
END DESCRIPTION:
#Sta/Elev= 30
   -13.5  148.46    -3.5  148.46       0  148.76       3  147.16     4.7  146.96
     4.7  145.86    5.35  145.86    5.35  144.96    6.15  144.96    6.15  145.86
    6.65  145.86    6.65  144.96    7.45  144.96    7.45  145.86    7.95  145.86
    7.95  144.96    8.75  144.96    8.75  145.91    9.25  145.91    9.25  145.01
   10.05  145.01   10.05  145.91   10.55  145.91   10.55  145.01   11.35  145.01
   11.35  145.91   11.65  145.91   11.65  147.01   14.15  148.01   24.15  148.01
#Mann= 3 , 0 , 0
   -13.5    .035       0       0    .035       0   14.15    .035       0
#XS Ineff= 2 , 0
               0  148.76   14.15          148.01
Permanent Ineff=
       F       F
Bank Sta=0,14.15
XS Rating Curve= 0
Exp/Cntr=.3,.1