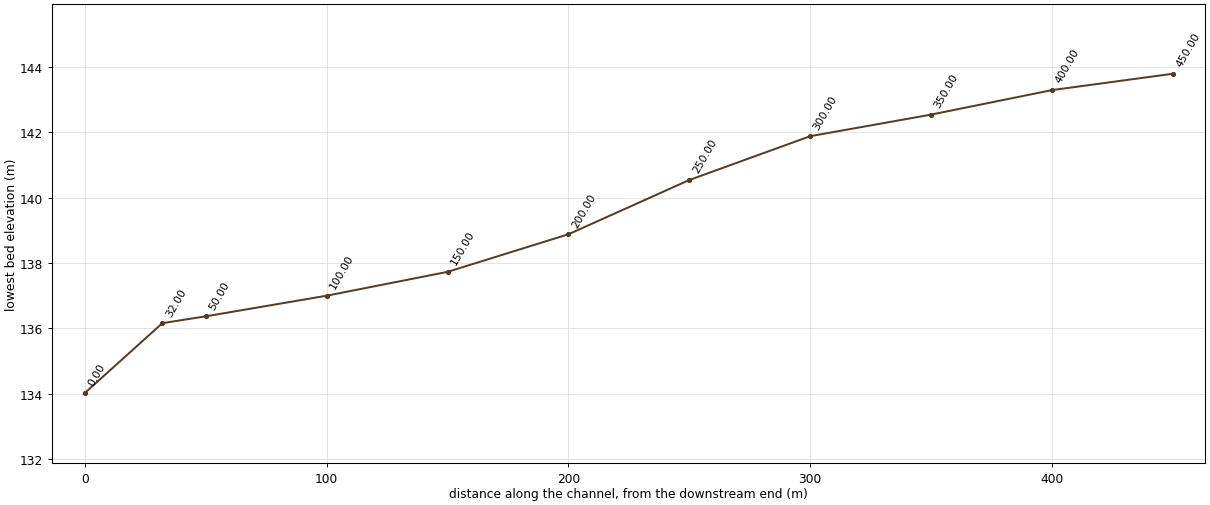
HEC-RAS study DHC.prj: doheung-ch

--- DHC.g01 (geometry) --- (continued)

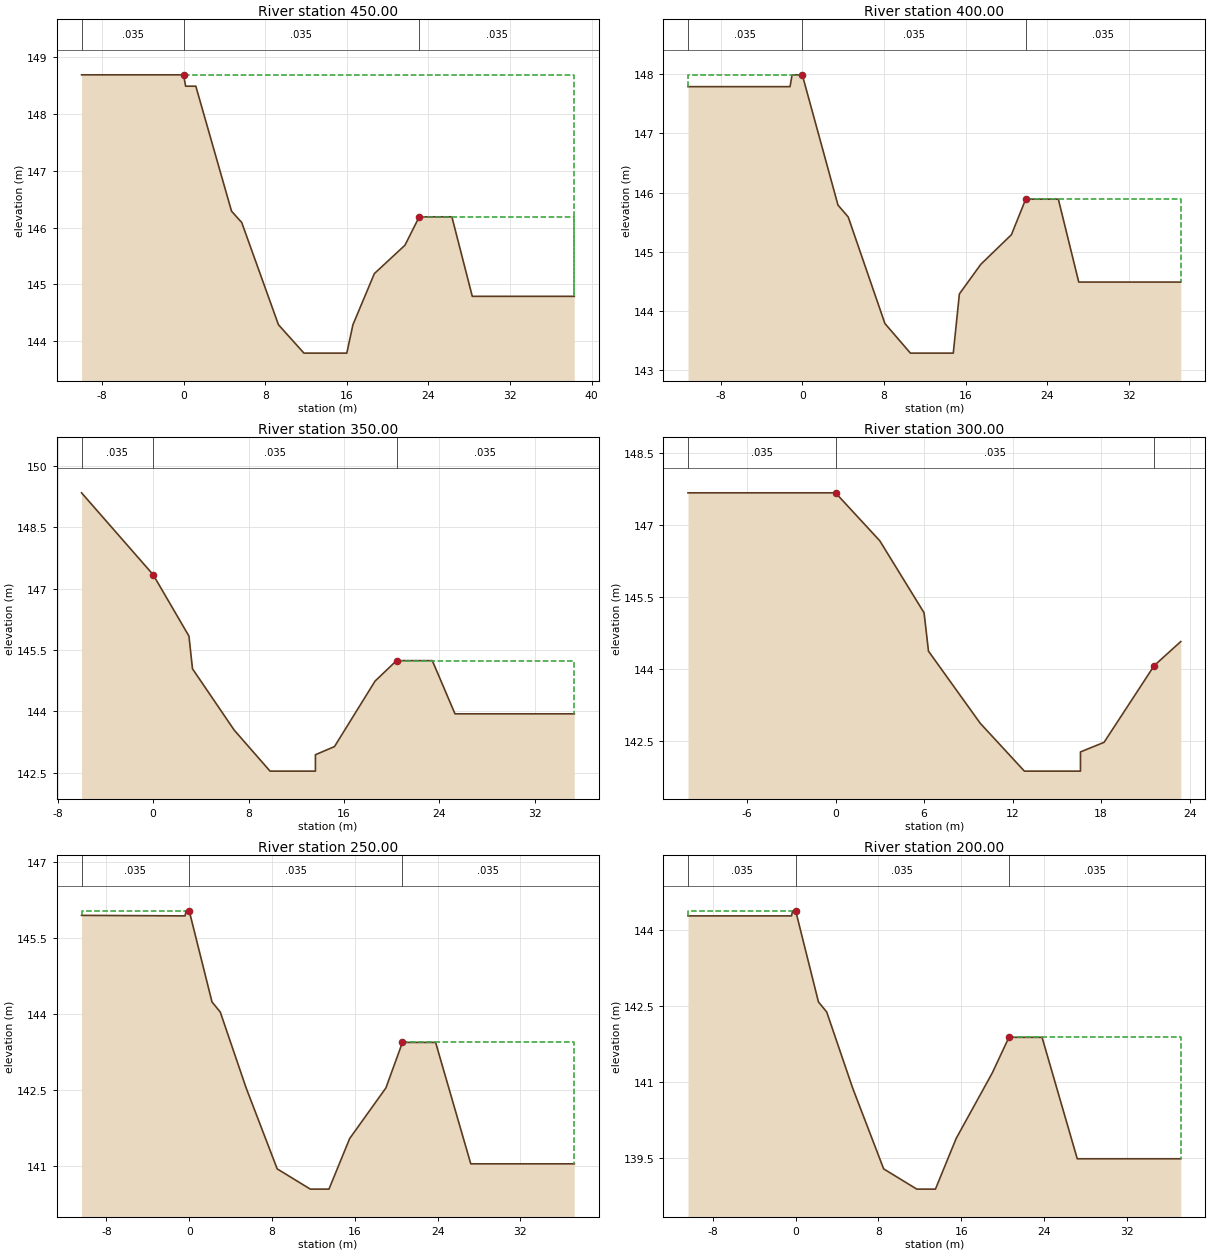
Type RM Length L Ch R = 1 ,450.00  ,50,50,50
BEGIN DESCRIPTION:
9
END DESCRIPTION:
#Sta/Elev= 16
     -10  148.69       0  148.69      .2  148.49     1.2  148.49     4.7  146.29
     5.7  146.09     9.3  144.29    11.8  143.79      16  143.79    16.6  144.29
    18.7  145.19    21.7  145.69    23.1  146.19    26.3  146.19    28.3  144.79
    38.3  144.79
#Mann= 3 , 0 , 0
     -10    .035       0       0    .035       0    23.1    .035       0
#XS Ineff= 2 , 0
       0       0  148.69    23.1       0  146.19
Permanent Ineff=
       F       F
Bank Sta=0,23.1
XS Rating Curve= 0
Exp/Cntr=.3,.1

Type RM Length L Ch R = 1 ,400.00  ,50,50,50
BEGIN DESCRIPTION:
8
END DESCRIPTION:
#Sta/Elev= 16
   -11.2  147.79    -1.2  147.79      -1  147.99       0  147.99     3.5  145.79
     4.5  145.59     8.1  143.79    10.6  143.29    14.8  143.29    15.4  144.29
    17.5  144.79    20.5  145.29    21.9  145.89    25.1  145.89    27.1  144.49
    37.1  144.49
#Mann= 3 , 0 , 0
   -11.2    .035       0       0    .035       0    21.9    .035       0
#XS Ineff= 2 , 0
               0  147.99    21.9          145.89
Permanent Ineff=
       F       F
Bank Sta=0,21.9
XS Rating Curve= 0
Exp/Cntr=.3,.1

Type RM Length L Ch R = 1 ,350.00  ,50,50,50
BEGIN DESCRIPTION:
7
END DESCRIPTION:
#Sta/Elev= 15
      -6  149.34      -3  148.34       0  147.34       3  145.84     3.3  145.04
     6.8  143.54     9.8  142.54    13.6  142.54    13.6  142.94    15.2  143.14
    18.6  144.74    20.4  145.24    23.4  145.24    25.3  143.94    35.3  143.94
#Mann= 3 , 0 , 0
      -6    .035       0       0    .035       0    20.4    .035       0
#XS Ineff= 2 , 0
               0  147.34    20.4          145.24
Permanent Ineff=
       F       F
Bank Sta=0,20.4
XS Rating Curve= 0
Exp/Cntr=.3,.1

Type RM Length L Ch R = 1 ,300.00  ,50,50,50
BEGIN DESCRIPTION:
6
END DESCRIPTION:
#Sta/Elev= 12
     -10  147.68       0  147.68       3  146.68       6  145.18     6.3  144.38
     9.8  142.88    12.8  141.88    16.6  141.88    16.6  142.28    18.2  142.48
    21.6  144.08    23.4  144.58
#Mann= 3 , 0 , 0
     -10    .035       0       0    .035       0    21.6    .035       0
#XS Ineff= 2 , 0
               0  147.68    21.6          144.08
Permanent Ineff=
       F       F
Bank Sta=0,21.6
XS Rating Curve= 0
Exp/Cntr=.3,.1

Type RM Length L Ch R = 1 ,250.00  ,50,50,50
BEGIN DESCRIPTION:
5
END DESCRIPTION:
#Sta/Elev= 16
   -10.4  145.95     -.4  145.94     -.3  146.04       0  146.04     2.2  144.24
       3  144.04     5.5  142.54     8.5  140.94    11.7  140.54    13.5  140.54
    15.5  141.54      19  142.54    20.6  143.44    23.8  143.44    27.2  141.04
    37.2  141.04
#Mann= 3 , 0 , 0
   -10.4    .035       0       0    .035       0    20.6    .035       0
#XS Ineff= 2 , 0
               0  146.04    20.6          143.44
Permanent Ineff=
       F       F
Bank Sta=0,20.6
XS Rating Curve= 0
Exp/Cntr=.3,.1

Type RM Length L Ch R = 1 ,200.00  ,50,50,50
BEGIN DESCRIPTION:
4
END DESCRIPTION:
#Sta/Elev= 16
   -10.4  144.28     -.4  144.28     -.3  144.38       0  144.38     2.2  142.58
       3  142.38     5.5  140.88     8.5  139.28    11.7  138.88    13.5  138.88
    15.5  139.88      19  141.18    20.6  141.88    23.8  141.88    27.2  139.48
    37.2  139.48
#Mann= 3 , 0 , 0
   -10.4    .035       0       0    .035       0    20.6    .035       0
#XS Ineff= 2 , 0
               0  144.38    20.6          141.88
Permanent Ineff=
       F       F
Bank Sta=0,20.6
XS Rating Curve= 0
Exp/Cntr=.3,.1

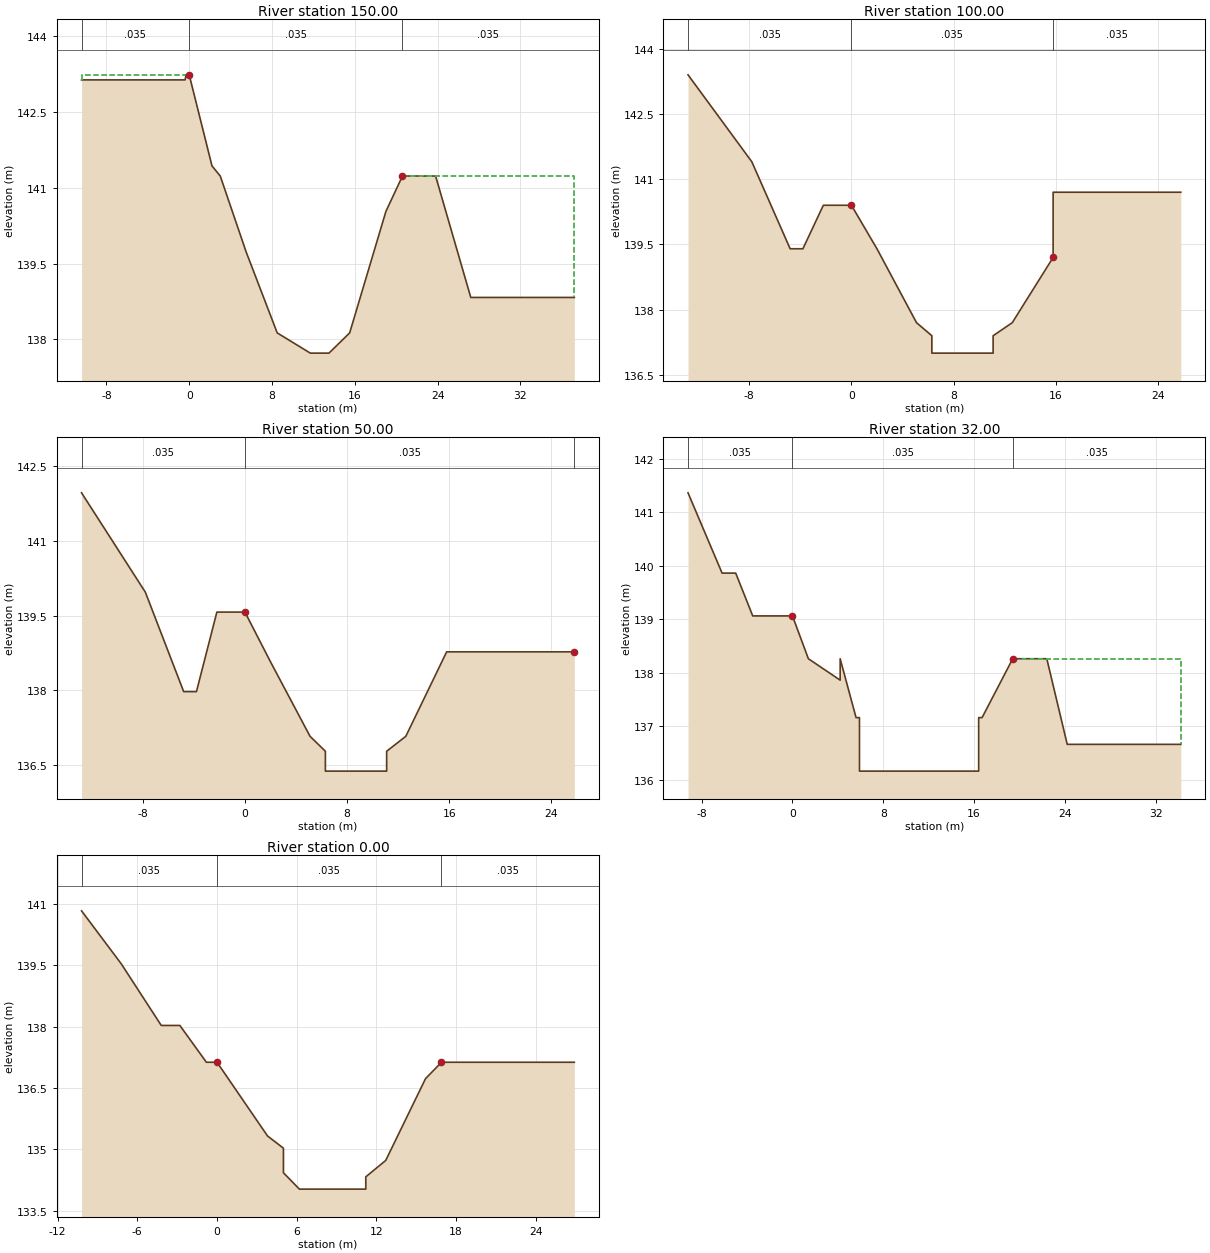
Type RM Length L Ch R = 1 ,150.00  ,50,50,50
BEGIN DESCRIPTION:
3
END DESCRIPTION:
#Sta/Elev= 16
   -10.4  143.13     -.4  143.13     -.3  143.23       0  143.23     2.2  141.43
       3  141.23     5.5  139.73     8.5  138.13    11.7  137.73    13.5  137.73
    15.5  138.13      19  140.53    20.6  141.23    23.8  141.23    27.2  138.83
    37.2  138.83
#Mann= 3 , 0 , 0
   -10.4    .035       0       0    .035       0    20.6    .035       0
#XS Ineff= 2 , 0
               0  143.23    20.6          141.23
Permanent Ineff=
       F       F
Bank Sta=0,20.6
XS Rating Curve= 0
Exp/Cntr=.3,.1

Type RM Length L Ch R = 1 ,100.00  ,50,50,50
BEGIN DESCRIPTION:
2
END DESCRIPTION:
#Sta/Elev= 16
   -12.8   143.4    -7.8   141.4    -4.8   139.4    -3.8   139.4    -2.2   140.4
       0   140.4       2   139.4     5.1   137.7     6.3   137.4     6.3     137
    11.1     137    11.1   137.4    12.6   137.7    15.8   139.2    15.8   140.7
    25.8   140.7
#Mann= 3 , 0 , 0
   -12.8    .035       0       0    .035       0    15.8    .035       0
Bank Sta=0,15.8
XS Rating Curve= 0
Exp/Cntr=.3,.1

Type RM Length L Ch R = 1 ,50.00   ,18,18,18
BEGIN DESCRIPTION:
1
END DESCRIPTION:
#Sta/Elev= 15
   -12.8  141.97    -7.8  139.97    -4.8  137.97    -3.8  137.97    -2.2  139.57
       0  139.57       2  138.57     5.1  137.07     6.3  136.77     6.3  136.37
    11.1  136.37    11.1  136.77    12.6  137.07    15.8  138.77    25.8  138.77
#Mann= 3 , 0 , 0
   -12.8    .035       0       0    .035       0    25.8    .035       0
#XS Ineff= 2 , 0
               0  139.57    25.8          138.77
Permanent Ineff=
       F       F
Bank Sta=0,25.8
XS Rating Curve= 0
Exp/Cntr=.3,.1

Type RM Length L Ch R = 1 ,32.00   ,32,32,32
BEGIN DESCRIPTION:
0.032
END DESCRIPTION:
#Sta/Elev= 18
    -9.2  141.36    -6.2  139.86      -5  139.86    -3.5  139.06       0  139.06
     1.4  138.26     4.2  137.86     4.2  138.26     5.6  137.16     5.9  137.16
     5.9  136.16    16.4  136.16    16.4  137.16    16.7  137.16    19.4  138.26
    22.4  138.26    24.2  136.66    34.2  136.66
#Mann= 3 , 0 , 0
    -9.2    .035       0       0    .035       0    19.4    .035       0
#XS Ineff= 2 , 0
               0  139.06    19.4          138.26
Permanent Ineff=
       F       F
Bank Sta=0,19.4
XS Rating Curve= 0
Exp/Cntr=.3,.1

Type RM Length L Ch R = 1 ,0.00    ,0,0,0
BEGIN DESCRIPTION:
0
END DESCRIPTION:
#Sta/Elev= 16
   -10.2  140.83    -7.2  139.53    -4.2  138.03    -2.8  138.03     -.8  137.13
       0  137.13     3.8  135.33       5  135.03       5  134.43     6.2  134.03
    11.2  134.03    11.2  134.33    12.7  134.73    15.7  136.73    16.9  137.13
    26.9  137.13
#Mann= 3 , 0 , 0
   -10.2    .035       0       0    .035       0    16.9    .035       0
#XS Ineff= 2 , 0
               0  137.13    16.9          137.13
Permanent Ineff=
       F       F
Bank Sta=0,16.9
XS Rating Curve= 0
Exp/Cntr=.3,.1

Chan Stop Cuts=-1