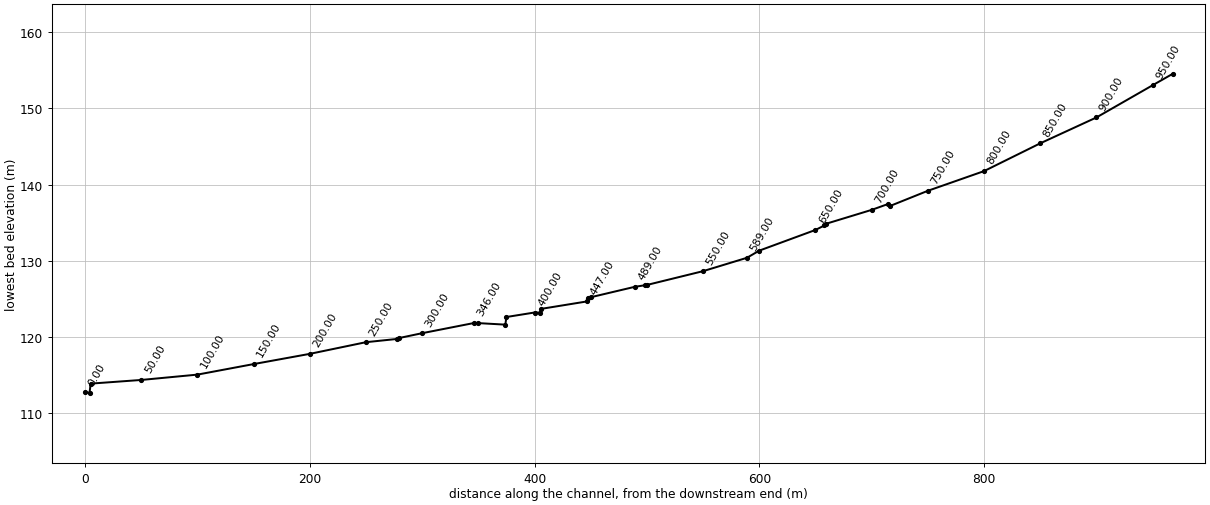
--- OHC.prj (project) ---

Proj Title=oakheyun-ch
Current Plan=p01
Default Exp/Contr=.3,.1
SI Units
Geom File=g01
Flow File=f01
Plan File=p01
Y Axis Title=Elevation
X Axis Title(PF)=Main Channel Distance
X Axis Title(XS)=Station
BEGIN DESCRIPTION:
           BACK WATER COMPUTATION
      APPLICATION OF HEC-2 BY Samju Construction Engineering
      oakheyun-ch: 10,20,30,50,80 yr
END DESCRIPTION:
DSS Export Rating Curves= 0
DSS Export Rating Curve Sorted= 0
DSS Export Volume Flow Curves= 0
DXF OffsetX= 0
DXF OffsetY= 0
DXF ScaleX= 1
DXF ScaleY= 10

--- OHC.p01 (plan) ---

Plan Title=Imported Plan 01
Version=Version 3.0.1  Mar 2001
Short Identifier=Imported Pla
Geom File=g01
Flow File=f01
Subcritical Flow
K Sum by GR= 0
Std Step Tol= 0.003
Critical Tol= 0.003
Num of Std Step Trials= 20
Max Error Tol= 0.1
Flow Tol Ratio= 0.001
Split Flow NTrial= 30
Split Flow Tol= 0.02
Split Flow Ratio= 0.02
Log Output Level= 0
Friction Slope Method= 1
Unsteady Friction Slope Method= 2
Parabolic Critical Depth
Global Vel Dist= 0 , 0 , 0
Global Log Level= 0
CheckData=True
Encroach Param=-1 ,0,0, 0
Computation Interval=1HOUR
Output Interval=1HOUR
Run HTab= 0
Run UNet= 0
Run PostProcess= 0
UNET Theta= 1
UNET ZTol= 0.02
UNET ZSATol= 0.1
UNET MxIter= 20
UNET MaxInSteps= 20
UNET DtIC= 0
UNET DtMin= 0
UNET MaxCRTS= 20
UNET WFStab= 2
UNET SFStab= 1
UNET WFX= 1
UNET SFX= 1
UNET Convert EG Bridges=-1
UNET Use Existing IB Tables=-1
Instantaneous Interval=1HOUR
Write IC File= 0
Write Velocity= 0
Write Detailed= 0

--- OHC.f01 (steady flow) ---

Flow Title=Imported Flow 01
Version=Version 3.0.1  Mar 2001
Number of Profiles= 5
Profile Names=10YR,20YR,30YR,50YR,80YR
River Rch & RM=RIVER-1,Reach-1         ,968.00
   16.56   18.24   19.22   20.46    21.6
Boundary for River Rch & Prof#=RIVER-1,Reach-1         , 1
Up Type= 0
Dn Type= 3
Dn Slope=.032
Boundary for River Rch & Prof#=RIVER-1,Reach-1         , 2
Up Type= 0
Dn Type= 3
Dn Slope=.032
Boundary for River Rch & Prof#=RIVER-1,Reach-1         , 3
Up Type= 0
Dn Type= 3
Dn Slope=.032
Boundary for River Rch & Prof#=RIVER-1,Reach-1         , 4
Up Type= 0
Dn Type= 3
Dn Slope=.032
Boundary for River Rch & Prof#=RIVER-1,Reach-1         , 5
Up Type= 0
Dn Type= 3
Dn Slope=.032
DSS Import GetInterval= 0
DSS Import GetPeak= 0
DSS Import FillOption= 0

--- OHC.g01 (geometry) ---

Geom Title=Imported Geom 01
Version=Version 3.0.1  Mar 2001

River Reach=RIVER-1         ,Reach-1
Reach XY= 2
              .5             .95              .5             .05

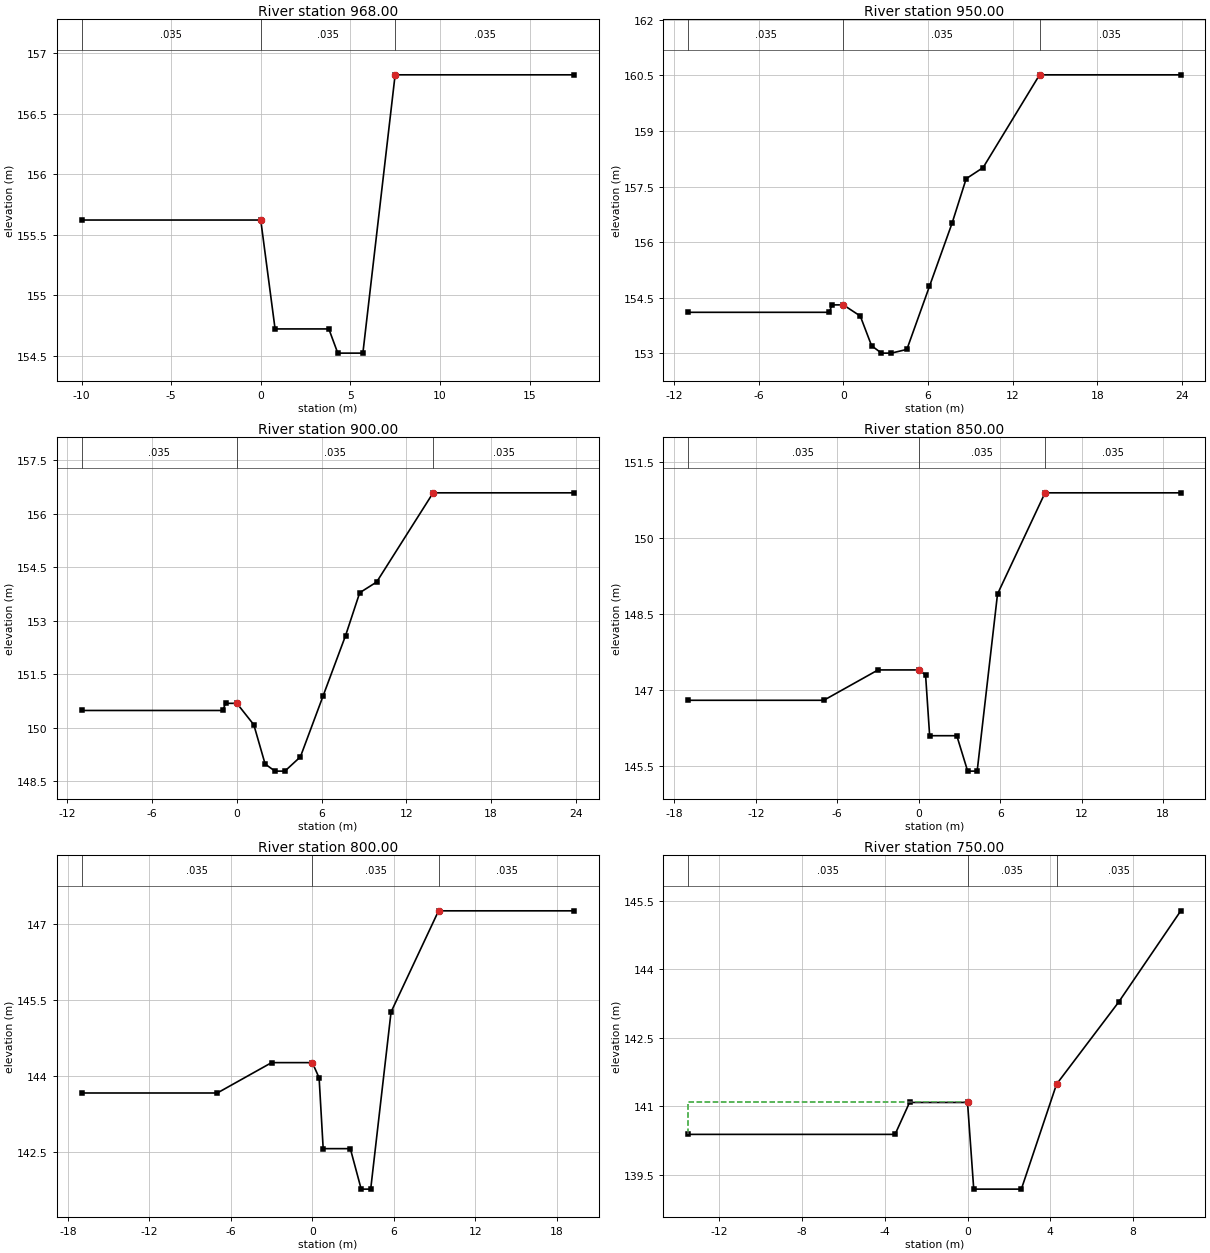
Type RM Length L Ch R = 1 ,968.00  ,18,18,18
BEGIN DESCRIPTION:
19.018
END DESCRIPTION:
#Sta/Elev= 8
     -10  155.62       0  155.62      .8  154.72     3.8  154.72     4.3  154.52
     5.7  154.52     7.5  156.82    17.5  156.82
#Mann= 3 , 0 , 0
     -10    .035       0       0    .035       0     7.5    .035       0
#XS Ineff= 2 , 0
               0  155.62     7.5          156.82
Permanent Ineff=
       F       F
Bank Sta=0,7.5
XS Rating Curve= 0
Exp/Cntr=.3,.1

Type RM Length L Ch R = 1 ,950.00  ,50,50,50
BEGIN DESCRIPTION:
19
END DESCRIPTION:
#Sta/Elev= 15
     -11  154.11      -1  154.11     -.8  154.31       0  154.31     1.2  154.01
       2  153.21     2.7  153.01     3.4  153.01     4.5  153.11     6.1  154.81
     7.7  156.51     8.7  157.71     9.9  158.01    13.9  160.51    23.9  160.51
#Mann= 3 , 0 , 0
     -11    .035       0       0    .035       0    13.9    .035       0
#XS Ineff= 2 , 0
       0       0  154.31    13.9       0  160.51
Permanent Ineff=
       F       F
Bank Sta=0,13.9
XS Rating Curve= 0
Exp/Cntr=.3,.1

Type RM Length L Ch R = 1 ,900.00  ,50,50,50
BEGIN DESCRIPTION:
18
END DESCRIPTION:
#Sta/Elev= 15
     -11  150.49      -1  150.49     -.8  150.69       0  150.69     1.2  150.09
       2  148.99     2.7  148.79     3.4  148.79     4.5  149.19     6.1  150.89
     7.7  152.59     8.7  153.79     9.9  154.09    13.9  156.59    23.9  156.59
#Mann= 3 , 0 , 0
     -11    .035       0       0    .035       0    13.9    .035       0
#XS Ineff= 2 , 0
       0       0  150.69    13.9       0  156.59
Permanent Ineff=
       F       F
Bank Sta=0,13.9
XS Rating Curve= 0
Exp/Cntr=.3,.1

Type RM Length L Ch R = 1 ,850.00  ,50,50,50
BEGIN DESCRIPTION:
17
END DESCRIPTION:
#Sta/Elev= 12
     -17   146.8      -7   146.8      -3   147.4       0   147.4      .5   147.3
      .8   146.1     2.8   146.1     3.6   145.4     4.3   145.4     5.8   148.9
     9.3   150.9    19.3   150.9
#Mann= 3 , 0 , 0
     -17    .035       0       0    .035       0     9.3    .035       0
#XS Ineff= 2 , 0
       0       0   147.4     9.3       0   150.9
Permanent Ineff=
       F       F
Bank Sta=0,9.3
XS Rating Curve= 0
Exp/Cntr=.3,.1

Type RM Length L Ch R = 1 ,800.00  ,50,50,50
BEGIN DESCRIPTION:
16
END DESCRIPTION:
#Sta/Elev= 12
     -17  143.66      -7  143.66      -3  144.26       0  144.26      .5  143.96
      .8  142.56     2.8  142.56     3.6  141.76     4.3  141.76     5.8  145.26
     9.3  147.26    19.3  147.26
#Mann= 3 , 0 , 0
     -17    .035       0       0    .035       0     9.3    .035       0
#XS Ineff= 2 , 0
       0       0  144.26     9.3       0  147.26
Permanent Ineff=
       F       F
Bank Sta=0,9.3
XS Rating Curve= 0
Exp/Cntr=.3,.1

Type RM Length L Ch R = 1 ,750.00  ,34,34,34
BEGIN DESCRIPTION:
15
END DESCRIPTION:
#Sta/Elev= 9
   -13.5  140.38    -3.5  140.38    -2.8  141.08       0  141.08      .3  139.18
     2.6  139.18     4.3  141.48     7.3  143.28    10.3  145.28
#Mann= 3 , 0 , 0
   -13.5    .035       0       0    .035       0     4.3    .035       0
#XS Ineff= 2 , 0
               0  141.08     4.3          141.48
Permanent Ineff=
       F       F
Bank Sta=0,4.3
XS Rating Curve= 0
Exp/Cntr=.3,.1

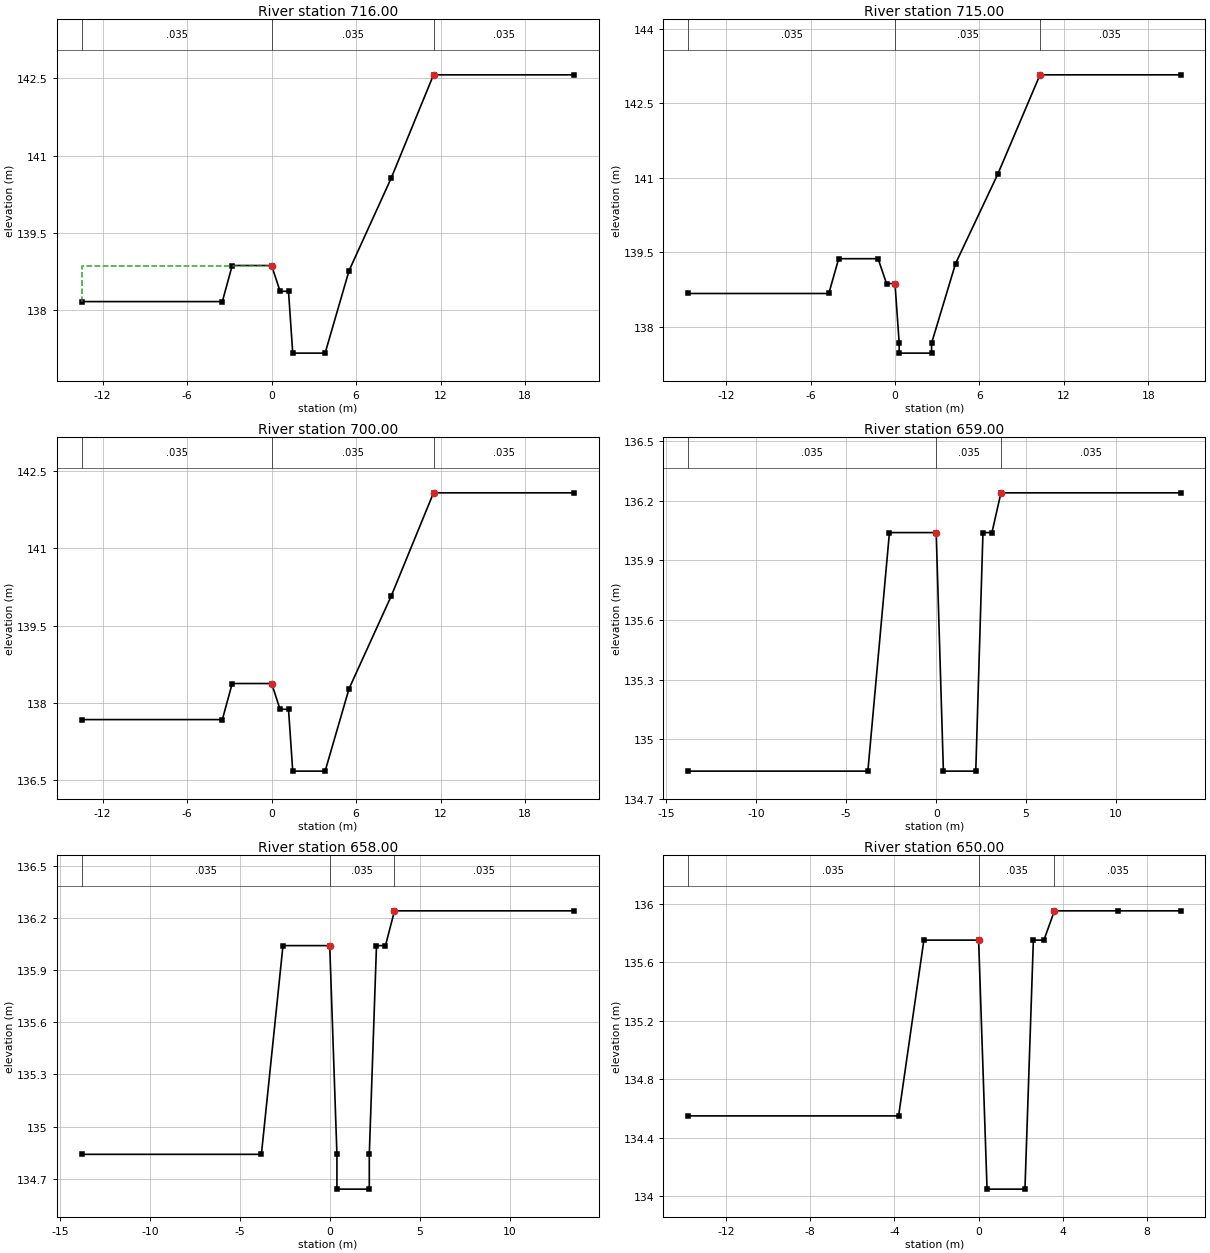
Type RM Length L Ch R = 1 ,716.00  ,1,1,1
BEGIN DESCRIPTION:
14.016
END DESCRIPTION:
#Sta/Elev= 12
   -13.5  138.17    -3.5  138.17    -2.8  138.87       0  138.87      .6  138.37
     1.2  138.37     1.5  137.17     3.8  137.17     5.5  138.77     8.5  140.57
    11.5  142.57    21.5  142.57
#Mann= 3 , 0 , 0
   -13.5    .035       0       0    .035       0    11.5    .035       0
#XS Ineff= 2 , 0
               0  138.87    11.5          142.57
Permanent Ineff=
       F       F
Bank Sta=0,11.5
XS Rating Curve= 0
Exp/Cntr=.3,.1

Type RM Length L Ch R = 1 ,715.00  ,15,15,15
BEGIN DESCRIPTION:
14.015
END DESCRIPTION:
#Sta/Elev= 14
   -14.7  138.67    -4.7  138.67      -4  139.37    -1.2  139.37     -.6  138.87
       0  138.87      .3  137.67      .3  137.47     2.6  137.47     2.6  137.67
     4.3  139.27     7.3  141.07    10.3  143.07    20.3  143.07
#Mann= 3 , 0 , 0
   -14.7    .035       0       0    .035       0    10.3    .035       0
#XS Ineff= 2 , 0
       0       0  138.87    10.3       0  143.07
Permanent Ineff=
       F       F
Bank Sta=0,10.3
XS Rating Curve= 0
Exp/Cntr=.3,.1

Type RM Length L Ch R = 1 ,700.00  ,41,41,41
BEGIN DESCRIPTION:
14
END DESCRIPTION:
#Sta/Elev= 12
   -13.5  137.68    -3.5  137.68    -2.8  138.38       0  138.38      .6  137.88
     1.2  137.88     1.5  136.68     3.8  136.68     5.5  138.28     8.5  140.08
    11.5  142.08    21.5  142.08
#Mann= 3 , 0 , 0
   -13.5    .035       0       0    .035       0    11.5    .035       0
#XS Ineff= 2 , 0
       0       0  138.38    11.5       0  142.08
Permanent Ineff=
       F       F
Bank Sta=0,11.5
XS Rating Curve= 0
Exp/Cntr=.3,.1

Type RM Length L Ch R = 1 ,659.00  ,1,1,1
BEGIN DESCRIPTION:
13.009
END DESCRIPTION:
#Sta/Elev= 10
   -13.8  134.84    -3.8  134.84    -2.6  136.04       0  136.04      .4  134.84
     2.2  134.84     2.6  136.04     3.1  136.04     3.6  136.24    13.6  136.24
#Mann= 3 , 0 , 0
   -13.8    .035       0       0    .035       0     3.6    .035       0
#XS Ineff= 2 , 0
       0       0  136.04     3.6       0  136.24
Permanent Ineff=
       F       F
Bank Sta=0,3.6
XS Rating Curve= 0
Exp/Cntr=.3,.1

Type RM Length L Ch R = 1 ,658.00  ,8,8,8
BEGIN DESCRIPTION:
13.008
END DESCRIPTION:
#Sta/Elev= 12
   -13.8  134.84    -3.8  134.84    -2.6  136.04       0  136.04      .4  134.84
      .4  134.64     2.2  134.64     2.2  134.84     2.6  136.04     3.1  136.04
     3.6  136.24    13.6  136.24
#Mann= 3 , 0 , 0
   -13.8    .035       0       0    .035       0     3.6    .035       0
#XS Ineff= 2 , 0
       0       0  136.04     3.6       0  136.24
Permanent Ineff=
       F       F
Bank Sta=0,3.6
XS Rating Curve= 0
Exp/Cntr=.3,.1

Type RM Length L Ch R = 1 ,650.00  ,50,50,50
BEGIN DESCRIPTION:
13
END DESCRIPTION:
#Sta/Elev= 11
   -13.8  134.55    -3.8  134.55    -2.6  135.75       0  135.75      .4  134.05
     2.2  134.05     2.6  135.75     3.1  135.75     3.6  135.95     6.6  135.95
     9.6  135.95
#Mann= 3 , 0 , 0
   -13.8    .035       0       0    .035       0     3.6    .035       0
#XS Ineff= 2 , 0
       0       0  135.75     3.6       0  135.95
Permanent Ineff=
       F       F
Bank Sta=0,3.6
XS Rating Curve= 0
Exp/Cntr=.3,.1

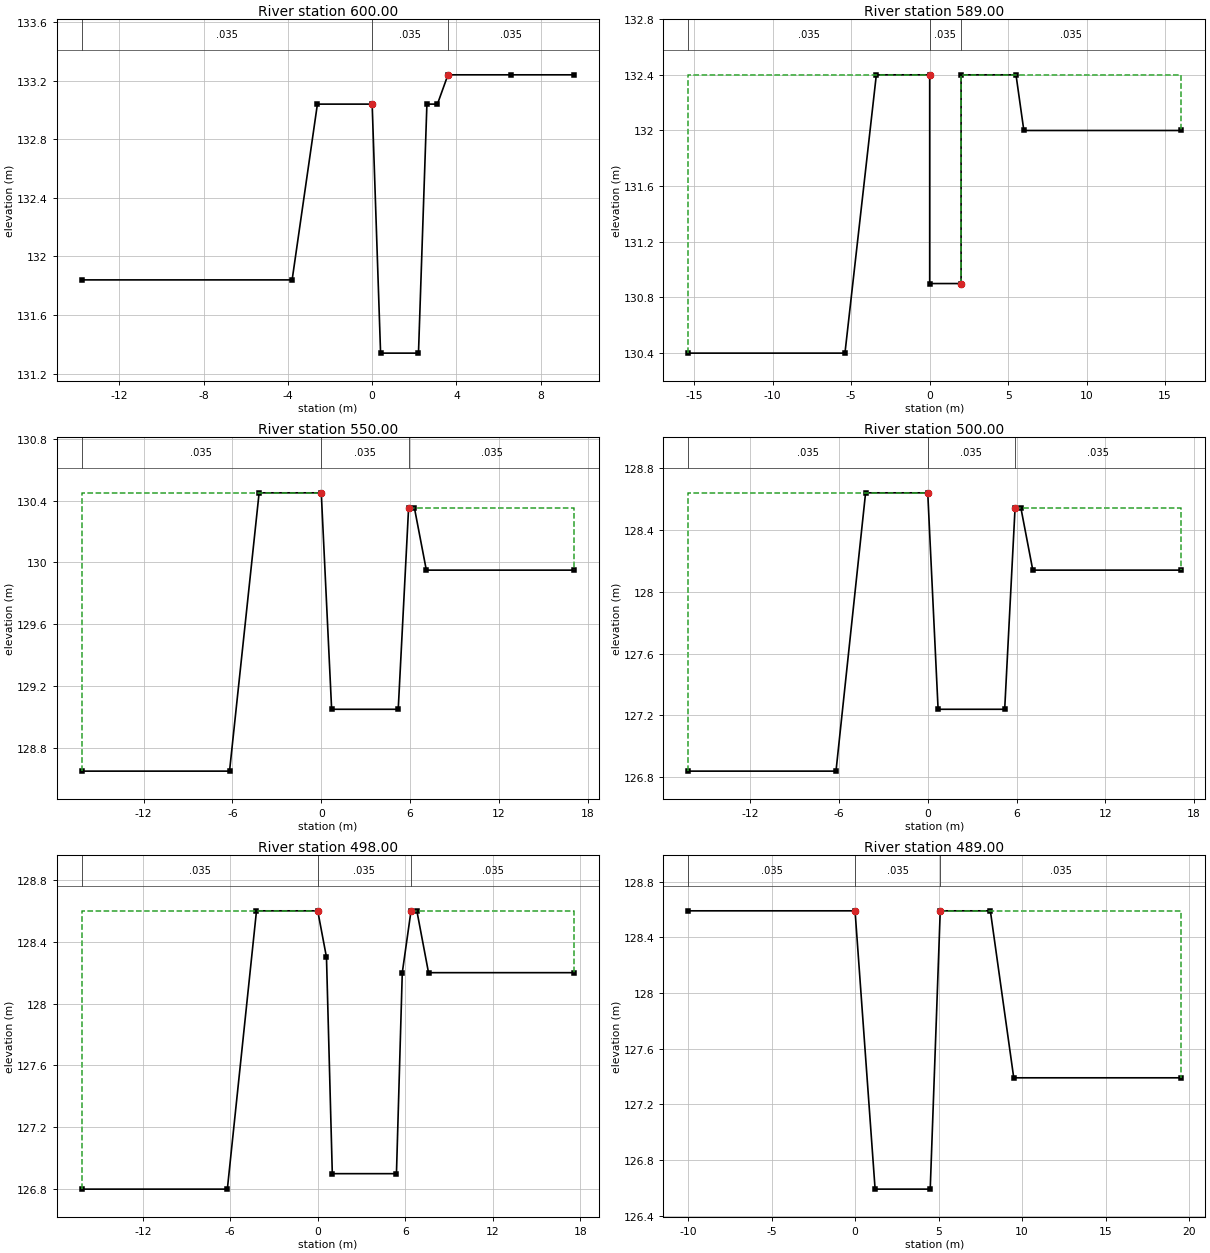
Type RM Length L Ch R = 1 ,600.00  ,11,11,11
BEGIN DESCRIPTION:
12
END DESCRIPTION:
#Sta/Elev= 11
   -13.8  131.84    -3.8  131.84    -2.6  133.04       0  133.04      .4  131.34
     2.2  131.34     2.6  133.04     3.1  133.04     3.6  133.24     6.6  133.24
     9.6  133.24
#Mann= 3 , 0 , 0
   -13.8    .035       0       0    .035       0     3.6    .035       0
#XS Ineff= 2 , 0
       0       0  133.04     3.6       0  133.24
Permanent Ineff=
       F       F
Bank Sta=0,3.6
XS Rating Curve= 0
Exp/Cntr=.3,.1

Type RM Length L Ch R = 1 ,589.00  ,39,39,39
BEGIN DESCRIPTION:
11.039
END DESCRIPTION:
#Sta/Elev= 10
   -15.4   130.4    -5.4   130.4    -3.4   132.4       0   132.4       0   130.9
       2   130.9       2   132.4     5.5   132.4       6     132      16     132
#Mann= 3 , 0 , 0
   -15.4    .035       0       0    .035       0       2    .035       0
#XS Ineff= 2 , 0
               0   132.4       2           132.4
Permanent Ineff=
       F       F
Bank Sta=0,2
XS Rating Curve= 0
Exp/Cntr=.3,.1

Type RM Length L Ch R = 1 ,550.00  ,50,50,50
BEGIN DESCRIPTION:
11
END DESCRIPTION:
#Sta/Elev= 10
   -16.2  128.65    -6.2  128.65    -4.2  130.45       0  130.45      .7  129.05
     5.2  129.05     5.9  130.35     6.3  130.35     7.1  129.95    17.1  129.95
#Mann= 3 , 0 , 0
   -16.2    .035       0       0    .035       0     5.9    .035       0
#XS Ineff= 2 , 0
               0  130.45     5.9          130.35
Permanent Ineff=
       F       F
Bank Sta=0,5.9
XS Rating Curve= 0
Exp/Cntr=.3,.1

Type RM Length L Ch R = 1 ,500.00  ,2,2,2
BEGIN DESCRIPTION:
10
END DESCRIPTION:
#Sta/Elev= 10
   -16.2  126.84    -6.2  126.84    -4.2  128.64       0  128.64      .7  127.24
     5.2  127.24     5.9  128.54     6.3  128.54     7.1  128.14    17.1  128.14
#Mann= 3 , 0 , 0
   -16.2    .035       0       0    .035       0     5.9    .035       0
#XS Ineff= 2 , 0
               0  128.64     5.9          128.54
Permanent Ineff=
       F       F
Bank Sta=0,5.9
XS Rating Curve= 0
Exp/Cntr=.3,.1

Type RM Length L Ch R = 1 ,498.00  ,9,9,9
BEGIN DESCRIPTION:
9.048
END DESCRIPTION:
#Sta/Elev= 12
   -16.2   126.8    -6.2   126.8    -4.2   128.6       0   128.6      .6   128.3
       1   126.9     5.4   126.9     5.8   128.2     6.4   128.6     6.8   128.6
     7.6   128.2    17.6   128.2
#Mann= 3 , 0 , 0
   -16.2    .035       0       0    .035       0     6.4    .035       0
#XS Ineff= 2 , 0
               0   128.6     6.4           128.6
Permanent Ineff=
       F       F
Bank Sta=0,6.4
XS Rating Curve= 0
Exp/Cntr=.3,.1

Type RM Length L Ch R = 1 ,489.00  ,39,39,39
BEGIN DESCRIPTION:
9.039
END DESCRIPTION:
#Sta/Elev= 8
     -10  128.59       0  128.59     1.2  126.59     4.5  126.59     5.1  128.59
     8.1  128.59     9.5  127.39    19.5  127.39
#Mann= 3 , 0 , 0
     -10    .035       0       0    .035       0     5.1    .035       0
#XS Ineff= 2 , 0
               0  128.59     5.1          128.59
Permanent Ineff=
       F       F
Bank Sta=0,5.1
XS Rating Curve= 0
Exp/Cntr=.3,.1

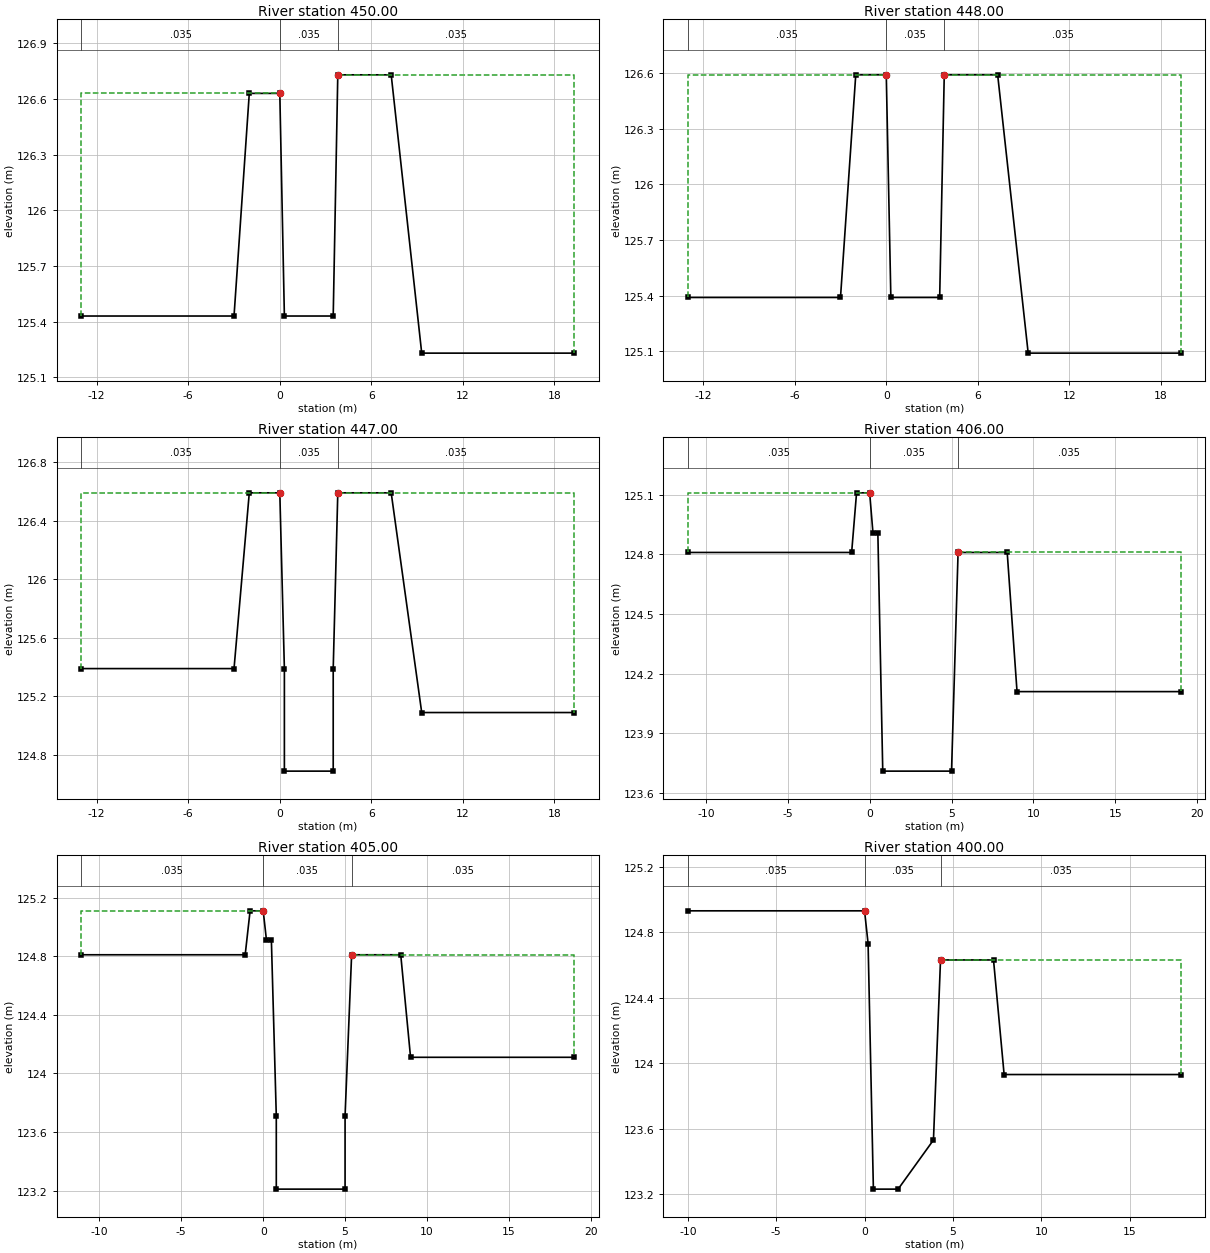
Type RM Length L Ch R = 1 ,450.00  ,2,2,2
BEGIN DESCRIPTION:
9
END DESCRIPTION:
#Sta/Elev= 10
     -13  125.43      -3  125.43      -2  126.63       0  126.63      .3  125.43
     3.5  125.43     3.8  126.73     7.3  126.73     9.3  125.23    19.3  125.23
#Mann= 3 , 0 , 0
     -13    .035       0       0    .035       0     3.8    .035       0
#XS Ineff= 2 , 0
               0  126.63     3.8          126.73
Permanent Ineff=
       F       F
Bank Sta=0,3.8
XS Rating Curve= 0
Exp/Cntr=.3,.1

Type RM Length L Ch R = 1 ,448.00  ,1,1,1
BEGIN DESCRIPTION:
8.048
END DESCRIPTION:
#Sta/Elev= 10
     -13  125.39      -3  125.39      -2  126.59       0  126.59      .3  125.39
     3.5  125.39     3.8  126.59     7.3  126.59     9.3  125.09    19.3  125.09
#Mann= 3 , 0 , 0
     -13    .035       0       0    .035       0     3.8    .035       0
#XS Ineff= 2 , 0
               0  126.59     3.8          126.59
Permanent Ineff=
       F       F
Bank Sta=0,3.8
XS Rating Curve= 0
Exp/Cntr=.3,.1

Type RM Length L Ch R = 1 ,447.00  ,41,41,41
BEGIN DESCRIPTION:
8.047
END DESCRIPTION:
#Sta/Elev= 12
     -13  125.39      -3  125.39      -2  126.59       0  126.59      .3  125.39
      .3  124.69     3.5  124.69     3.5  125.39     3.8  126.59     7.3  126.59
     9.3  125.09    19.3  125.09
#Mann= 3 , 0 , 0
     -13    .035       0       0    .035       0     3.8    .035       0
#XS Ineff= 2 , 0
               0  126.59     3.8          126.59
Permanent Ineff=
       F       F
Bank Sta=0,3.8
XS Rating Curve= 0
Exp/Cntr=.3,.1

Type RM Length L Ch R = 1 ,406.00  ,1,1,1
BEGIN DESCRIPTION:
8.006
END DESCRIPTION:
#Sta/Elev= 12
   -11.1  124.81    -1.1  124.81     -.8  125.11       0  125.11      .2  124.91
      .5  124.91      .8  123.71       5  123.71     5.4  124.81     8.4  124.81
       9  124.11      19  124.11
#Mann= 3 , 0 , 0
   -11.1    .035       0       0    .035       0     5.4    .035       0
#XS Ineff= 2 , 0
               0  125.11     5.4          124.81
Permanent Ineff=
       F       F
Bank Sta=0,5.4
XS Rating Curve= 0
Exp/Cntr=.3,.1

Type RM Length L Ch R = 1 ,405.00  ,5,5,5
BEGIN DESCRIPTION:
8.005
END DESCRIPTION:
#Sta/Elev= 14
   -11.1  124.81    -1.1  124.81     -.8  125.11       0  125.11      .2  124.91
      .5  124.91      .8  123.71      .8  123.21       5  123.21       5  123.71
     5.4  124.81     8.4  124.81       9  124.11      19  124.11
#Mann= 3 , 0 , 0
   -11.1    .035       0       0    .035       0     5.4    .035       0
#XS Ineff= 2 , 0
               0  125.11     5.4          124.81
Permanent Ineff=
       F       F
Bank Sta=0,5.4
XS Rating Curve= 0
Exp/Cntr=.3,.1

Type RM Length L Ch R = 1 ,400.00  ,25,25,25
BEGIN DESCRIPTION:
8
END DESCRIPTION:
#Sta/Elev= 10
     -10  124.93       0  124.93      .2  124.73      .5  123.23     1.9  123.23
     3.9  123.53     4.3  124.63     7.3  124.63     7.9  123.93    17.9  123.93
#Mann= 3 , 0 , 0
     -10    .035       0       0    .035       0     4.3    .035       0
#XS Ineff= 2 , 0
               0  124.93     4.3          124.63
Permanent Ineff=
       F       F
Bank Sta=0,4.3
XS Rating Curve= 0
Exp/Cntr=.3,.1

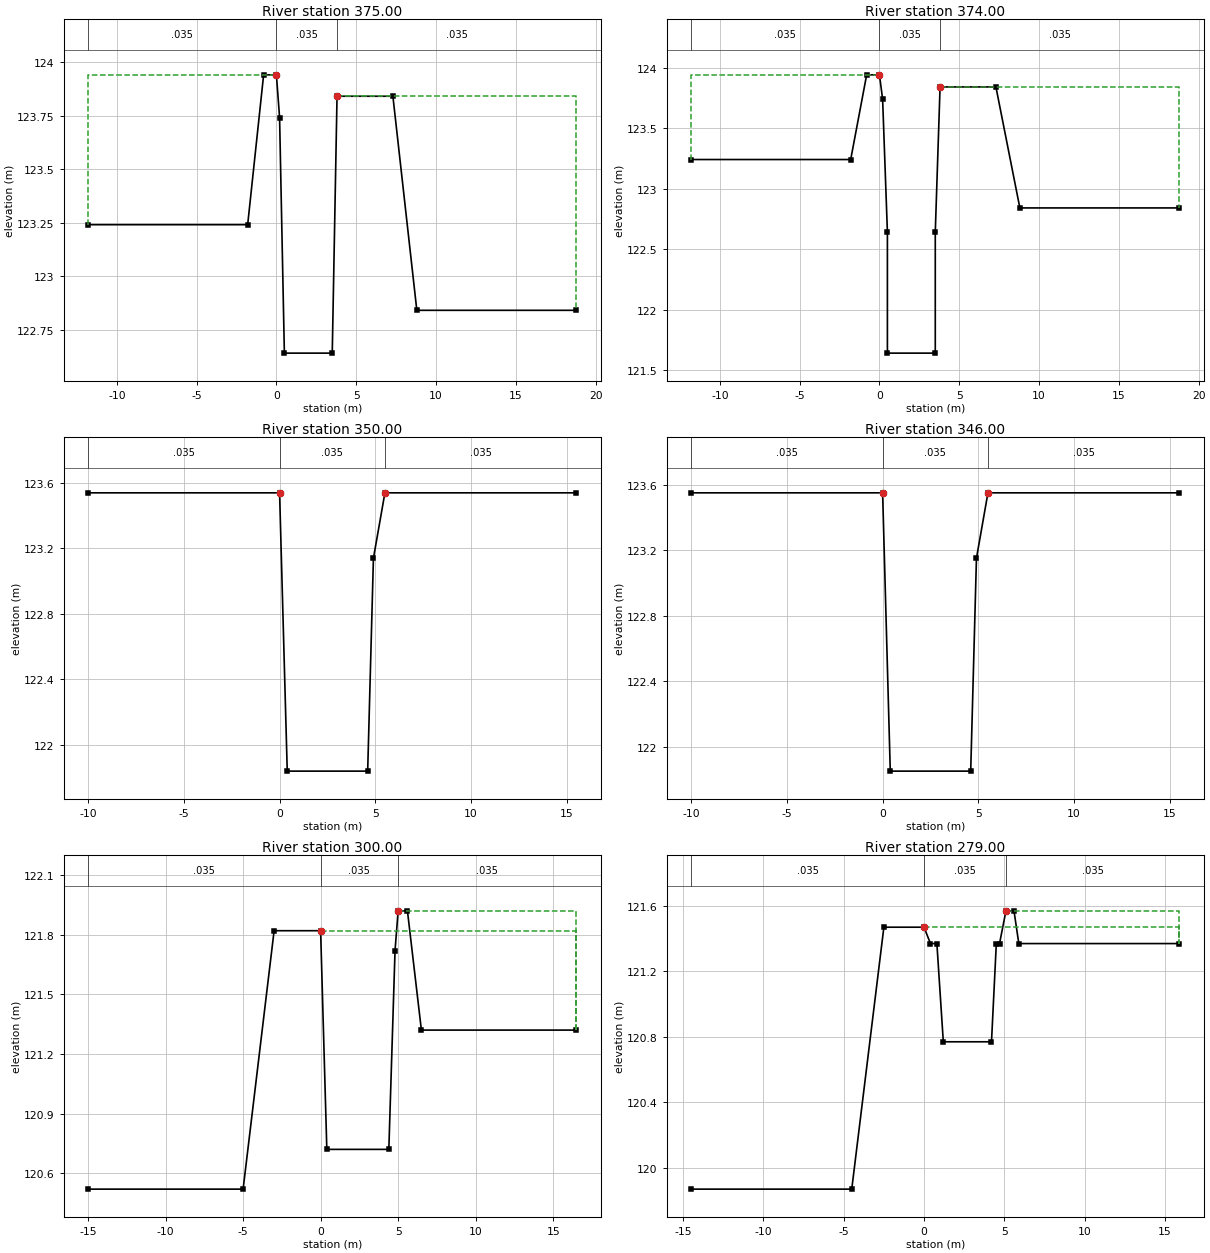
Type RM Length L Ch R = 1 ,375.00  ,1,1,1
BEGIN DESCRIPTION:
7.025
END DESCRIPTION:
#Sta/Elev= 11
   -11.8  123.24    -1.8  123.24     -.8  123.94       0  123.94      .2  123.74
      .5  122.64     3.5  122.64     3.8  123.84     7.3  123.84     8.8  122.84
    18.8  122.84
#Mann= 3 , 0 , 0
   -11.8    .035       0       0    .035       0     3.8    .035       0
#XS Ineff= 2 , 0
               0  123.94     3.8          123.84
Permanent Ineff=
       F       F
Bank Sta=0,3.8
XS Rating Curve= 0
Exp/Cntr=.3,.1

Type RM Length L Ch R = 1 ,374.00  ,24,24,24
BEGIN DESCRIPTION:
7.024
END DESCRIPTION:
#Sta/Elev= 13
   -11.8  123.24    -1.8  123.24     -.8  123.94       0  123.94      .2  123.74
      .5  122.64      .5  121.64     3.5  121.64     3.5  122.64     3.8  123.84
     7.3  123.84     8.8  122.84    18.8  122.84
#Mann= 3 , 0 , 0
   -11.8    .035       0       0    .035       0     3.8    .035       0
#XS Ineff= 2 , 0
               0  123.94     3.8          123.84
Permanent Ineff=
       F       F
Bank Sta=0,3.8
XS Rating Curve= 0
Exp/Cntr=.3,.1

Type RM Length L Ch R = 1 ,350.00  ,4,4,4
BEGIN DESCRIPTION:
7
END DESCRIPTION:
#Sta/Elev= 7
     -10  123.54       0  123.54      .4  121.84     4.6  121.84     4.9  123.14
     5.5  123.54    15.5  123.54
#Mann= 3 , 0 , 0
     -10    .035       0       0    .035       0     5.5    .035       0
#XS Ineff= 2 , 0
       0       0  123.54     5.5       0  123.54
Permanent Ineff=
       F       F
Bank Sta=0,5.5
XS Rating Curve= 0
Exp/Cntr=.3,.1

Type RM Length L Ch R = 1 ,346.00  ,46,46,46
BEGIN DESCRIPTION:
6.046
END DESCRIPTION:
#Sta/Elev= 7
     -10  123.55       0  123.55      .4  121.85     4.6  121.85     4.9  123.15
     5.5  123.55    15.5  123.55
#Mann= 3 , 0 , 0
     -10    .035       0       0    .035       0     5.5    .035       0
#XS Ineff= 2 , 0
               0  123.55     5.5          123.55
Permanent Ineff=
       F       F
Bank Sta=0,5.5
XS Rating Curve= 0
Exp/Cntr=.3,.1

Type RM Length L Ch R = 1 ,300.00  ,21,21,21
BEGIN DESCRIPTION:
6
END DESCRIPTION:
#Sta/Elev= 11
     -15  120.52      -5  120.52      -3  121.82       0  121.82      .4  120.72
     4.4  120.72     4.8  121.72       5  121.92     5.6  121.92     6.5  121.32
    16.5  121.32
#Mann= 3 , 0 , 0
     -15    .035       0       0    .035       0       5    .035       0
#XS Ineff= 2 , 0
       0       0  121.82       5       0  121.92
Permanent Ineff=
       F       F
Bank Sta=0,5
XS Rating Curve= 0
Exp/Cntr=.3,.1

Type RM Length L Ch R = 1 ,279.00  ,1,1,1
BEGIN DESCRIPTION:
5.029
END DESCRIPTION:
#Sta/Elev= 14
   -14.5  119.87    -4.5  119.87    -2.5  121.47       0  121.47      .4  121.37
      .8  121.37     1.2  120.77     4.2  120.77     4.5  121.37     4.7  121.37
     5.1  121.57     5.6  121.57     5.9  121.37    15.9  121.37
#Mann= 3 , 0 , 0
   -14.5    .035       0       0    .035       0     5.1    .035       0
#XS Ineff= 2 , 0
       0       0  121.47     5.1       0  121.57
Permanent Ineff=
       F       F
Bank Sta=0,5.1
XS Rating Curve= 0
Exp/Cntr=.3,.1

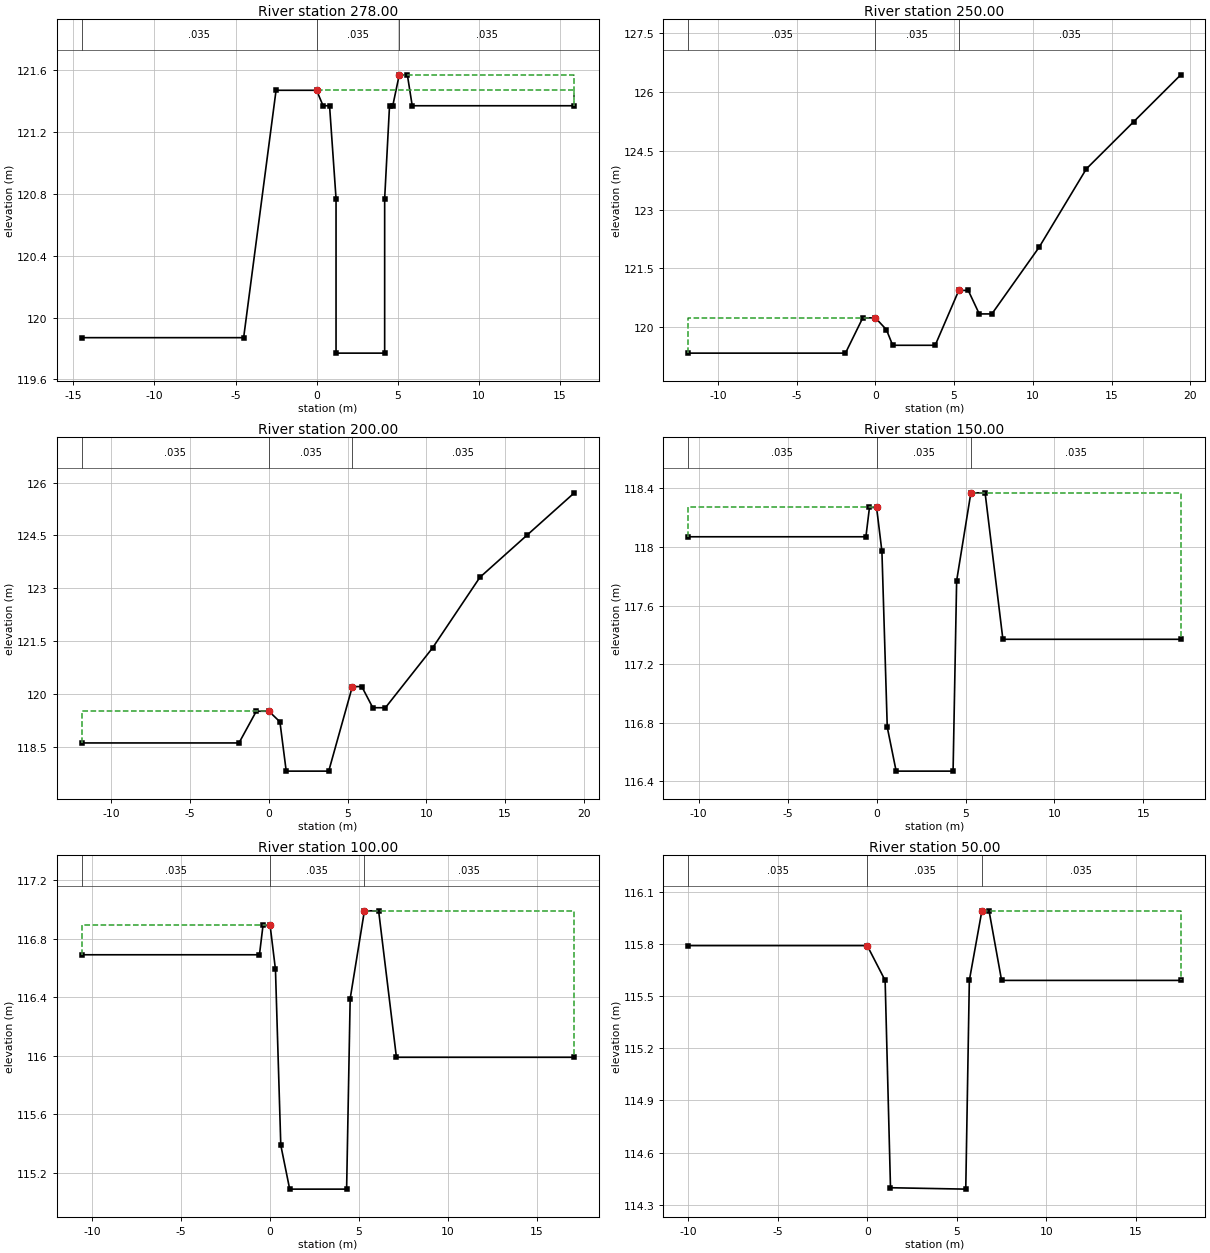
Type RM Length L Ch R = 1 ,278.00  ,28,28,28
BEGIN DESCRIPTION:
5.028
END DESCRIPTION:
#Sta/Elev= 16
   -14.5  119.87    -4.5  119.87    -2.5  121.47       0  121.47      .4  121.37
      .8  121.37     1.2  120.77     1.2  119.77     4.2  119.77     4.2  120.77
     4.5  121.37     4.7  121.37     5.1  121.57     5.6  121.57     5.9  121.37
    15.9  121.37
#Mann= 3 , 0 , 0
   -14.5    .035       0       0    .035       0     5.1    .035       0
#XS Ineff= 2 , 0
       0       0  121.47     5.1       0  121.57
Permanent Ineff=
       F       F
Bank Sta=0,5.1
XS Rating Curve= 0
Exp/Cntr=.3,.1

Type RM Length L Ch R = 1 ,250.00  ,50,50,50
BEGIN DESCRIPTION:
5
END DESCRIPTION:
#Sta/Elev= 15
   -11.9  119.34    -1.9  119.34     -.8  120.24       0  120.24      .7  119.94
     1.1  119.54     3.8  119.54     5.3  120.94     5.9  120.94     6.6  120.34
     7.4  120.34    10.4  122.04    13.4  124.04    16.4  125.24    19.4  126.44
#Mann= 3 , 0 , 0
   -11.9    .035       0       0    .035       0     5.3    .035       0
#XS Ineff= 2 , 0
               0  120.24     5.3          120.94
Permanent Ineff=
       F       F
Bank Sta=0,5.3
XS Rating Curve= 0
Exp/Cntr=.3,.1

Type RM Length L Ch R = 1 ,200.00  ,50,50,50
BEGIN DESCRIPTION:
4
END DESCRIPTION:
#Sta/Elev= 15
   -11.9  118.61    -1.9  118.61     -.8  119.51       0  119.51      .7  119.21
     1.1  117.81     3.8  117.81     5.3  120.21     5.9  120.21     6.6  119.61
     7.4  119.61    10.4  121.31    13.4  123.31    16.4  124.51    19.4  125.71
#Mann= 3 , 0 , 0
   -11.9    .035       0       0    .035       0     5.3    .035       0
#XS Ineff= 2 , 0
               0  119.51     5.3          120.21
Permanent Ineff=
       F       F
Bank Sta=0,5.3
XS Rating Curve= 0
Exp/Cntr=.3,.1

Type RM Length L Ch R = 1 ,150.00  ,50,50,50
BEGIN DESCRIPTION:
3
END DESCRIPTION:
#Sta/Elev= 13
   -10.6  118.07     -.6  118.07     -.4  118.27       0  118.27      .3  117.97
      .6  116.77     1.1  116.47     4.3  116.47     4.5  117.77     5.3  118.37
     6.1  118.37     7.1  117.37    17.1  117.37
#Mann= 3 , 0 , 0
   -10.6    .035       0       0    .035       0     5.3    .035       0
#XS Ineff= 2 , 0
               0  118.27     5.3          118.37
Permanent Ineff=
       F       F
Bank Sta=0,5.3
XS Rating Curve= 0
Exp/Cntr=.3,.1

Type RM Length L Ch R = 1 ,100.00  ,50,50,50
BEGIN DESCRIPTION:
2
END DESCRIPTION:
#Sta/Elev= 13
   -10.6  116.69     -.6  116.69     -.4  116.89       0  116.89      .3  116.59
      .6  115.39     1.1  115.09     4.3  115.09     4.5  116.39     5.3  116.99
     6.1  116.99     7.1  115.99    17.1  115.99
#Mann= 3 , 0 , 0
   -10.6    .035       0       0    .035       0     5.3    .035       0
#XS Ineff= 2 , 0
               0  116.89     5.3          116.99
Permanent Ineff=
       F       F
Bank Sta=0,5.3
XS Rating Curve= 0
Exp/Cntr=.3,.1

Type RM Length L Ch R = 1 ,50.00   ,45,45,45
BEGIN DESCRIPTION:
1
END DESCRIPTION:
#Sta/Elev= 10
     -10  115.79       0  115.79       1  115.59     1.3 114.398     5.5  114.39
     5.7  115.59     6.4  115.99     6.8  115.99     7.5  115.59    17.5  115.59
#Mann= 3 , 0 , 0
     -10    .035       0       0    .035       0     6.4    .035       0
#XS Ineff= 2 , 0
               0  115.79     6.4          115.99
Permanent Ineff=
       F       F
Bank Sta=0,6.4
XS Rating Curve= 0
Exp/Cntr=.3,.1

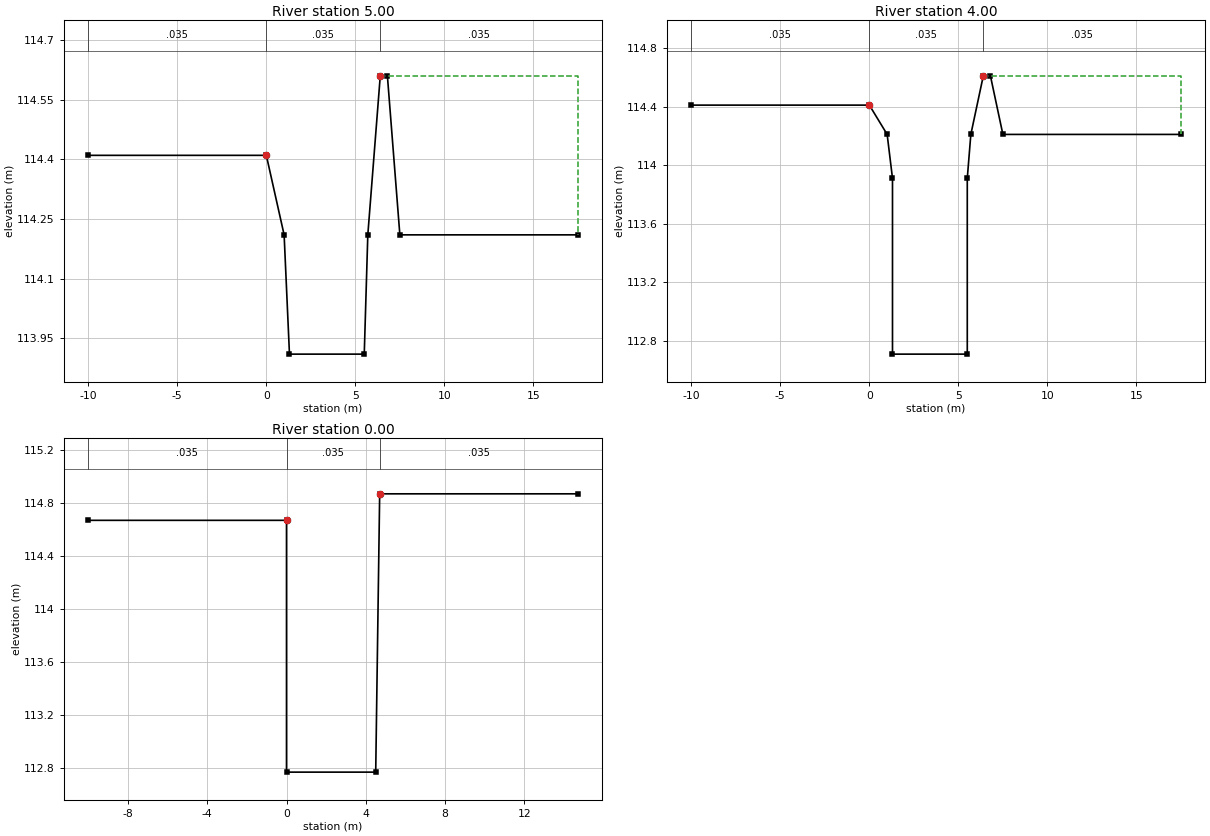
Type RM Length L Ch R = 1 ,5.00    ,1,1,1
BEGIN DESCRIPTION:
0.005
END DESCRIPTION:
#Sta/Elev= 10
     -10  114.41       0  114.41       1  114.21     1.3  113.91     5.5  113.91
     5.7  114.21     6.4  114.61     6.8  114.61     7.5  114.21    17.5  114.21
#Mann= 3 , 0 , 0
     -10    .035       0       0    .035       0     6.4    .035       0
#XS Ineff= 2 , 0
               0  114.41     6.4          114.61
Permanent Ineff=
       F       F
Bank Sta=0,6.4
XS Rating Curve= 0
Exp/Cntr=.3,.1

Type RM Length L Ch R = 1 ,4.00    ,4,4,4
BEGIN DESCRIPTION:
0.004
END DESCRIPTION:
#Sta/Elev= 12
     -10  114.41       0  114.41       1  114.21     1.3  113.91     1.3  112.71
     5.5  112.71     5.5  113.91     5.7  114.21     6.4  114.61     6.8  114.61
     7.5  114.21    17.5  114.21
#Mann= 3 , 0 , 0
     -10    .035       0       0    .035       0     6.4    .035       0
#XS Ineff= 2 , 0
               0  114.41     6.4          114.61
Permanent Ineff=
       F       F
Bank Sta=0,6.4
XS Rating Curve= 0
Exp/Cntr=.3,.1

Type RM Length L Ch R = 1 ,0.00    ,0,0,0
BEGIN DESCRIPTION:
0
END DESCRIPTION:
#Sta/Elev= 6
     -10  114.67       0  114.67       0  112.77     4.5  112.77     4.7  114.87
    14.7  114.87
#Mann= 3 , 0 , 0
     -10    .035       0       0    .035       0     4.7    .035       0
#XS Ineff= 2 , 0
               0  114.67     4.7          114.87
Permanent Ineff=
       F       F
Bank Sta=0,4.7
XS Rating Curve= 0
Exp/Cntr=.3,.1

Chan Stop Cuts=-1