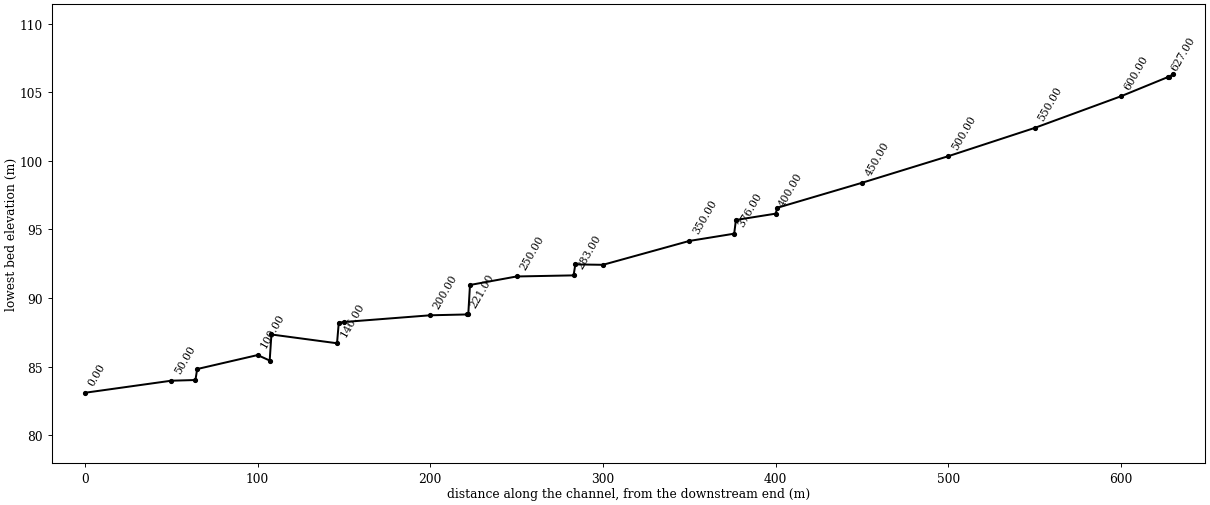
--- EHC.prj (project) ---

Proj Title=eunhyun-ch
Current Plan=p01
Default Exp/Contr=.3,.1
SI Units
Geom File=g01
Flow File=f01
Plan File=p01
Y Axis Title=Elevation
X Axis Title(PF)=Main Channel Distance
X Axis Title(XS)=Station
BEGIN DESCRIPTION:
           BACK WATER COMPUTATION
      APPLICATION OF HEC-2 BY Samju Construction Engineering
      eunhyun-ch: 10,20,30,50,80 yr
END DESCRIPTION:
DSS Export Rating Curves= 0
DSS Export Rating Curve Sorted= 0
DSS Export Volume Flow Curves= 0
DXF OffsetX= 0
DXF OffsetY= 0
DXF ScaleX= 1
DXF ScaleY= 10

--- EHC.p01 (plan) ---

Plan Title=Imported Plan 01
Version=Version 3.0.1  Mar 2001
Short Identifier=Imported Pla
Geom File=g01
Flow File=f01
Subcritical Flow
K Sum by GR= 0
Std Step Tol= 0.003
Critical Tol= 0.003
Num of Std Step Trials= 20
Max Error Tol= 0.1
Flow Tol Ratio= 0.001
Split Flow NTrial= 30
Split Flow Tol= 0.02
Split Flow Ratio= 0.02
Log Output Level= 0
Friction Slope Method= 1
Unsteady Friction Slope Method= 2
Parabolic Critical Depth
Global Vel Dist= 0 , 0 , 0
Global Log Level= 0
CheckData=True
Encroach Param=-1 ,0,0, 0
Computation Interval=1HOUR
Output Interval=1HOUR
Run HTab= 0
Run UNet= 0
Run PostProcess= 0
UNET Theta= 1
UNET ZTol= 0.02
UNET ZSATol= 0.1
UNET MxIter= 20
UNET MaxInSteps= 20
UNET DtIC= 0
UNET DtMin= 0
UNET MaxCRTS= 20
UNET WFStab= 2
UNET SFStab= 1
UNET WFX= 1
UNET SFX= 1
UNET Convert EG Bridges=-1
UNET Use Existing IB Tables=-1
Instantaneous Interval=1HOUR
Write IC File= 0
Write Velocity= 0
Write Detailed= 0

--- EHC.f01 (steady flow) ---

Flow Title=Imported Flow 01
Version=Version 3.0.1  Mar 2001
Number of Profiles= 5
Profile Names=10YR,20YR,30YR,50YR,80YR
River Rch & RM=RIVER-1,Reach-1         ,630.00
   12.61   13.89   14.63   15.58   16.44
Boundary for River Rch & Prof#=RIVER-1,Reach-1         , 1
Up Type= 0
Dn Type= 3
Dn Slope=.034
Boundary for River Rch & Prof#=RIVER-1,Reach-1         , 2
Up Type= 0
Dn Type= 3
Dn Slope=.034
Boundary for River Rch & Prof#=RIVER-1,Reach-1         , 3
Up Type= 0
Dn Type= 3
Dn Slope=.034
Boundary for River Rch & Prof#=RIVER-1,Reach-1         , 4
Up Type= 0
Dn Type= 3
Dn Slope=.034
Boundary for River Rch & Prof#=RIVER-1,Reach-1         , 5
Up Type= 0
Dn Type= 3
Dn Slope=.034
DSS Import GetInterval= 0
DSS Import GetPeak= 0
DSS Import FillOption= 0

--- EHC.g01 (geometry) ---

Geom Title=Imported Geom 01
Version=Version 3.0.1  Mar 2001

River Reach=RIVER-1         ,Reach-1
Reach XY= 2
              .5             .95              .5             .05

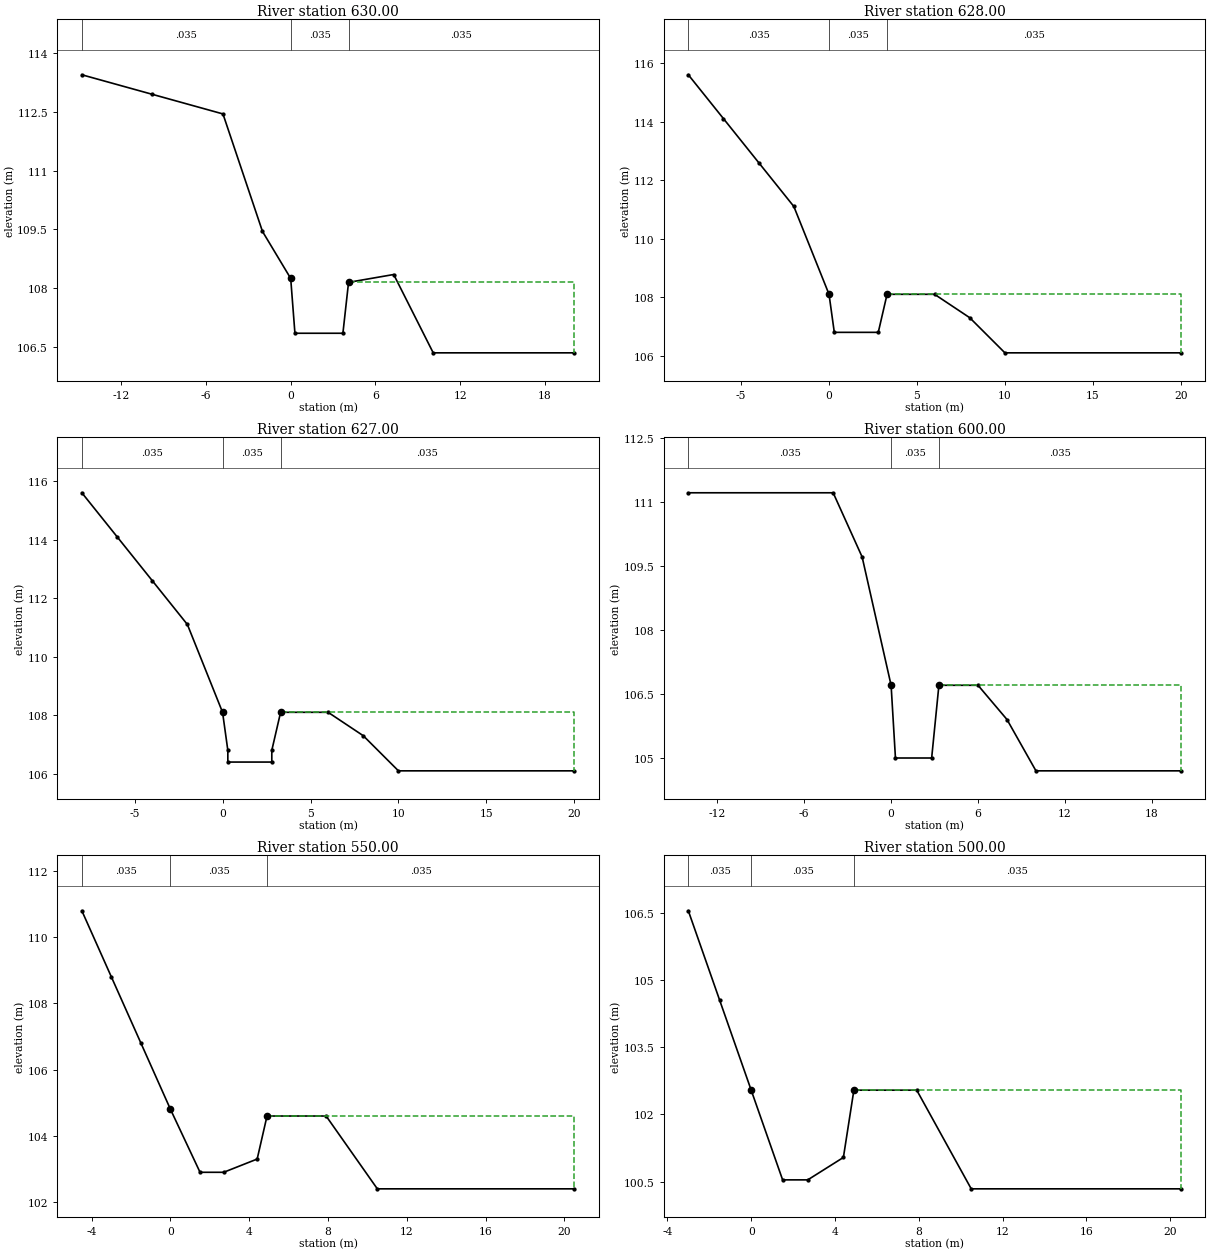
Type RM Length L Ch R = 1 ,630.00  ,2,2,2
BEGIN DESCRIPTION:
12.03
END DESCRIPTION:
#Sta/Elev= 11
   -14.8  113.45    -9.8  112.95    -4.8  112.45      -2  109.45       0  108.25
      .3  106.85     3.7  106.85     4.1  108.15     7.3  108.35    10.1  106.35
    20.1  106.35
#Mann= 3 , 0 , 0
   -14.8    .035       0       0    .035       0     4.1    .035       0
#XS Ineff= 2 , 0
               0  108.25     4.1          108.15
Permanent Ineff=
       F       F
Bank Sta=0,4.1
XS Rating Curve= 0
Exp/Cntr=.3,.1

Type RM Length L Ch R = 1 ,628.00  ,1,1,1
BEGIN DESCRIPTION:
12.028
END DESCRIPTION:
#Sta/Elev= 12
      -8   115.6      -6   114.1      -4   112.6      -2   111.1       0   108.1
      .3   106.8     2.8   106.8     3.3   108.1       6   108.1       8   107.3
      10   106.1      20   106.1
#Mann= 3 , 0 , 0
      -8    .035       0       0    .035       0     3.3    .035       0
#XS Ineff= 2 , 0
               0   108.1     3.3           108.1
Permanent Ineff=
       F       F
Bank Sta=0,3.3
XS Rating Curve= 0
Exp/Cntr=.3,.1

Type RM Length L Ch R = 1 ,627.00  ,27,27,27
BEGIN DESCRIPTION:
12.027
END DESCRIPTION:
#Sta/Elev= 14
      -8   115.6      -6   114.1      -4   112.6      -2   111.1       0   108.1
      .3   106.8      .3   106.4     2.8   106.4     2.8   106.8     3.3   108.1
       6   108.1       8   107.3      10   106.1      20   106.1
#Mann= 3 , 0 , 0
      -8    .035       0       0    .035       0     3.3    .035       0
#XS Ineff= 2 , 0
               0   108.1     3.3           108.1
Permanent Ineff=
       F       F
Bank Sta=0,3.3
XS Rating Curve= 0
Exp/Cntr=.3,.1

Type RM Length L Ch R = 1 ,600.00  ,50,50,50
BEGIN DESCRIPTION:
12
END DESCRIPTION:
#Sta/Elev= 11
     -14  111.21      -4  111.21      -2  109.71       0  106.71      .3  105.01
     2.8  105.01     3.3  106.71       6  106.71       8  105.91      10  104.71
      20  104.71
#Mann= 3 , 0 , 0
     -14    .035       0       0    .035       0     3.3    .035       0
#XS Ineff= 2 , 0
               0  106.71     3.3          106.71
Permanent Ineff=
       F       F
Bank Sta=0,3.3
XS Rating Curve= 0
Exp/Cntr=.3,.1

Type RM Length L Ch R = 1 ,550.00  ,50,50,50
BEGIN DESCRIPTION:
11
END DESCRIPTION:
#Sta/Elev= 11
    -4.5   110.8      -3   108.8    -1.5   106.8       0   104.8     1.5   102.9
     2.7   102.9     4.4   103.3     4.9   104.6     7.9   104.6    10.5   102.4
    20.5   102.4
#Mann= 3 , 0 , 0
    -4.5    .035       0       0    .035       0     4.9    .035       0
#XS Ineff= 2 , 0
               0   104.8     4.9           104.6
Permanent Ineff=
       F       F
Bank Sta=0,4.9
XS Rating Curve= 0
Exp/Cntr=.3,.1

Type RM Length L Ch R = 1 ,500.00  ,50,50,50
BEGIN DESCRIPTION:
10
END DESCRIPTION:
#Sta/Elev= 10
      -3  106.54    -1.5  104.54       0  102.54     1.5  100.54     2.7  100.54
     4.4  101.04     4.9  102.54     7.9  102.54    10.5  100.34    20.5  100.34
#Mann= 3 , 0 , 0
      -3    .035       0       0    .035       0     4.9    .035       0
#XS Ineff= 2 , 0
               0  102.54     4.9          102.54
Permanent Ineff=
       F       F
Bank Sta=0,4.9
XS Rating Curve= 0
Exp/Cntr=.3,.1

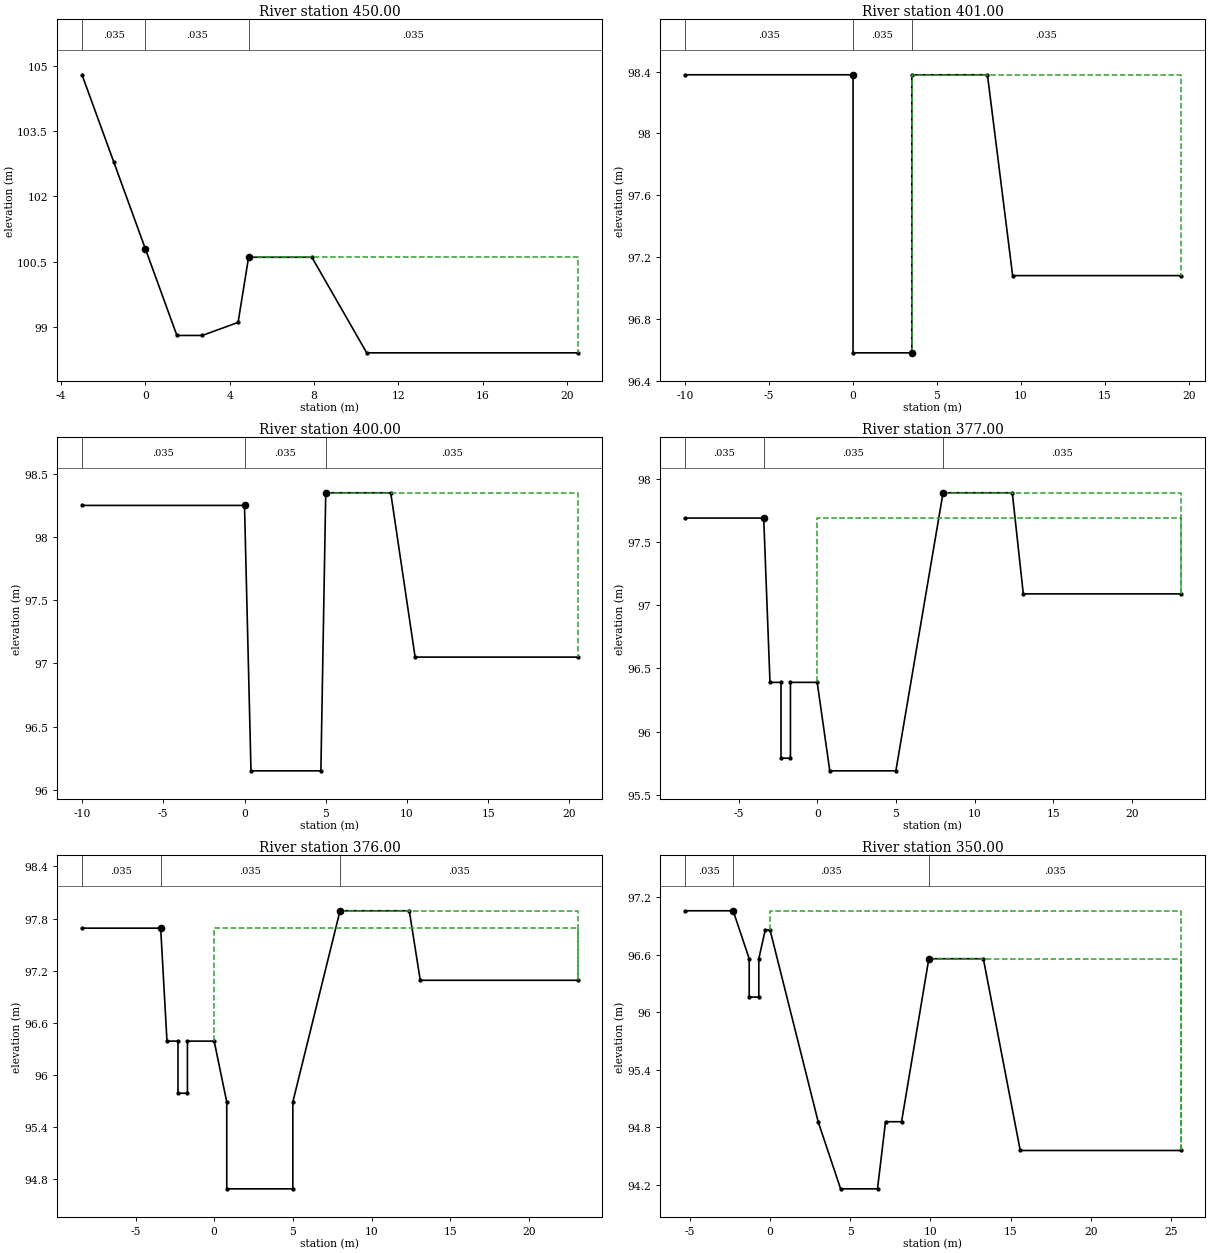
Type RM Length L Ch R = 1 ,450.00  ,49,49,49
BEGIN DESCRIPTION:
9
END DESCRIPTION:
#Sta/Elev= 10
      -3   104.8    -1.5   102.8       0   100.8     1.5    98.8     2.7    98.8
     4.4    99.1     4.9   100.6     7.9   100.6    10.5    98.4    20.5    98.4
#Mann= 3 , 0 , 0
      -3    .035       0       0    .035       0     4.9    .035       0
#XS Ineff= 2 , 0
               0   100.8     4.9           100.6
Permanent Ineff=
       F       F
Bank Sta=0,4.9
XS Rating Curve= 0
Exp/Cntr=.3,.1

Type RM Length L Ch R = 1 ,401.00  ,1,1,1
BEGIN DESCRIPTION:
8.001
END DESCRIPTION:
#Sta/Elev= 8
     -10   98.38       0   98.38       0   96.58     3.5   96.58     3.5   98.38
       8   98.38     9.5   97.08    19.5   97.08
#Mann= 3 , 0 , 0
     -10    .035       0       0    .035       0     3.5    .035       0
#XS Ineff= 2 , 0
               0   98.38     3.5           98.38
Permanent Ineff=
       F       F
Bank Sta=0,3.5
XS Rating Curve= 0
Exp/Cntr=.3,.1

Type RM Length L Ch R = 1 ,400.00  ,23,23,23
BEGIN DESCRIPTION:
8
END DESCRIPTION:
#Sta/Elev= 8
     -10   98.25       0   98.25      .4   96.15     4.7   96.15       5   98.35
       9   98.35    10.5   97.05    20.5   97.05
#Mann= 3 , 0 , 0
     -10    .035       0       0    .035       0       5    .035       0
#XS Ineff= 2 , 0
               0   98.25       5           98.35
Permanent Ineff=
       F       F
Bank Sta=0,5
XS Rating Curve= 0
Exp/Cntr=.3,.1

Type RM Length L Ch R = 1 ,377.00  ,1,1,1
BEGIN DESCRIPTION:
7.027
END DESCRIPTION:
#Sta/Elev= 14
    -8.4   97.69    -3.4   97.69      -3   96.39    -2.3   96.39    -2.3   95.79
    -1.7   95.79    -1.7   96.39       0   96.39      .8   95.69       5   95.69
       8   97.89    12.4   97.89    13.1   97.09    23.1   97.09
#Mann= 3 , 0 , 0
    -8.4    .035       0    -3.4    .035       0       8    .035       0
#XS Ineff= 2 , 0
       0    -3.4   97.69       8       0   97.89
Permanent Ineff=
       F       F
Bank Sta=-3.4,8
XS Rating Curve= 0
Exp/Cntr=.3,.1

Type RM Length L Ch R = 1 ,376.00  ,26,26,26
BEGIN DESCRIPTION:
7.026
END DESCRIPTION:
#Sta/Elev= 16
    -8.4   97.69    -3.4   97.69      -3   96.39    -2.3   96.39    -2.3   95.79
    -1.7   95.79    -1.7   96.39       0   96.39      .8   95.69      .8   94.69
       5   94.69       5   95.69       8   97.89    12.4   97.89    13.1   97.09
    23.1   97.09
#Mann= 3 , 0 , 0
    -8.4    .035       0    -3.4    .035       0       8    .035       0
#XS Ineff= 2 , 0
       0    -3.4   97.69       8       0   97.89
Permanent Ineff=
       F       F
Bank Sta=-3.4,8
XS Rating Curve= 0
Exp/Cntr=.3,.1

Type RM Length L Ch R = 1 ,350.00  ,50,50,50
BEGIN DESCRIPTION:
7
END DESCRIPTION:
#Sta/Elev= 17
    -5.3   97.06    -2.3   97.06    -1.3   96.56    -1.3   96.16     -.7   96.16
     -.7   96.56     -.3   96.86       0   96.86       3   94.86     4.4   94.16
     6.7   94.16     7.2   94.86     8.2   94.86     9.9   96.56    13.3   96.56
    15.6   94.56    25.6   94.56
#Mann= 3 , 0 , 0
    -5.3    .035       0    -2.3    .035       0     9.9    .035       0
#XS Ineff= 2 , 0
       0    -2.3   97.06     9.9       0   96.56
Permanent Ineff=
       F       F
Bank Sta=-2.3,9.9
XS Rating Curve= 0
Exp/Cntr=.3,.1

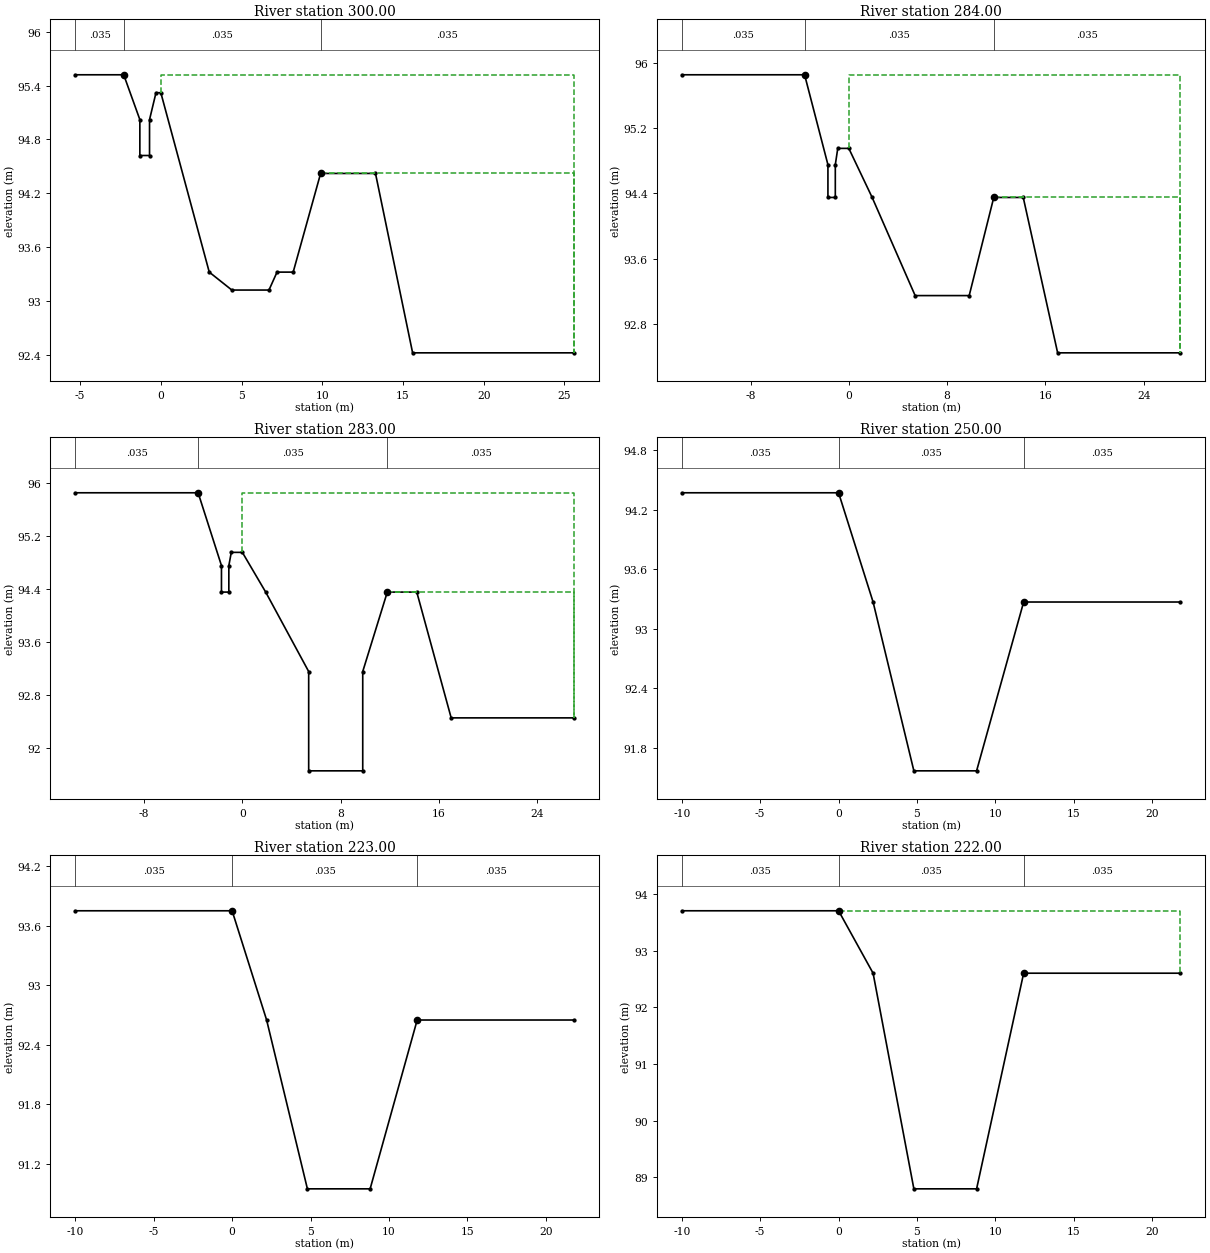
Type RM Length L Ch R = 1 ,300.00  ,16,16,16
BEGIN DESCRIPTION:
6
END DESCRIPTION:
#Sta/Elev= 17
    -5.3   95.52    -2.3   95.52    -1.3   95.02    -1.3   94.62     -.7   94.62
     -.7   95.02     -.3   95.32       0   95.32       3   93.32     4.4   93.12
     6.7   93.12     7.2   93.32     8.2   93.32     9.9   94.42    13.3   94.42
    15.6   92.42    25.6   92.42
#Mann= 3 , 0 , 0
    -5.3    .035       0    -2.3    .035       0     9.9    .035       0
#XS Ineff= 2 , 0
       0    -2.3   95.52     9.9       0   94.42
Permanent Ineff=
       F       F
Bank Sta=-2.3,9.9
XS Rating Curve= 0
Exp/Cntr=.3,.1

Type RM Length L Ch R = 1 ,284.00  ,1,1,1
BEGIN DESCRIPTION:
5.034
END DESCRIPTION:
#Sta/Elev= 15
   -13.6   95.85    -3.6   95.85    -1.7   94.75    -1.7   94.35    -1.1   94.35
    -1.1   94.75     -.9   94.95       0   94.95     1.9   94.35     5.4   93.15
     9.8   93.15    11.8   94.35    14.2   94.35      17   92.45      27   92.45
#Mann= 3 , 0 , 0
   -13.6    .035       0    -3.6    .035       0    11.8    .035       0
#XS Ineff= 2 , 0
       0    -3.6   95.85    11.8       0   94.35
Permanent Ineff=
       F       F
Bank Sta=-3.6,11.8
XS Rating Curve= 0
Exp/Cntr=.3,.1

Type RM Length L Ch R = 1 ,283.00  ,33,33,33
BEGIN DESCRIPTION:
5.033
END DESCRIPTION:
#Sta/Elev= 17
   -13.6   95.85    -3.6   95.85    -1.7   94.75    -1.7   94.35    -1.1   94.35
    -1.1   94.75     -.9   94.95       0   94.95     1.9   94.35     5.4   93.15
     5.4   91.65     9.8   91.65     9.8   93.15    11.8   94.35    14.2   94.35
      17   92.45      27   92.45
#Mann= 3 , 0 , 0
   -13.6    .035       0    -3.6    .035       0    11.8    .035       0
#XS Ineff= 2 , 0
       0    -3.6   95.85    11.8       0   94.35
Permanent Ineff=
       F       F
Bank Sta=-3.6,11.8
XS Rating Curve= 0
Exp/Cntr=.3,.1

Type RM Length L Ch R = 1 ,250.00  ,27,27,27
BEGIN DESCRIPTION:
5
END DESCRIPTION:
#Sta/Elev= 7
     -10   94.37       0   94.37     2.2   93.27     4.8   91.57     8.8   91.57
    11.8   93.27    21.8   93.27
#Mann= 3 , 0 , 0
     -10    .035       0       0    .035       0    11.8    .035       0
#XS Ineff= 2 , 0
               0   94.37    11.8           93.27
Permanent Ineff=
       F       F
Bank Sta=0,11.8
XS Rating Curve= 0
Exp/Cntr=.3,.1

Type RM Length L Ch R = 1 ,223.00  ,1,1,1
BEGIN DESCRIPTION:
4.023
END DESCRIPTION:
#Sta/Elev= 7
     -10   93.75       0   93.75     2.2   92.65     4.8   90.95     8.8   90.95
    11.8   92.65    21.8   92.65
#Mann= 3 , 0 , 0
     -10    .035       0       0    .035       0    11.8    .035       0
#XS Ineff= 2 , 0
               0   93.75    11.8           92.65
Permanent Ineff=
       F       F
Bank Sta=0,11.8
XS Rating Curve= 0
Exp/Cntr=.3,.1

Type RM Length L Ch R = 1 ,222.00  ,1,1,1
BEGIN DESCRIPTION:
4.022
END DESCRIPTION:
#Sta/Elev= 7
     -10    93.7       0    93.7     2.2    92.6     4.8    88.8     8.8    88.8
    11.8    92.6    21.8    92.6
#Mann= 3 , 0 , 0
     -10    .035       0       0    .035       0    11.8    .035       0
#XS Ineff= 2 , 0
       0       0    93.7    11.8       0    92.6
Permanent Ineff=
       F       F
Bank Sta=0,11.8
XS Rating Curve= 0
Exp/Cntr=.3,.1

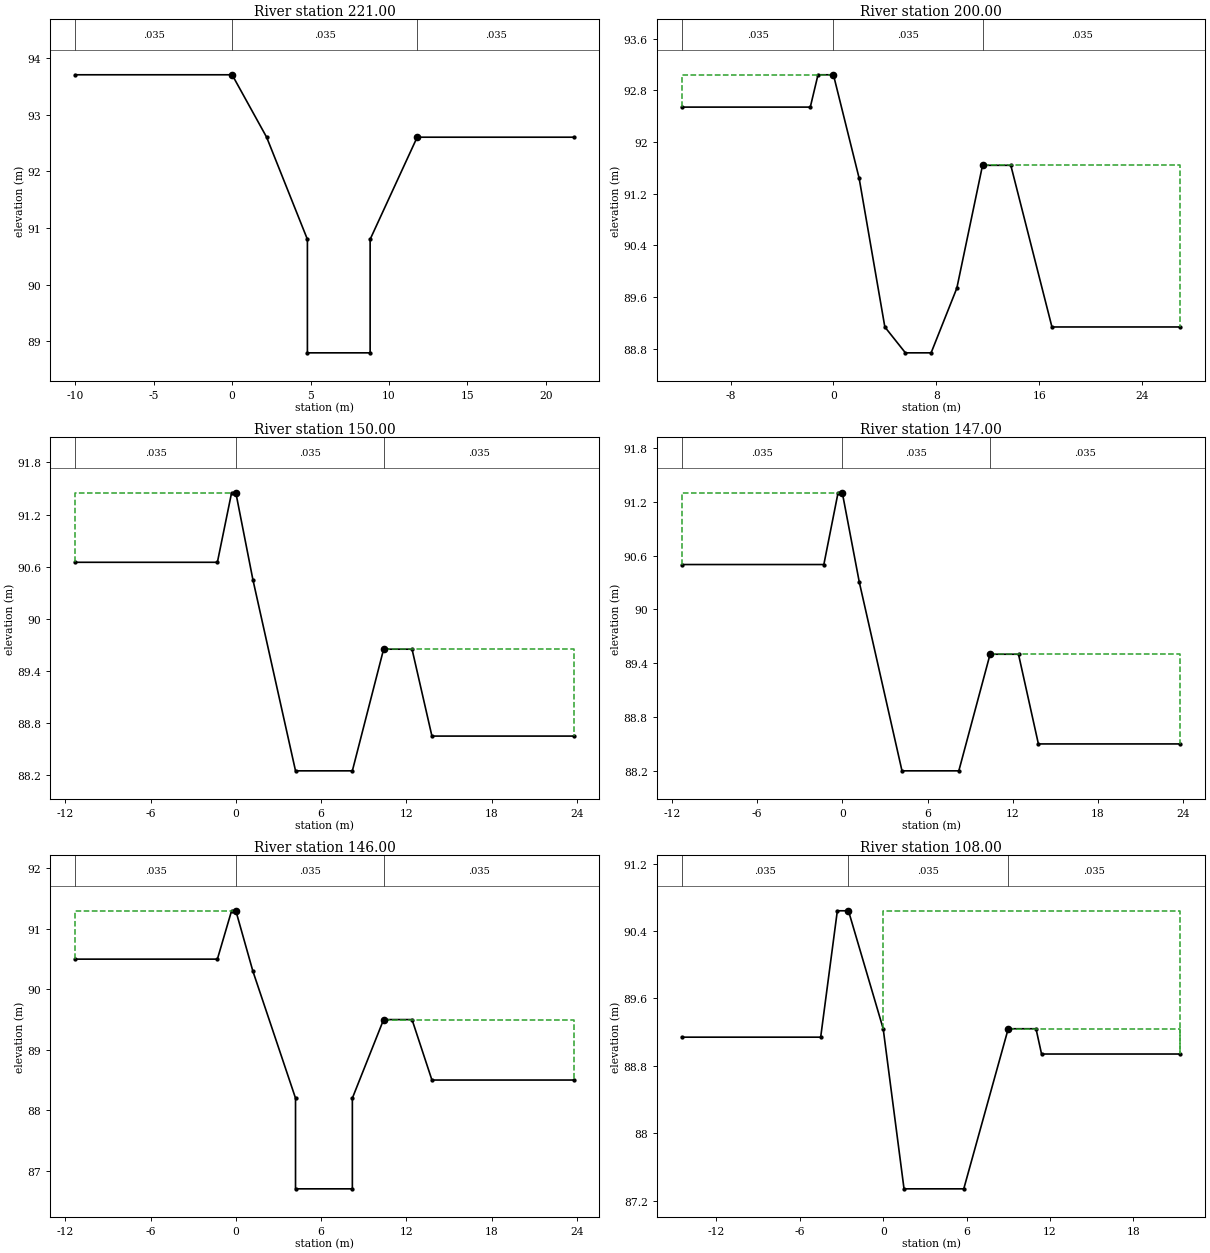
Type RM Length L Ch R = 1 ,221.00  ,21,21,21
BEGIN DESCRIPTION:
4.021
END DESCRIPTION:
#Sta/Elev= 9
     -10    93.7       0    93.7     2.2    92.6     4.8    90.8     4.8    88.8
     8.8    88.8     8.8    90.8    11.8    92.6    21.8    92.6
#Mann= 3 , 0 , 0
     -10    .035       0       0    .035       0    11.8    .035       0
#XS Ineff= 2 , 0
               0    93.7    11.8            92.6
Permanent Ineff=
       F       F
Bank Sta=0,11.8
XS Rating Curve= 0
Exp/Cntr=.3,.1

Type RM Length L Ch R = 1 ,200.00  ,50,50,50
BEGIN DESCRIPTION:
4
END DESCRIPTION:
#Sta/Elev= 13
   -11.8   92.54    -1.8   92.54    -1.2   93.04       0   93.04       2   91.44
       4   89.14     5.6   88.74     7.6   88.74     9.6   89.74    11.6   91.64
    13.8   91.64      17   89.14      27   89.14
#Mann= 3 , 0 , 0
   -11.8    .035       0       0    .035       0    11.6    .035       0
#XS Ineff= 2 , 0
               0   93.04    11.6           91.64
Permanent Ineff=
       F       F
Bank Sta=0,11.6
XS Rating Curve= 0
Exp/Cntr=.3,.1

Type RM Length L Ch R = 1 ,150.00  ,3,3,3
BEGIN DESCRIPTION:
3
END DESCRIPTION:
#Sta/Elev= 11
   -11.3   90.65    -1.3   90.65     -.3   91.45       0   91.45     1.2   90.45
     4.2   88.25     8.2   88.25    10.4   89.65    12.4   89.65    13.8   88.65
    23.8   88.65
#Mann= 3 , 0 , 0
   -11.3    .035       0       0    .035       0    10.4    .035       0
#XS Ineff= 2 , 0
               0   91.45    10.4           89.65
Permanent Ineff=
       F       F
Bank Sta=0,10.4
XS Rating Curve= 0
Exp/Cntr=.3,.1

Type RM Length L Ch R = 1 ,147.00  ,1,1,1
BEGIN DESCRIPTION:
2.047
END DESCRIPTION:
#Sta/Elev= 11
   -11.3    90.5    -1.3    90.5     -.3    91.3       0    91.3     1.2    90.3
     4.2    88.2     8.2    88.2    10.4    89.5    12.4    89.5    13.8    88.5
    23.8    88.5
#Mann= 3 , 0 , 0
   -11.3    .035       0       0    .035       0    10.4    .035       0
#XS Ineff= 2 , 0
               0    91.3    10.4            89.5
Permanent Ineff=
       F       F
Bank Sta=0,10.4
XS Rating Curve= 0
Exp/Cntr=.3,.1

Type RM Length L Ch R = 1 ,146.00  ,38,38,38
BEGIN DESCRIPTION:
2.046
END DESCRIPTION:
#Sta/Elev= 13
   -11.3    90.5    -1.3    90.5     -.3    91.3       0    91.3     1.2    90.3
     4.2    88.2     4.2    86.7     8.2    86.7     8.2    88.2    10.4    89.5
    12.4    89.5    13.8    88.5    23.8    88.5
#Mann= 3 , 0 , 0
   -11.3    .035       0       0    .035       0    10.4    .035       0
#XS Ineff= 2 , 0
               0    91.3    10.4            89.5
Permanent Ineff=
       F       F
Bank Sta=0,10.4
XS Rating Curve= 0
Exp/Cntr=.3,.1

Type RM Length L Ch R = 1 ,108.00  ,1,1,1
BEGIN DESCRIPTION:
2.008
END DESCRIPTION:
#Sta/Elev= 11
   -14.5   89.14    -4.5   89.14    -3.3   90.64    -2.5   90.64       0   89.24
     1.5   87.34     5.8   87.34       9   89.24      11   89.24    11.4   88.94
    21.4   88.94
#Mann= 3 , 0 , 0
   -14.5    .035       0    -2.5    .035       0       9    .035       0
#XS Ineff= 2 , 0
       0    -2.5   90.64       9       0   89.24
Permanent Ineff=
       F       F
Bank Sta=-2.5,9
XS Rating Curve= 0
Exp/Cntr=.3,.1

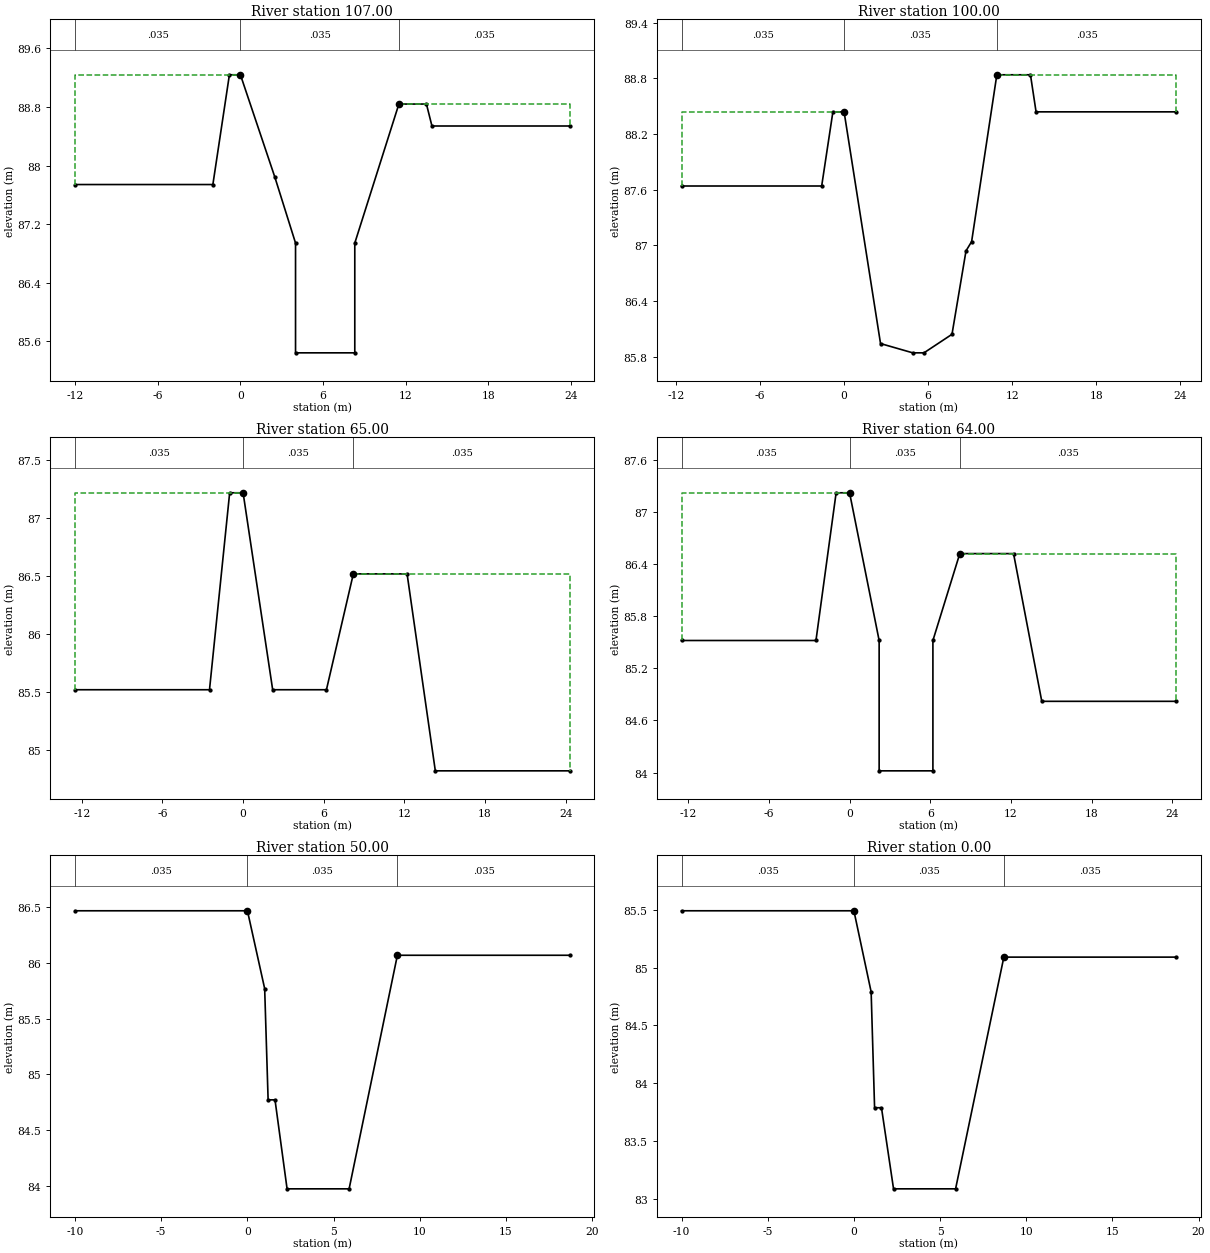
Type RM Length L Ch R = 1 ,107.00  ,7,7,7
BEGIN DESCRIPTION:
2.007
END DESCRIPTION:
#Sta/Elev= 13
     -12   87.74      -2   87.74     -.8   89.24       0   89.24     2.5   87.84
       4   86.94       4   85.44     8.3   85.44     8.3   86.94    11.5   88.84
    13.5   88.84    13.9   88.54    23.9   88.54
#Mann= 3 , 0 , 0
     -12    .035       0       0    .035       0    11.5    .035       0
#XS Ineff= 2 , 0
               0   89.24    11.5           88.84
Permanent Ineff=
       F       F
Bank Sta=0,11.5
XS Rating Curve= 0
Exp/Cntr=.3,.1

Type RM Length L Ch R = 1 ,100.00  ,35,35,35
BEGIN DESCRIPTION:
2
END DESCRIPTION:
#Sta/Elev= 14
   -11.6   87.64    -1.6   87.64     -.8   88.44       0   88.44     2.6   85.94
     4.9   85.84     5.7   85.84     7.7   86.04     8.7   86.94     9.1   87.04
    10.9   88.84    13.3   88.84    13.7   88.44    23.7   88.44
#Mann= 3 , 0 , 0
   -11.6    .035       0       0    .035       0    10.9    .035       0
#XS Ineff= 2 , 0
               0   88.44    10.9           88.84
Permanent Ineff=
       F       F
Bank Sta=0,10.9
XS Rating Curve= 0
Exp/Cntr=.3,.1

Type RM Length L Ch R = 1 ,65.00   ,1,1,1
BEGIN DESCRIPTION:
1.015
END DESCRIPTION:
#Sta/Elev= 10
   -12.5   85.52    -2.5   85.52      -1   87.22       0   87.22     2.2   85.52
     6.2   85.52     8.2   86.52    12.2   86.52    14.3   84.82    24.3   84.82
#Mann= 3 , 0 , 0
   -12.5    .035       0       0    .035       0     8.2    .035       0
#XS Ineff= 2 , 0
               0   87.22     8.2           86.52
Permanent Ineff=
       F       F
Bank Sta=0,8.2
XS Rating Curve= 0
Exp/Cntr=.3,.1

Type RM Length L Ch R = 1 ,64.00   ,14,14,14
BEGIN DESCRIPTION:
1.014
END DESCRIPTION:
#Sta/Elev= 12
   -12.5   85.52    -2.5   85.52      -1   87.22       0   87.22     2.2   85.52
     2.2   84.02     6.2   84.02     6.2   85.52     8.2   86.52    12.2   86.52
    14.3   84.82    24.3   84.82
#Mann= 3 , 0 , 0
   -12.5    .035       0       0    .035       0     8.2    .035       0
#XS Ineff= 2 , 0
               0   87.22     8.2           86.52
Permanent Ineff=
       F       F
Bank Sta=0,8.2
XS Rating Curve= 0
Exp/Cntr=.3,.1

Type RM Length L Ch R = 1 ,50.00   ,50,50,50
BEGIN DESCRIPTION:
1
END DESCRIPTION:
#Sta/Elev= 9
     -10   86.47       0   86.47       1   85.77     1.2   84.77     1.6   84.77
     2.3   83.97     5.9   83.97     8.7   86.07    18.7   86.07
#Mann= 3 , 0 , 0
     -10    .035       0       0    .035       0     8.7    .035       0
#XS Ineff= 2 , 0
               0   86.47     8.7           86.07
Permanent Ineff=
       F       F
Bank Sta=0,8.7
XS Rating Curve= 0
Exp/Cntr=.3,.1

Type RM Length L Ch R = 1 ,0.00    ,0,0,0
BEGIN DESCRIPTION:
0
END DESCRIPTION:
#Sta/Elev= 9
     -10   85.49       0   85.49       1   84.79     1.2   83.79     1.6   83.79
     2.3   83.09     5.9   83.09     8.7   85.09    18.7   85.09
#Mann= 3 , 0 , 0
     -10    .035       0       0    .035       0     8.7    .035       0
#XS Ineff= 2 , 0
               0   85.49     8.7           85.09
Permanent Ineff=
       F       F
Bank Sta=0,8.7
XS Rating Curve= 0
Exp/Cntr=.3,.1

Chan Stop Cuts=-1