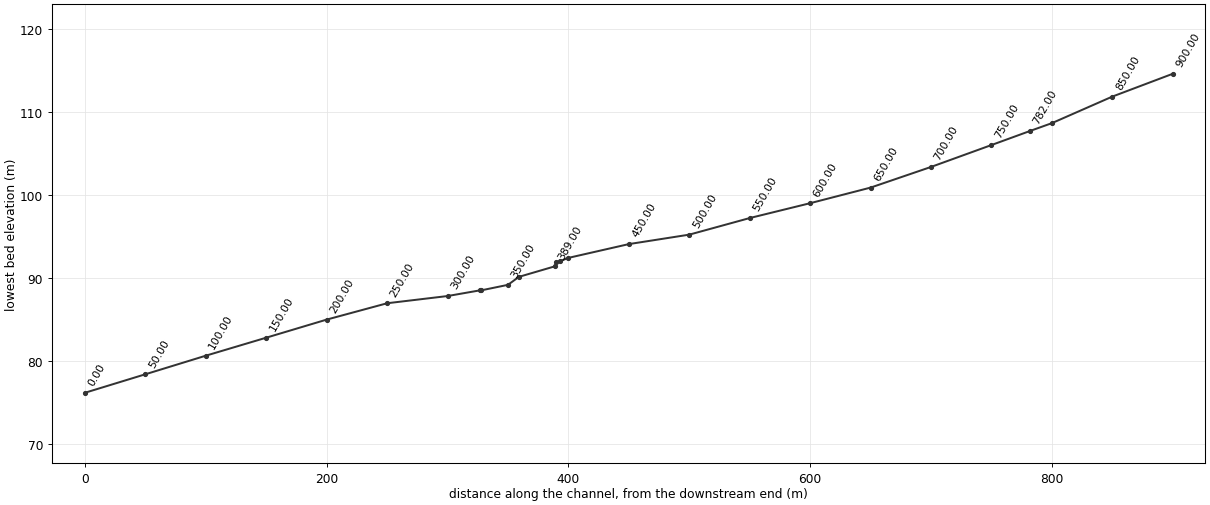
--- NPC.prj (project) ---

Proj Title=napeon-ch
Current Plan=p01
Default Exp/Contr=.3,.1
SI Units
Geom File=g01
Flow File=f01
Plan File=p01
Y Axis Title=Elevation
X Axis Title(PF)=Main Channel Distance
X Axis Title(XS)=Station
BEGIN DESCRIPTION:
           BACK WATER COMPUTATION
      APPLICATION OF HEC-2 BY Samju Construction Engineering
      napeon-ch: 10,20,30,50,80 yr
END DESCRIPTION:
DSS Export Rating Curves= 0
DSS Export Rating Curve Sorted= 0
DSS Export Volume Flow Curves= 0
DXF OffsetX= 0
DXF OffsetY= 0
DXF ScaleX= 1
DXF ScaleY= 10

--- NPC.p01 (plan) ---

Plan Title=Imported Plan 01
Version=Version 3.0.1  Mar 2001
Short Identifier=Imported Pla
Geom File=g01
Flow File=f01
Subcritical Flow
K Sum by GR= 0
Std Step Tol= 0.003
Critical Tol= 0.003
Num of Std Step Trials= 20
Max Error Tol= 0.1
Flow Tol Ratio= 0.001
Split Flow NTrial= 30
Split Flow Tol= 0.02
Split Flow Ratio= 0.02
Log Output Level= 0
Friction Slope Method= 1
Unsteady Friction Slope Method= 2
Parabolic Critical Depth
Global Vel Dist= 0 , 0 , 0
Global Log Level= 0
CheckData=True
Encroach Param=-1 ,0,0, 0
Computation Interval=1HOUR
Output Interval=1HOUR
Run HTab= 0
Run UNet= 0
Run PostProcess= 0
UNET Theta= 1
UNET ZTol= 0.02
UNET ZSATol= 0.1
UNET MxIter= 20
UNET MaxInSteps= 20
UNET DtIC= 0
UNET DtMin= 0
UNET MaxCRTS= 20
UNET WFStab= 2
UNET SFStab= 1
UNET WFX= 1
UNET SFX= 1
UNET Convert EG Bridges=-1
UNET Use Existing IB Tables=-1
Instantaneous Interval=1HOUR
Write IC File= 0
Write Velocity= 0
Write Detailed= 0

--- NPC.f01 (steady flow) ---

Flow Title=Imported Flow 01
Version=Version 3.0.1  Mar 2001
Number of Profiles= 5
Profile Names=10YR,20YR,30YR,50YR,80YR
River Rch & RM=RIVER-1,Reach-1         ,900.00
   13.07    14.4   15.18   16.16   17.06
Boundary for River Rch & Prof#=RIVER-1,Reach-1         , 1
Up Type= 0
Dn Type= 3
Dn Slope=.042
Boundary for River Rch & Prof#=RIVER-1,Reach-1         , 2
Up Type= 0
Dn Type= 3
Dn Slope=.042
Boundary for River Rch & Prof#=RIVER-1,Reach-1         , 3
Up Type= 0
Dn Type= 3
Dn Slope=.042
Boundary for River Rch & Prof#=RIVER-1,Reach-1         , 4
Up Type= 0
Dn Type= 3
Dn Slope=.042
Boundary for River Rch & Prof#=RIVER-1,Reach-1         , 5
Up Type= 0
Dn Type= 3
Dn Slope=.042
DSS Import GetInterval= 0
DSS Import GetPeak= 0
DSS Import FillOption= 0

--- NPC.g01 (geometry) ---

Geom Title=Imported Geom 01
Version=Version 3.0.1  Mar 2001

River Reach=RIVER-1         ,Reach-1
Reach XY= 2
              .5             .95              .5             .05

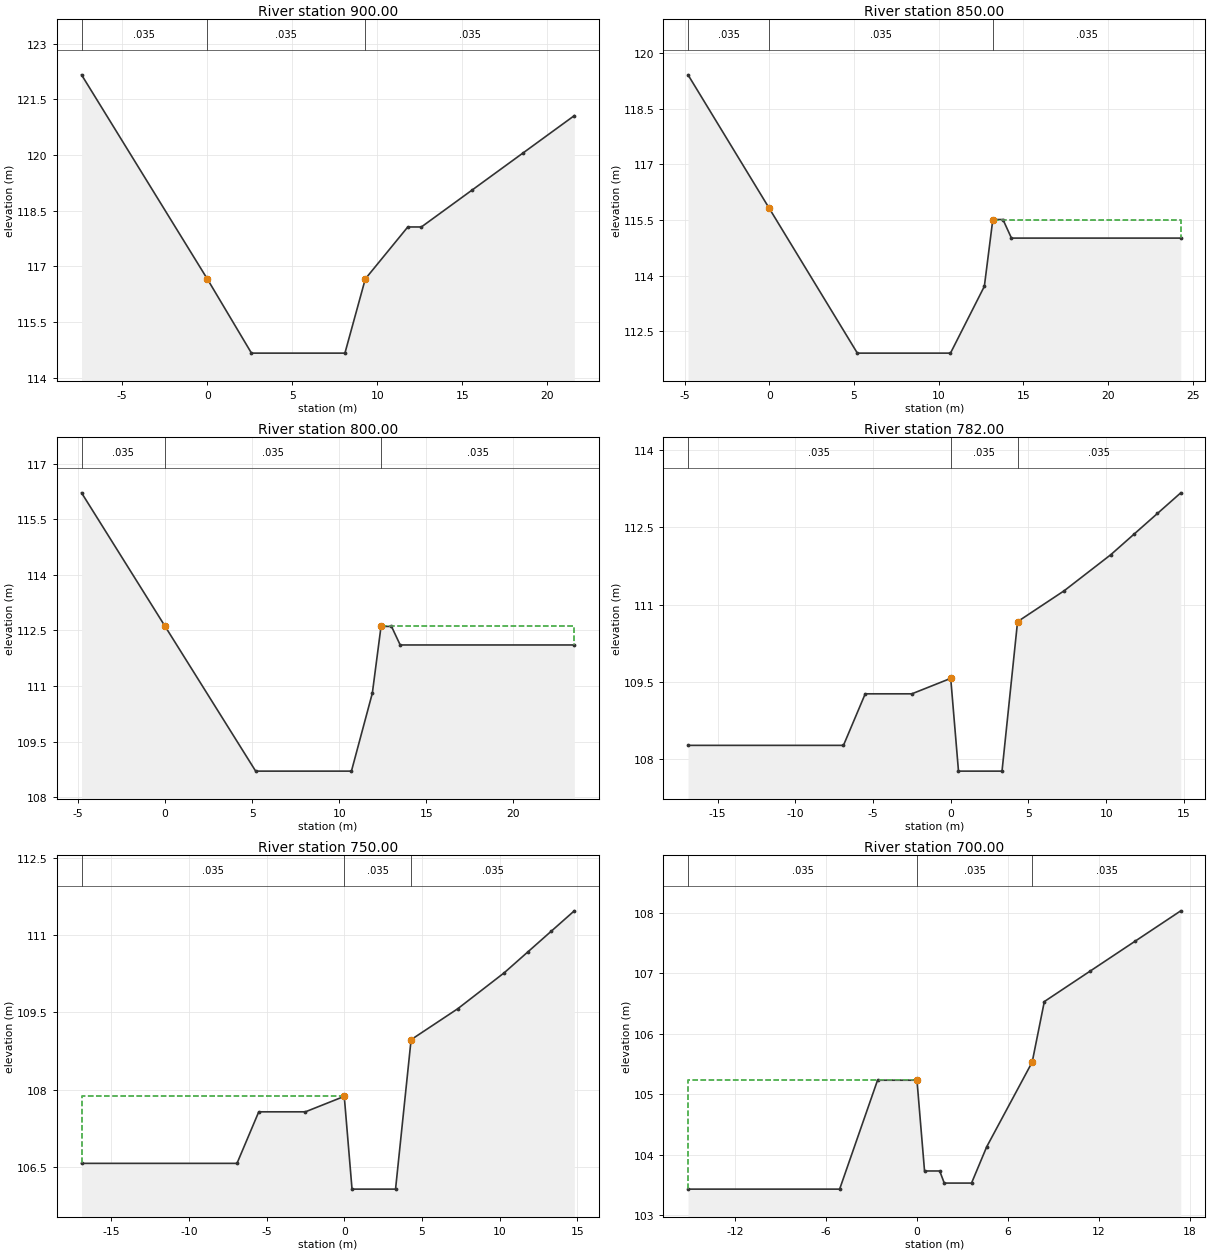
Type RM Length L Ch R = 1 ,900.00  ,50,50,50
BEGIN DESCRIPTION:
18
END DESCRIPTION:
#Sta/Elev= 10
    -7.4  122.16       0  116.66     2.6  114.66     8.1  114.66     9.3  116.66
    11.8  118.06    12.6  118.06    15.6  119.06    18.6  120.06    21.6  121.06
#Mann= 3 , 0 , 0
    -7.4    .035       0       0    .035       0     9.3    .035       0
#XS Ineff= 2 , 0
               0  116.66     9.3          116.66
Permanent Ineff=
       F       F
Bank Sta=0,9.3
XS Rating Curve= 0
Exp/Cntr=.3,.1

Type RM Length L Ch R = 1 ,850.00  ,50,50,50
BEGIN DESCRIPTION:
17
END DESCRIPTION:
#Sta/Elev= 9
    -4.8  119.41       0  115.81     5.2  111.91    10.7  111.91    12.7  113.71
    13.2  115.51    13.8  115.51    14.3  115.01    24.3  115.01
#Mann= 3 , 0 , 0
    -4.8    .035       0       0    .035       0    13.2    .035       0
#XS Ineff= 2 , 0
               0  115.81    13.2          115.51
Permanent Ineff=
       F       F
Bank Sta=0,13.2
XS Rating Curve= 0
Exp/Cntr=.3,.1

Type RM Length L Ch R = 1 ,800.00  ,18,18,18
BEGIN DESCRIPTION:
16
END DESCRIPTION:
#Sta/Elev= 9
    -4.8  116.21       0  112.61     5.2  108.71    10.7  108.71    11.9  110.81
    12.4  112.61      13  112.61    13.5  112.11    23.5  112.11
#Mann= 3 , 0 , 0
    -4.8    .035       0       0    .035       0    12.4    .035       0
#XS Ineff= 2 , 0
               0  112.61    12.4          112.61
Permanent Ineff=
       F       F
Bank Sta=0,12.4
XS Rating Curve= 0
Exp/Cntr=.3,.1

Type RM Length L Ch R = 1 ,782.00  ,32,32,32
BEGIN DESCRIPTION:
15.032
END DESCRIPTION:
#Sta/Elev= 13
   -16.9  108.27    -6.9  108.27    -5.5  109.27    -2.5  109.27       0  109.57
      .5  107.77     3.3  107.77     4.3  110.67     7.3  111.27    10.3  111.97
    11.8  112.37    13.3  112.77    14.8  113.17
#Mann= 3 , 0 , 0
   -16.9    .035       0       0    .035       0     4.3    .035       0
#XS Ineff= 2 , 0
       0       0  109.57     4.3       0  110.67
Permanent Ineff=
       F       F
Bank Sta=0,4.3
XS Rating Curve= 0
Exp/Cntr=.3,.1

Type RM Length L Ch R = 1 ,750.00  ,50,50,50
BEGIN DESCRIPTION:
15
END DESCRIPTION:
#Sta/Elev= 13
   -16.9  106.57    -6.9  106.57    -5.5  107.57    -2.5  107.57       0  107.87
      .5  106.07     3.3  106.07     4.3  108.97     7.3  109.57    10.3  110.27
    11.8  110.67    13.3  111.07    14.8  111.47
#Mann= 3 , 0 , 0
   -16.9    .035       0       0    .035       0     4.3    .035       0
#XS Ineff= 2 , 0
               0  107.87     4.3          108.97
Permanent Ineff=
       F       F
Bank Sta=0,4.3
XS Rating Curve= 0
Exp/Cntr=.3,.1

Type RM Length L Ch R = 1 ,700.00  ,50,50,50
BEGIN DESCRIPTION:
14
END DESCRIPTION:
#Sta/Elev= 14
   -15.1  103.43    -5.1  103.43    -2.6  105.23       0  105.23      .5  103.73
     1.5  103.73     1.8  103.53     3.6  103.53     4.6  104.13     7.6  105.53
     8.4  106.53    11.4  107.03    14.4  107.53    17.4  108.03
#Mann= 3 , 0 , 0
   -15.1    .035       0       0    .035       0     7.6    .035       0
#XS Ineff= 2 , 0
               0  105.23     7.6          105.53
Permanent Ineff=
       F       F
Bank Sta=0,7.6
XS Rating Curve= 0
Exp/Cntr=.3,.1

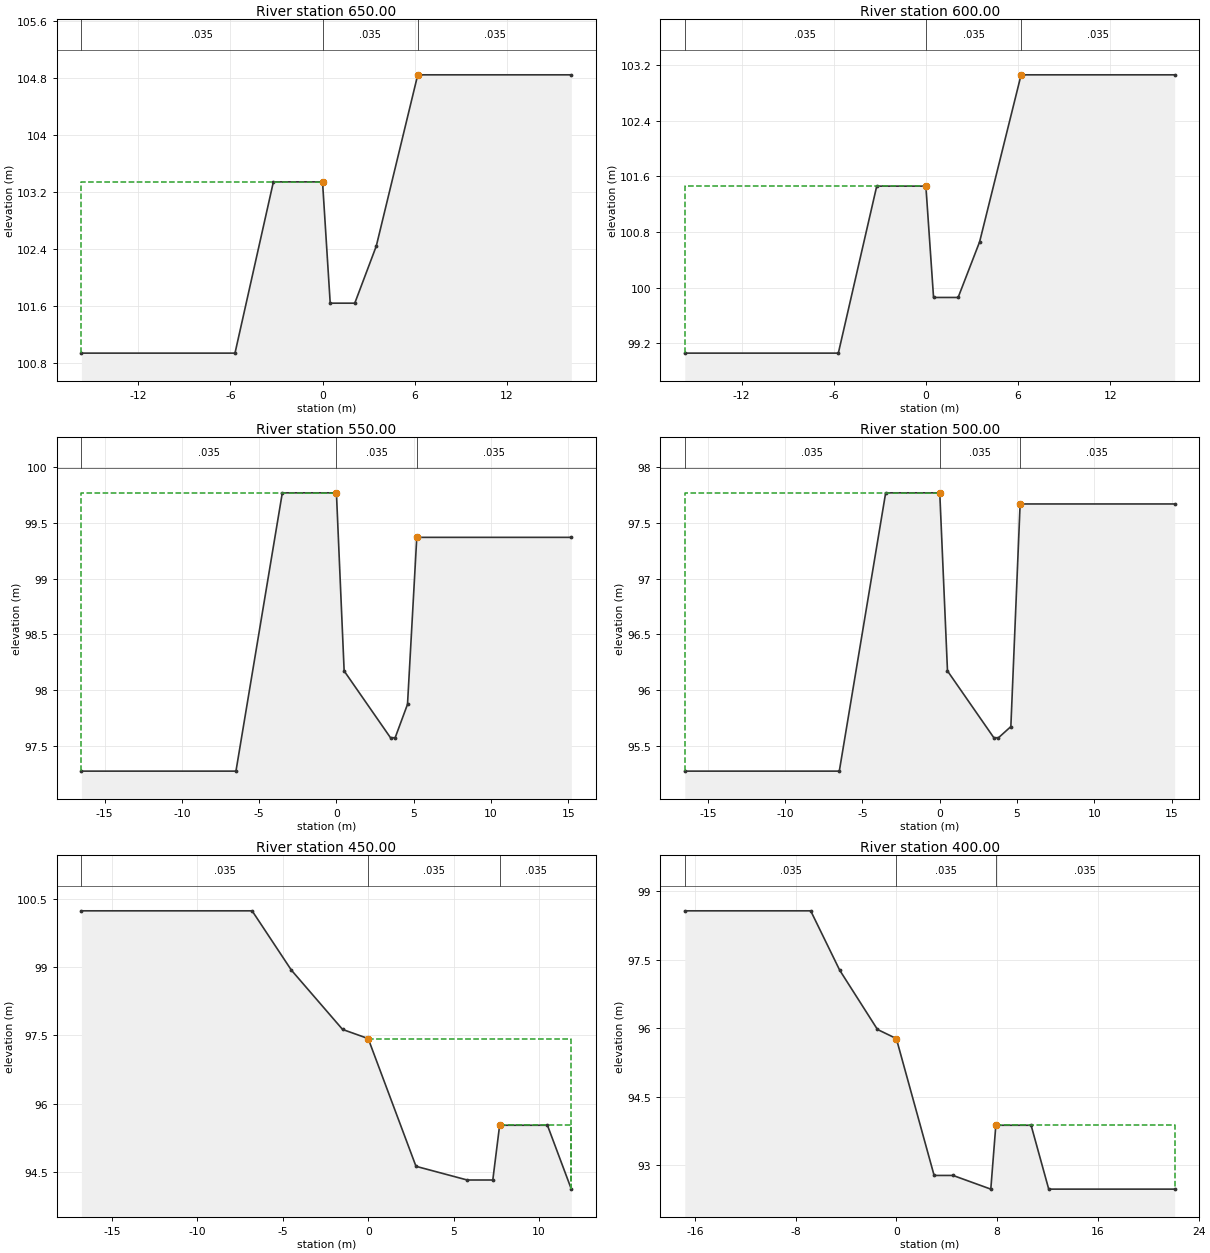
Type RM Length L Ch R = 1 ,650.00  ,50,50,50
BEGIN DESCRIPTION:
13
END DESCRIPTION:
#Sta/Elev= 9
   -15.7  100.94    -5.7  100.94    -3.2  103.34       0  103.34      .5  101.64
     2.1  101.64     3.5  102.44     6.2  104.84    16.2  104.84
#Mann= 3 , 0 , 0
   -15.7    .035       0       0    .035       0     6.2    .035       0
#XS Ineff= 2 , 0
               0  103.34     6.2          104.84
Permanent Ineff=
       F       F
Bank Sta=0,6.2
XS Rating Curve= 0
Exp/Cntr=.3,.1

Type RM Length L Ch R = 1 ,600.00  ,50,50,50
BEGIN DESCRIPTION:
12
END DESCRIPTION:
#Sta/Elev= 9
   -15.7   99.06    -5.7   99.06    -3.2  101.46       0  101.46      .5   99.86
     2.1   99.86     3.5  100.66     6.2  103.06    16.2  103.06
#Mann= 3 , 0 , 0
   -15.7    .035       0       0    .035       0     6.2    .035       0
#XS Ineff= 2 , 0
               0  101.46     6.2          103.06
Permanent Ineff=
       F       F
Bank Sta=0,6.2
XS Rating Curve= 0
Exp/Cntr=.3,.1

Type RM Length L Ch R = 1 ,550.00  ,50,50,50
BEGIN DESCRIPTION:
11
END DESCRIPTION:
#Sta/Elev= 10
   -16.5   97.27    -6.5   97.27    -3.5   99.77       0   99.77      .5   98.17
     3.5   97.57     3.8   97.57     4.6   97.87     5.2   99.37    15.2   99.37
#Mann= 3 , 0 , 0
   -16.5    .035       0       0    .035       0     5.2    .035       0
#XS Ineff= 2 , 0
               0   99.77     5.2           99.37
Permanent Ineff=
       F       F
Bank Sta=0,5.2
XS Rating Curve= 0
Exp/Cntr=.3,.1

Type RM Length L Ch R = 1 ,500.00  ,50,50,50
BEGIN DESCRIPTION:
10
END DESCRIPTION:
#Sta/Elev= 10
   -16.5   95.27    -6.5   95.27    -3.5   97.77       0   97.77      .5   96.17
     3.5   95.57     3.8   95.57     4.6   95.67     5.2   97.67    15.2   97.67
#Mann= 3 , 0 , 0
   -16.5    .035       0       0    .035       0     5.2    .035       0
#XS Ineff= 2 , 0
               0   97.77     5.2           97.67
Permanent Ineff=
       F       F
Bank Sta=0,5.2
XS Rating Curve= 0
Exp/Cntr=.3,.1

Type RM Length L Ch R = 1 ,450.00  ,50,50,50
BEGIN DESCRIPTION:
9
END DESCRIPTION:
#Sta/Elev= 11
   -16.8  100.23    -6.8  100.23    -4.5   98.93    -1.5   97.63       0   97.43
     2.8   94.63     5.8   94.33     7.3   94.33     7.7   95.53    10.5   95.53
    11.9   94.13
#Mann= 3 , 0 , 0
   -16.8    .035       0       0    .035       0     7.7    .035       0
#XS Ineff= 2 , 0
       0       0   97.43     7.7       0   95.53
Permanent Ineff=
       F       F
Bank Sta=0,7.7
XS Rating Curve= 0
Exp/Cntr=.3,.1

Type RM Length L Ch R = 1 ,400.00  ,7,7,7
BEGIN DESCRIPTION:
8
END DESCRIPTION:
#Sta/Elev= 12
   -16.8   98.57    -6.8   98.57    -4.5   97.27    -1.5   95.97       0   95.77
       3   92.77     4.5   92.77     7.5   92.47     7.9   93.87    10.7   93.87
    12.1   92.47    22.1   92.47
#Mann= 3 , 0 , 0
   -16.8    .035       0       0    .035       0     7.9    .035       0
#XS Ineff= 2 , 0
               0   95.77     7.9           93.87
Permanent Ineff=
       F       F
Bank Sta=0,7.9
XS Rating Curve= 0
Exp/Cntr=.3,.1

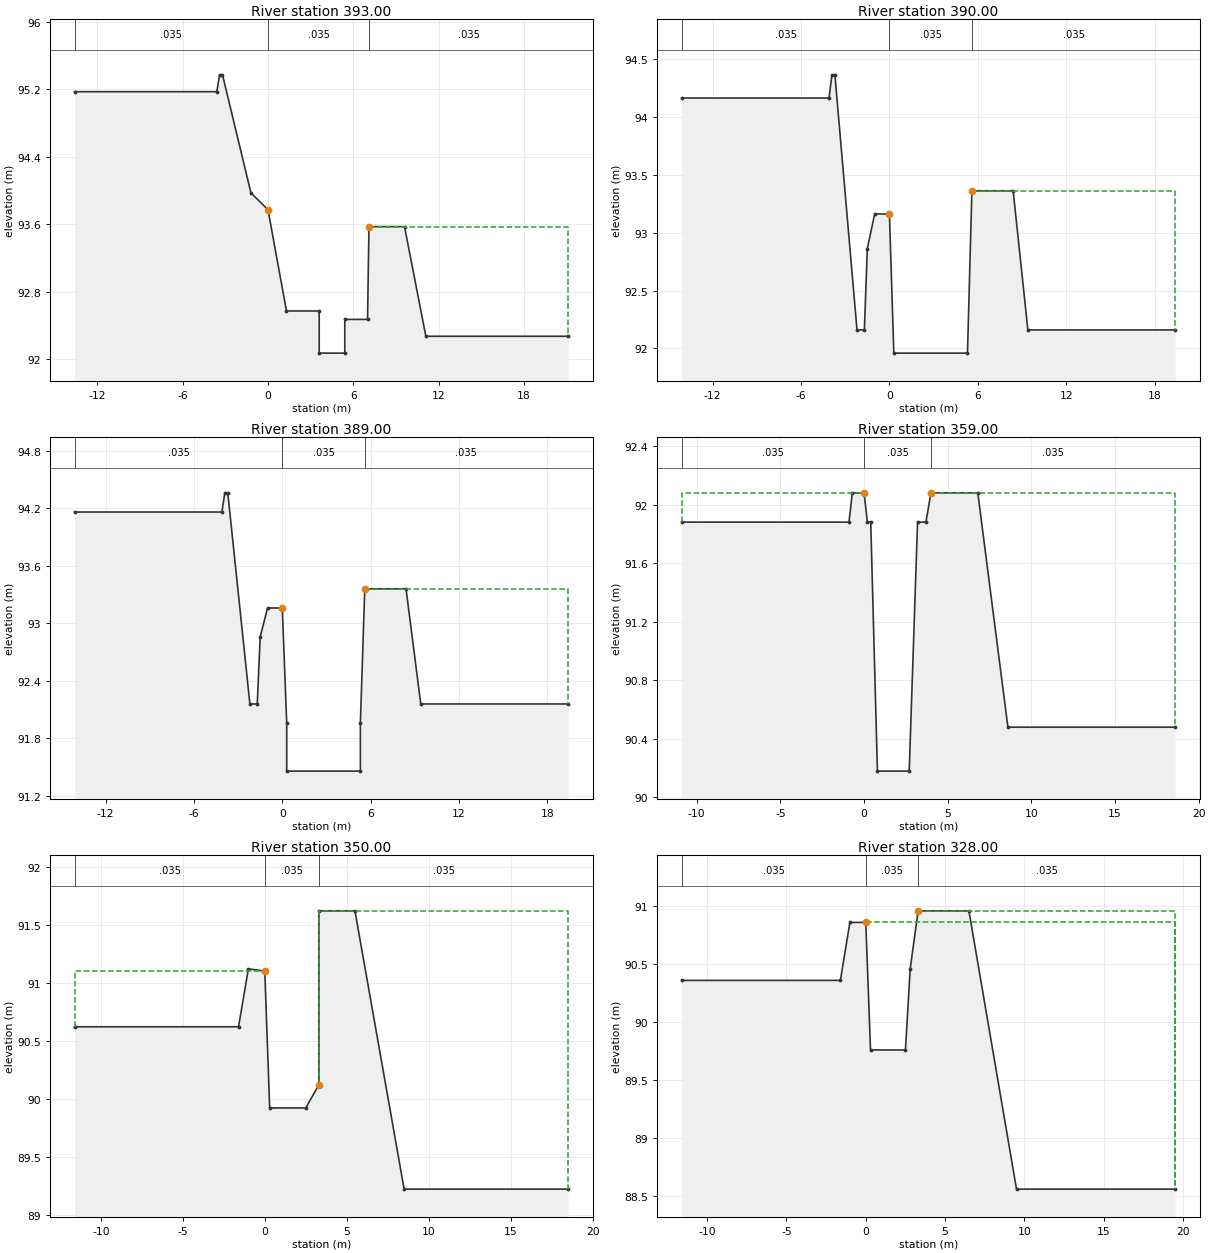
Type RM Length L Ch R = 1 ,393.00  ,3,3,3
BEGIN DESCRIPTION:
7.043
END DESCRIPTION:
#Sta/Elev= 16
   -13.6   95.17    -3.6   95.17    -3.4   95.37    -3.2   95.37    -1.2   93.97
       0   93.77     1.3   92.57     3.6   92.57     3.6   92.07     5.4   92.07
     5.4   92.47       7   92.47     7.1   93.57     9.6   93.57    11.1   92.27
    21.1   92.27
#Mann= 3 , 0 , 0
   -13.6    .035       0       0    .035       0     7.1    .035       0
#XS Ineff= 2 , 0
               0   93.77     7.1           93.57
Permanent Ineff=
       F       F
Bank Sta=0,7.1
XS Rating Curve= 0
Exp/Cntr=.3,.1

Type RM Length L Ch R = 1 ,390.00  ,1,1,1
BEGIN DESCRIPTION:
7.04
END DESCRIPTION:
#Sta/Elev= 15
   -14.1   94.16    -4.1   94.16    -3.9   94.36    -3.7   94.36    -2.2   92.16
    -1.7   92.16    -1.5   92.86      -1   93.16       0   93.16      .3   91.96
     5.3   91.96     5.6   93.36     8.4   93.36     9.4   92.16    19.4   92.16
#Mann= 3 , 0 , 0
   -14.1    .035       0       0    .035       0     5.6    .035       0
#XS Ineff= 2 , 0
               0   93.16     5.6           93.36
Permanent Ineff=
       F       F
Bank Sta=0,5.6
XS Rating Curve= 0
Exp/Cntr=.3,.1

Type RM Length L Ch R = 1 ,389.00  ,30,30,30
BEGIN DESCRIPTION:
7.039
END DESCRIPTION:
#Sta/Elev= 17
   -14.1   94.16    -4.1   94.16    -3.9   94.36    -3.7   94.36    -2.2   92.16
    -1.7   92.16    -1.5   92.86      -1   93.16       0   93.16      .3   91.96
      .3   91.46     5.3   91.46     5.3   91.96     5.6   93.36     8.4   93.36
     9.4   92.16    19.4   92.16
#Mann= 3 , 0 , 0
   -14.1    .035       0       0    .035       0     5.6    .035       0
#XS Ineff= 2 , 0
               0   93.16     5.6           93.36
Permanent Ineff=
       F       F
Bank Sta=0,5.6
XS Rating Curve= 0
Exp/Cntr=.3,.1

Type RM Length L Ch R = 1 ,359.00  ,9,9,9
BEGIN DESCRIPTION:
7.009
END DESCRIPTION:
#Sta/Elev= 14
   -10.9   91.88     -.9   91.88     -.7   92.08       0   92.08      .2   91.88
      .4   91.88      .8   90.18     2.7   90.18     3.2   91.88     3.7   91.88
       4   92.08     6.8   92.08     8.6   90.48    18.6   90.48
#Mann= 3 , 0 , 0
   -10.9    .035       0       0    .035       0       4    .035       0
#XS Ineff= 2 , 0
               0   92.08       4           92.08
Permanent Ineff=
       F       F
Bank Sta=0,4
XS Rating Curve= 0
Exp/Cntr=.3,.1

Type RM Length L Ch R = 1 ,350.00  ,22,22,22
BEGIN DESCRIPTION:
7
END DESCRIPTION:
#Sta/Elev= 11
   -11.6   90.62    -1.6   90.62      -1   91.12       0    91.1      .3   89.92
     2.5   89.92     3.3   90.12     3.3   91.62     5.5   91.62     8.5   89.22
    18.5   89.22
#Mann= 3 , 0 , 0
   -11.6    .035       0       0    .035       0     3.3    .035       0
#XS Ineff= 2 , 0
               0    91.1     3.3           91.62
Permanent Ineff=
       F       F
Bank Sta=0,3.3
XS Rating Curve= 0
Exp/Cntr=.3,.1

Type RM Length L Ch R = 1 ,328.00  ,1,1,1
BEGIN DESCRIPTION:
6.028
END DESCRIPTION:
#Sta/Elev= 11
   -11.6   90.36    -1.6   90.36      -1   90.86       0   90.86      .3   89.76
     2.5   89.76     2.8   90.46     3.3   90.96     6.5   90.96     9.5   88.56
    19.5   88.56
#Mann= 3 , 0 , 0
   -11.6    .035       0       0    .035       0     3.3    .035       0
#XS Ineff= 2 , 0
       0       0   90.86     3.3       0   90.96
Permanent Ineff=
       F       F
Bank Sta=0,3.3
XS Rating Curve= 0
Exp/Cntr=.3,.1

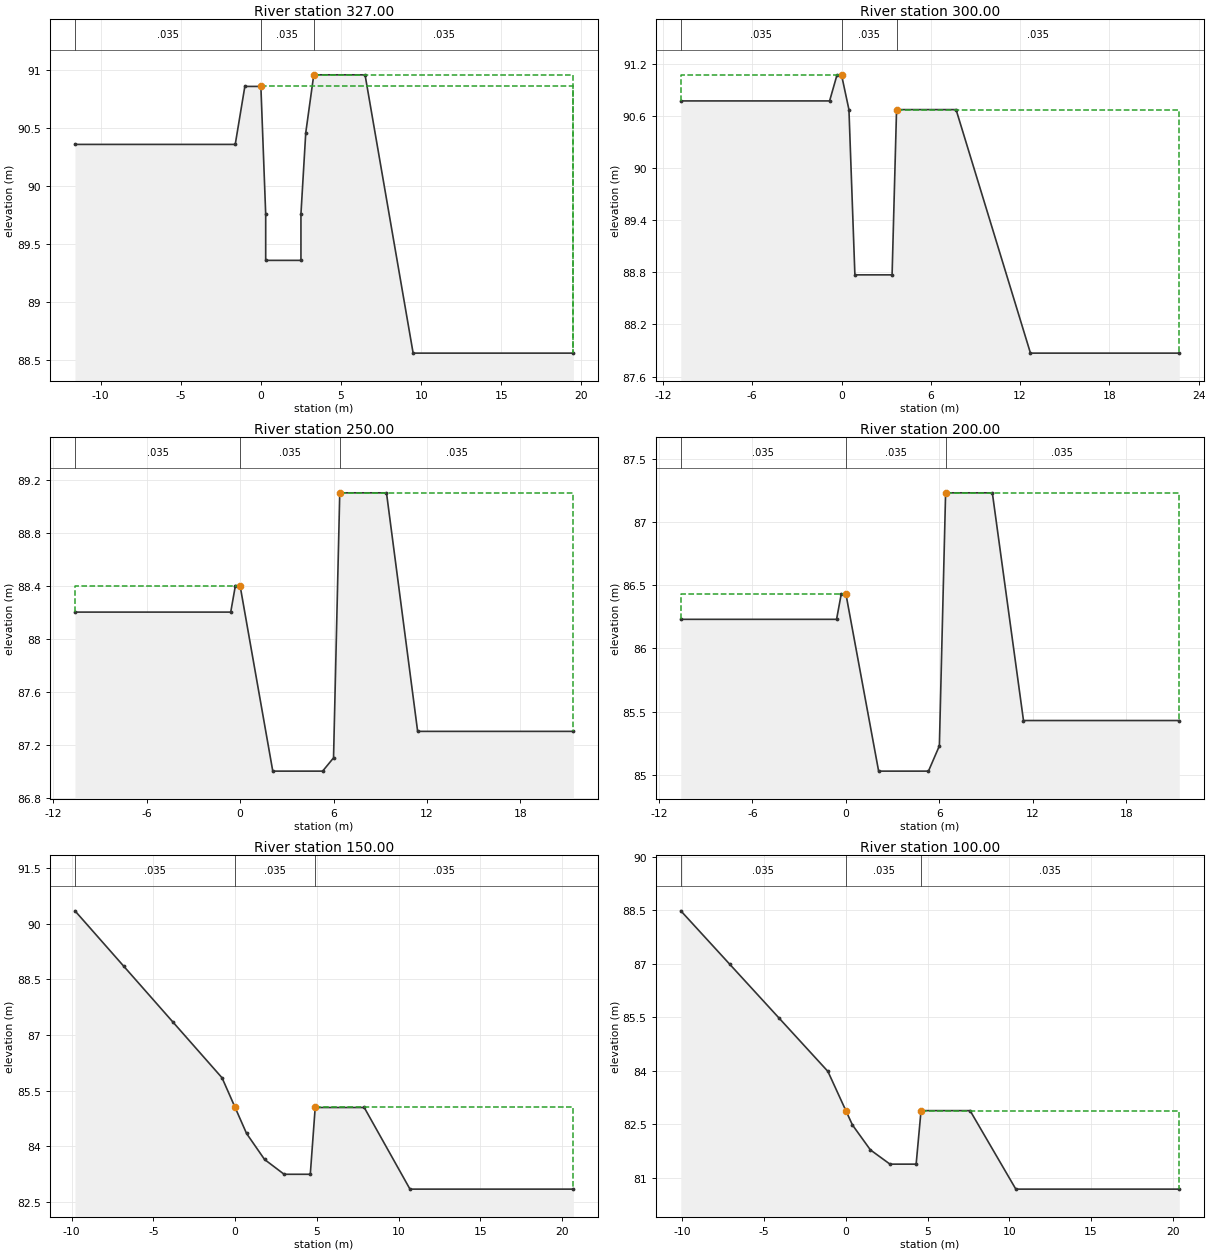
Type RM Length L Ch R = 1 ,327.00  ,27,27,27
BEGIN DESCRIPTION:
6.027
END DESCRIPTION:
#Sta/Elev= 13
   -11.6   90.36    -1.6   90.36      -1   90.86       0   90.86      .3   89.76
      .3   89.36     2.5   89.36     2.5   89.76     2.8   90.46     3.3   90.96
     6.5   90.96     9.5   88.56    19.5   88.56
#Mann= 3 , 0 , 0
   -11.6    .035       0       0    .035       0     3.3    .035       0
#XS Ineff= 2 , 0
       0       0   90.86     3.3       0   90.96
Permanent Ineff=
       F       F
Bank Sta=0,3.3
XS Rating Curve= 0
Exp/Cntr=.3,.1

Type RM Length L Ch R = 1 ,300.00  ,50,50,50
BEGIN DESCRIPTION:
6
END DESCRIPTION:
#Sta/Elev= 11
   -10.8   90.77     -.8   90.77     -.3   91.07       0   91.07      .5   90.67
      .9   88.77     3.4   88.77     3.7   90.67     7.7   90.67    12.7   87.87
    22.7   87.87
#Mann= 3 , 0 , 0
   -10.8    .035       0       0    .035       0     3.7    .035       0
#XS Ineff= 2 , 0
               0   91.07     3.7           90.67
Permanent Ineff=
       F       F
Bank Sta=0,3.7
XS Rating Curve= 0
Exp/Cntr=.3,.1

Type RM Length L Ch R = 1 ,250.00  ,50,50,50
BEGIN DESCRIPTION:
5
END DESCRIPTION:
#Sta/Elev= 11
   -10.6    88.2     -.6    88.2     -.3    88.4       0    88.4     2.1      87
     5.3      87       6    87.1     6.4    89.1     9.4    89.1    11.4    87.3
    21.4    87.3
#Mann= 3 , 0 , 0
   -10.6    .035       0       0    .035       0     6.4    .035       0
#XS Ineff= 2 , 0
               0    88.4     6.4            89.1
Permanent Ineff=
       F       F
Bank Sta=0,6.4
XS Rating Curve= 0
Exp/Cntr=.3,.1

Type RM Length L Ch R = 1 ,200.00  ,50,50,50
BEGIN DESCRIPTION:
4
END DESCRIPTION:
#Sta/Elev= 11
   -10.6   86.23     -.6   86.23     -.3   86.43       0   86.43     2.1   85.03
     5.3   85.03       6   85.23     6.4   87.23     9.4   87.23    11.4   85.43
    21.4   85.43
#Mann= 3 , 0 , 0
   -10.6    .035       0       0    .035       0     6.4    .035       0
#XS Ineff= 2 , 0
               0   86.43     6.4           87.23
Permanent Ineff=
       F       F
Bank Sta=0,6.4
XS Rating Curve= 0
Exp/Cntr=.3,.1

Type RM Length L Ch R = 1 ,150.00  ,50,50,50
BEGIN DESCRIPTION:
3
END DESCRIPTION:
#Sta/Elev= 13
    -9.8   90.35    -6.8   88.85    -3.8   87.35     -.8   85.85       0   85.05
      .7   84.35     1.8   83.65       3   83.25     4.6   83.25     4.9   85.05
     7.9   85.05    10.7   82.85    20.7   82.85
#Mann= 3 , 0 , 0
    -9.8    .035       0       0    .035       0     4.9    .035       0
#XS Ineff= 2 , 0
               0   85.05     4.9           85.05
Permanent Ineff=
       F       F
Bank Sta=0,4.9
XS Rating Curve= 0
Exp/Cntr=.3,.1

Type RM Length L Ch R = 1 ,100.00  ,50,50,50
BEGIN DESCRIPTION:
2
END DESCRIPTION:
#Sta/Elev= 13
   -10.1   88.48    -7.1   86.98    -4.1   85.48    -1.1   83.98       0   82.88
      .4   82.48     1.5   81.78     2.7   81.38     4.3   81.38     4.6   82.88
     7.6   82.88    10.4   80.68    20.4   80.68
#Mann= 3 , 0 , 0
   -10.1    .035       0       0    .035       0     4.6    .035       0
#XS Ineff= 2 , 0
               0   82.88     4.6           82.88
Permanent Ineff=
       F       F
Bank Sta=0,4.6
XS Rating Curve= 0
Exp/Cntr=.3,.1

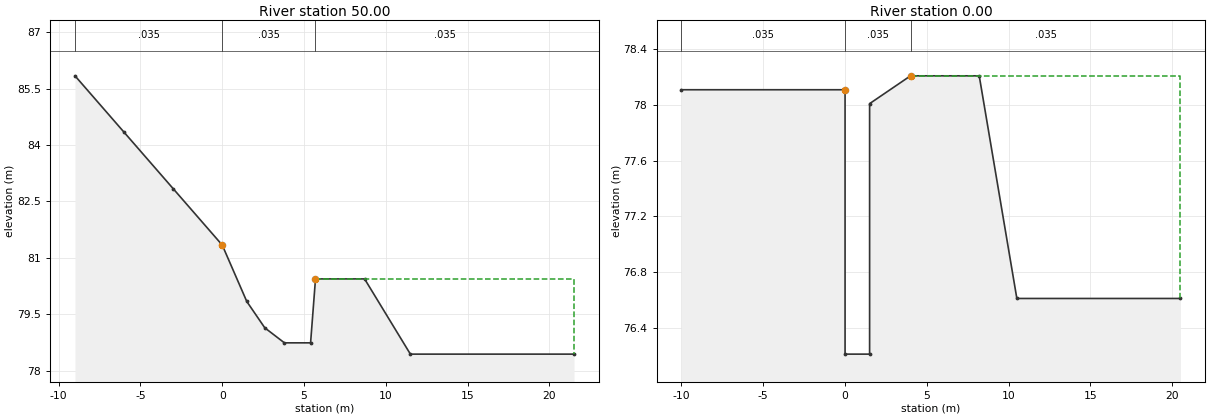
Type RM Length L Ch R = 1 ,50.00   ,50,50,50
BEGIN DESCRIPTION:
1
END DESCRIPTION:
#Sta/Elev= 12
      -9   85.84      -6   84.34      -3   82.84       0   81.34     1.5   79.84
     2.6   79.14     3.8   78.74     5.4   78.74     5.7   80.44     8.7   80.44
    11.5   78.44    21.5   78.44
#Mann= 3 , 0 , 0
      -9    .035       0       0    .035       0     5.7    .035       0
#XS Ineff= 2 , 0
               0   81.34     5.7           80.44
Permanent Ineff=
       F       F
Bank Sta=0,5.7
XS Rating Curve= 0
Exp/Cntr=.3,.1

Type RM Length L Ch R = 1 ,0.00    ,0,0,0
BEGIN DESCRIPTION:
0
END DESCRIPTION:
#Sta/Elev= 9
     -10   78.11       0   78.11       0   76.21     1.5   76.21     1.5   78.01
       4   78.21     8.2   78.21    10.5   76.61    20.5   76.61
#Mann= 3 , 0 , 0
     -10    .035       0       0    .035       0       4    .035       0
#XS Ineff= 2 , 0
               0   78.11       4           78.21
Permanent Ineff=
       F       F
Bank Sta=0,4
XS Rating Curve= 0
Exp/Cntr=.3,.1

Chan Stop Cuts=-1