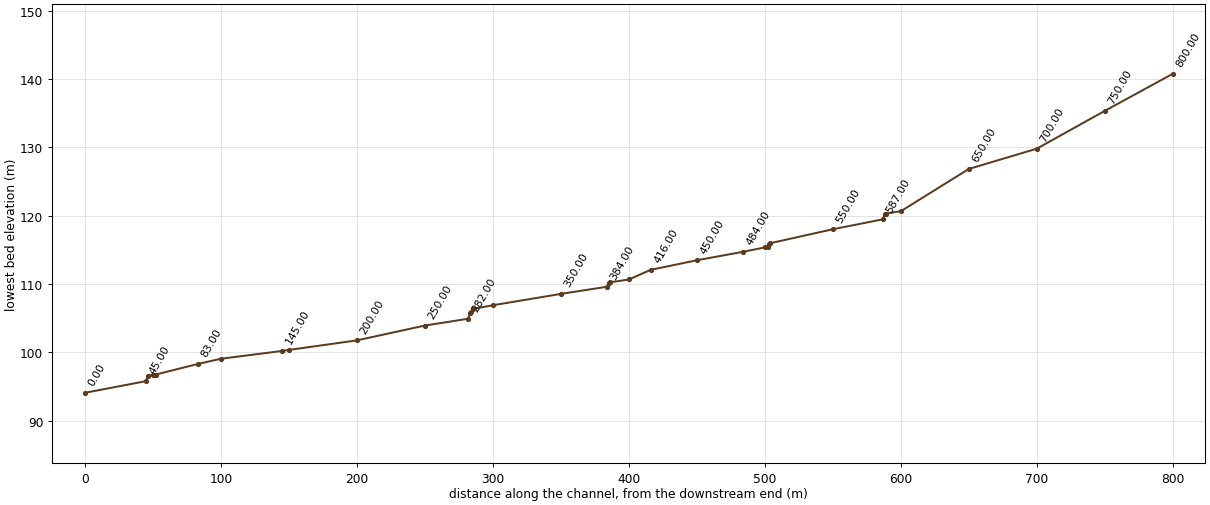
--- DANG.prj (project) ---

Proj Title=dangkong-ch
Current Plan=p01
Default Exp/Contr=.3,.1
SI Units
Geom File=g01
Flow File=f01
Plan File=p01
Y Axis Title=Elevation
X Axis Title(PF)=Main Channel Distance
X Axis Title(XS)=Station
BEGIN DESCRIPTION:
           BACK WATER COMPUTATION
      APPLICATION OF HEC-2 BY Samju Construction Engineering
      dangkong-ch:10,20,30,50,80 yr
END DESCRIPTION:
DSS Export Rating Curves= 0
DSS Export Rating Curve Sorted= 0
DSS Export Volume Flow Curves= 0
DXF OffsetX= 0
DXF OffsetY= 0
DXF ScaleX= 1
DXF ScaleY= 10

--- DANG.p01 (plan) ---

Plan Title=Imported Plan 01
Version=Version 3.0.1  Mar 2001
Short Identifier=Imported Pla
Geom File=g01
Flow File=f01
Subcritical Flow
K Sum by GR= 0
Std Step Tol= 0.003
Critical Tol= 0.003
Num of Std Step Trials= 20
Max Error Tol= 0.1
Flow Tol Ratio= 0.001
Split Flow NTrial= 30
Split Flow Tol= 0.02
Split Flow Ratio= 0.02
Log Output Level= 0
Friction Slope Method= 1
Unsteady Friction Slope Method= 2
Parabolic Critical Depth
Global Vel Dist= 0 , 0 , 0
Global Log Level= 0
CheckData=True
Encroach Param=-1 ,0,0, 0
Computation Interval=1HOUR
Output Interval=1HOUR
Run HTab= 0
Run UNet= 0
Run PostProcess= 0
UNET Theta= 1
UNET ZTol= 0.02
UNET ZSATol= 0.1
UNET MxIter= 20
UNET MaxInSteps= 20
UNET DtIC= 0
UNET DtMin= 0
UNET MaxCRTS= 20
UNET WFStab= 2
UNET SFStab= 1
UNET WFX= 1
UNET SFX= 1
UNET Convert EG Bridges=-1
UNET Use Existing IB Tables=-1
Instantaneous Interval=1HOUR
Write IC File= 0
Write Velocity= 0
Write Detailed= 0

--- DANG.f01 (steady flow) ---

Flow Title=Imported Flow 01
Version=Version 3.0.1  Mar 2001
Number of Profiles= 5
Profile Names=10YR,20YR,30YR,50YR,80YR
River Rch & RM=RIVER-1,Reach-1         ,800.00
    5.43    5.98     6.3    6.71    7.08
Boundary for River Rch & Prof#=RIVER-1,Reach-1         , 1
Up Type= 0
Dn Type= 3
Dn Slope=.044
Boundary for River Rch & Prof#=RIVER-1,Reach-1         , 2
Up Type= 0
Dn Type= 3
Dn Slope=.044
Boundary for River Rch & Prof#=RIVER-1,Reach-1         , 3
Up Type= 0
Dn Type= 3
Dn Slope=.044
Boundary for River Rch & Prof#=RIVER-1,Reach-1         , 4
Up Type= 0
Dn Type= 3
Dn Slope=.044
Boundary for River Rch & Prof#=RIVER-1,Reach-1         , 5
Up Type= 0
Dn Type= 3
Dn Slope=.044
DSS Import GetInterval= 0
DSS Import GetPeak= 0
DSS Import FillOption= 0

--- DANG.g01 (geometry) ---

Geom Title=Imported Geom 01
Version=Version 3.0.1  Mar 2001

River Reach=RIVER-1         ,Reach-1
Reach XY= 2
              .5             .95              .5             .05

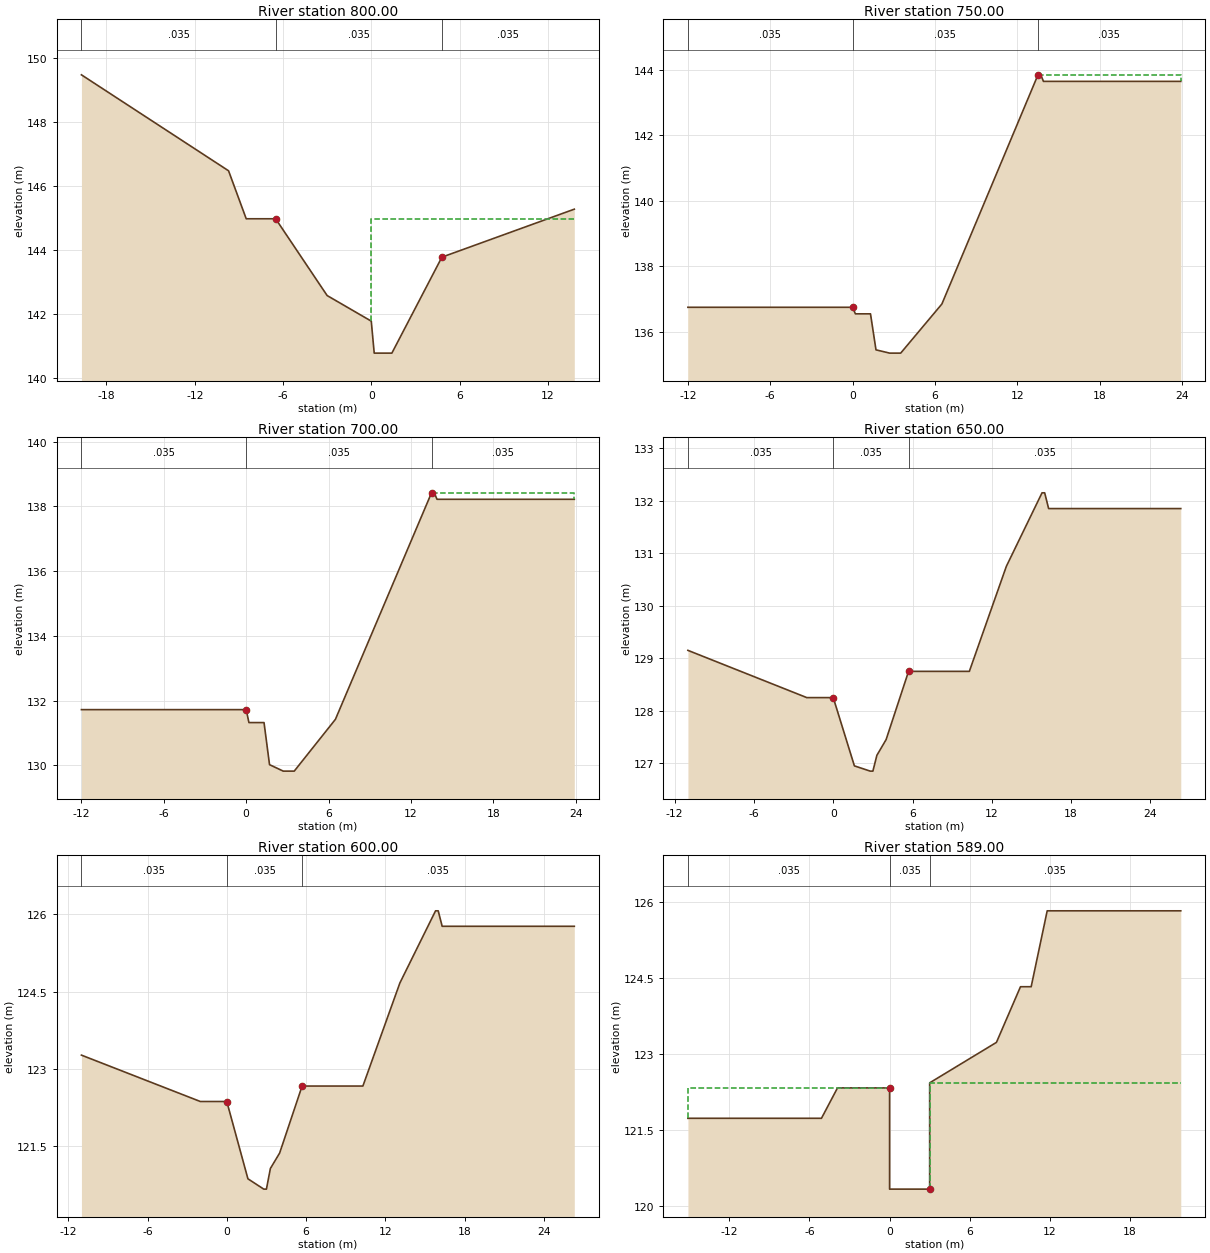
Type RM Length L Ch R = 1 ,800.00  ,50,50,50
BEGIN DESCRIPTION:
16
END DESCRIPTION:
#Sta/Elev= 13
   -19.7  149.48   -14.7  147.98    -9.7  146.48    -8.5  144.98    -6.5  144.98
      -3  142.58       0  141.78      .2  140.78     1.4  140.78     4.8  143.78
     7.8  144.28    10.8  144.78    13.8  145.28
#Mann= 3 , 0 , 0
   -19.7    .035       0    -6.5    .035       0     4.8    .035       0
#XS Ineff= 2 , 0
       0    -6.5  144.98     4.8       0  143.78
Permanent Ineff=
       F       F
Bank Sta=-6.5,4.8
XS Rating Curve= 0
Exp/Cntr=.3,.1

Type RM Length L Ch R = 1 ,750.00  ,50,50,50
BEGIN DESCRIPTION:
15
END DESCRIPTION:
#Sta/Elev= 14
     -12  136.75      -2  136.75       0  136.75      .2  136.55     1.3  136.55
     1.7  135.45     2.7  135.35     3.5  135.35     6.5  136.85    11.5  141.85
    13.5  143.85    13.7  143.85    13.9  143.65    23.9  143.65
#Mann= 3 , 0 , 0
     -12    .035       0       0    .035       0    13.5    .035       0
#XS Ineff= 2 , 0
       0       0  136.75    13.5       0  143.85
Permanent Ineff=
       F       F
Bank Sta=0,13.5
XS Rating Curve= 0
Exp/Cntr=.3,.1

Type RM Length L Ch R = 1 ,700.00  ,50,50,50
BEGIN DESCRIPTION:
14
END DESCRIPTION:
#Sta/Elev= 14
     -12  131.72      -2  131.72       0  131.72      .2  131.32     1.3  131.32
     1.7  130.02     2.7  129.82     3.5  129.82     6.5  131.42    11.5  136.42
    13.5  138.42    13.7  138.42    13.9  138.22    23.9  138.22
#Mann= 3 , 0 , 0
     -12    .035       0       0    .035       0    13.5    .035       0
#XS Ineff= 2 , 0
       0       0  131.72    13.5       0  138.42
Permanent Ineff=
       F       F
Bank Sta=0,13.5
XS Rating Curve= 0
Exp/Cntr=.3,.1

Type RM Length L Ch R = 1 ,650.00  ,50,50,50
BEGIN DESCRIPTION:
13
END DESCRIPTION:
#Sta/Elev= 17
     -11  129.15      -8  128.85      -5  128.55      -2  128.25       0  128.25
     1.6  126.95     2.8  126.85       3  126.85     3.3  127.15       4  127.45
     5.7  128.75    10.3  128.75    13.1  130.75    15.8  132.15      16  132.15
    16.3  131.85    26.3  131.85
#Mann= 3 , 0 , 0
     -11    .035       0       0    .035       0     5.7    .035       0
#XS Ineff= 2 , 0
               0  128.25     5.7          128.75
Permanent Ineff=
       F       F
Bank Sta=0,5.7
XS Rating Curve= 0
Exp/Cntr=.3,.1

Type RM Length L Ch R = 1 ,600.00  ,11,11,11
BEGIN DESCRIPTION:
12
END DESCRIPTION:
#Sta/Elev= 17
     -11  123.27      -8  122.97      -5  122.67      -2  122.37       0  122.37
     1.6  120.87     2.8  120.67       3  120.67     3.3  121.07       4  121.37
     5.7  122.67    10.3  122.67    13.1  124.67    15.8  126.07      16  126.07
    16.3  125.77    26.3  125.77
#Mann= 3 , 0 , 0
     -11    .035       0       0    .035       0     5.7    .035       0
#XS Ineff= 2 , 0
       0       0  122.37     5.7       0  122.67
Permanent Ineff=
       F       F
Bank Sta=0,5.7
XS Rating Curve= 0
Exp/Cntr=.3,.1

Type RM Length L Ch R = 1 ,589.00  ,1,1,1
BEGIN DESCRIPTION:
11.039
END DESCRIPTION:
#Sta/Elev= 12
   -15.1  121.73    -5.1  121.73    -3.9  122.33       0  122.33       0  120.33
       3  120.33       3  122.43       8  123.23     9.8  124.33    10.6  124.33
    11.8  125.83    21.8  125.83
#Mann= 3 , 0 , 0
   -15.1    .035       0       0    .035       0       3    .035       0
#XS Ineff= 2 , 0
               0  122.33       3          122.43
Permanent Ineff=
       F       F
Bank Sta=0,3
XS Rating Curve= 0
Exp/Cntr=.3,.1

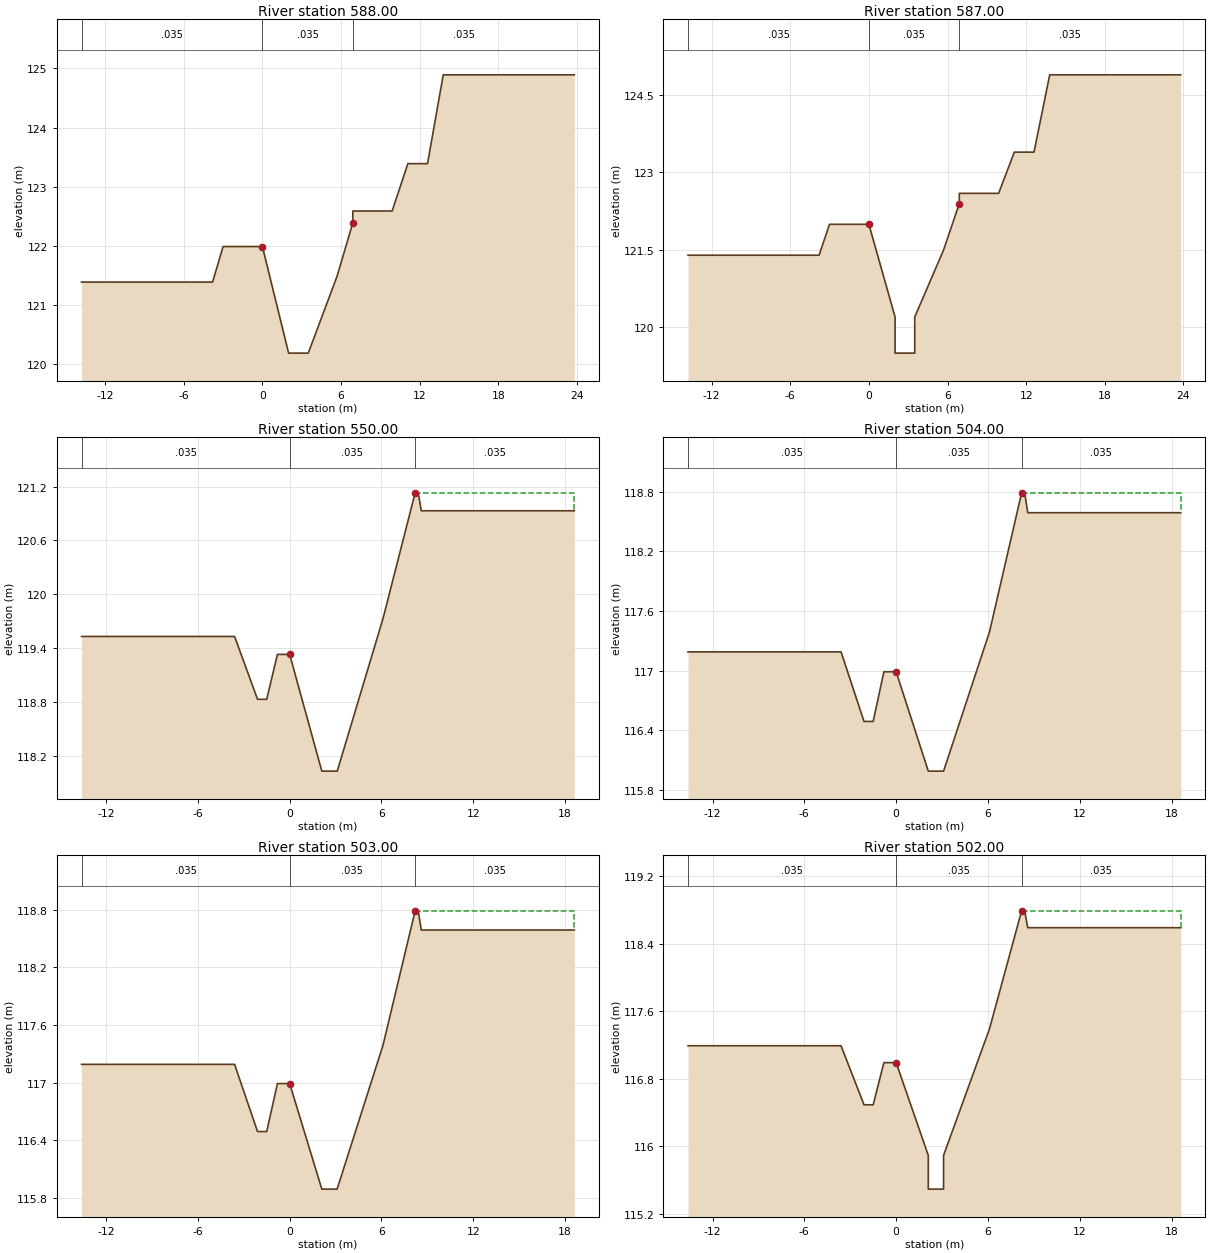
Type RM Length L Ch R = 1 ,588.00  ,1,1,1
BEGIN DESCRIPTION:
11.038
END DESCRIPTION:
#Sta/Elev= 14
   -13.8  121.39    -3.8  121.39      -3  121.99       0  121.99       2  120.19
     3.5  120.19     5.7  121.49     6.9  122.39     6.9  122.59     9.9  122.59
    11.1  123.39    12.6  123.39    13.8  124.89    23.8  124.89
#Mann= 3 , 0 , 0
   -13.8    .035       0       0    .035       0     6.9    .035       0
Bank Sta=0,6.9
XS Rating Curve= 0
Exp/Cntr=.3,.1

Type RM Length L Ch R = 1 ,587.00  ,37,37,37
BEGIN DESCRIPTION:
11.037
END DESCRIPTION:
#Sta/Elev= 16
   -13.8  121.39    -3.8  121.39      -3  121.99       0  121.99       2  120.19
       2  119.49     3.5  119.49     3.5  120.19     5.7  121.49     6.9  122.39
     6.9  122.59     9.9  122.59    11.1  123.39    12.6  123.39    13.8  124.89
    23.8  124.89
#Mann= 3 , 0 , 0
   -13.8    .035       0       0    .035       0     6.9    .035       0
Bank Sta=0,6.9
XS Rating Curve= 0
Exp/Cntr=.3,.1

Type RM Length L Ch R = 1 ,550.00  ,46,46,46
BEGIN DESCRIPTION:
11
END DESCRIPTION:
#Sta/Elev= 13
   -13.6  119.53    -3.6  119.53    -2.1  118.83    -1.5  118.83     -.8  119.33
       0  119.33     2.1  118.03    3.11  118.03     6.1  119.73     8.2  121.13
     8.4  121.13     8.6  120.93    18.6  120.93
#Mann= 3 , 0 , 0
   -13.6    .035       0       0    .035       0     8.2    .035       0
#XS Ineff= 2 , 0
               0  119.33     8.2          121.13
Permanent Ineff=
       F       F
Bank Sta=0,8.2
XS Rating Curve= 0
Exp/Cntr=.3,.1

Type RM Length L Ch R = 1 ,504.00  ,1,1,1
BEGIN DESCRIPTION:
10.004
END DESCRIPTION:
#Sta/Elev= 13
   -13.6  117.19    -3.6  117.19    -2.1  116.49    -1.5  116.49     -.8  116.99
       0  116.99     2.1  115.99     3.1  115.99     6.1  117.39     8.2  118.79
     8.4  118.79     8.6  118.59    18.6  118.59
#Mann= 3 , 0 , 0
   -13.6    .035       0       0    .035       0     8.2    .035       0
#XS Ineff= 2 , 0
               0  116.99     8.2          118.79
Permanent Ineff=
       F       F
Bank Sta=0,8.2
XS Rating Curve= 0
Exp/Cntr=.3,.1

Type RM Length L Ch R = 1 ,503.00  ,1,1,1
BEGIN DESCRIPTION:
10.003
END DESCRIPTION:
#Sta/Elev= 13
   -13.6  117.19    -3.6  117.19    -2.1  116.49    -1.5  116.49     -.8  116.99
       0  116.99     2.1  115.89     3.1  115.89     6.1  117.39     8.2  118.79
     8.4  118.79     8.6  118.59    18.6  118.59
#Mann= 3 , 0 , 0
   -13.6    .035       0       0    .035       0     8.2    .035       0
#XS Ineff= 2 , 0
               0  116.99     8.2          118.79
Permanent Ineff=
       F       F
Bank Sta=0,8.2
XS Rating Curve= 0
Exp/Cntr=.3,.1

Type RM Length L Ch R = 1 ,502.00  ,2,2,2
BEGIN DESCRIPTION:
10.002
END DESCRIPTION:
#Sta/Elev= 15
   -13.6  117.19    -3.6  117.19    -2.1  116.49    -1.5  116.49     -.8  116.99
       0  116.99     2.1  115.89     2.1  115.49     3.1  115.49     3.1  115.89
     6.1  117.39     8.2  118.79     8.4  118.79     8.6  118.59    18.6  118.59
#Mann= 3 , 0 , 0
   -13.6    .035       0       0    .035       0     8.2    .035       0
#XS Ineff= 2 , 0
               0  116.99     8.2          118.79
Permanent Ineff=
       F       F
Bank Sta=0,8.2
XS Rating Curve= 0
Exp/Cntr=.3,.1

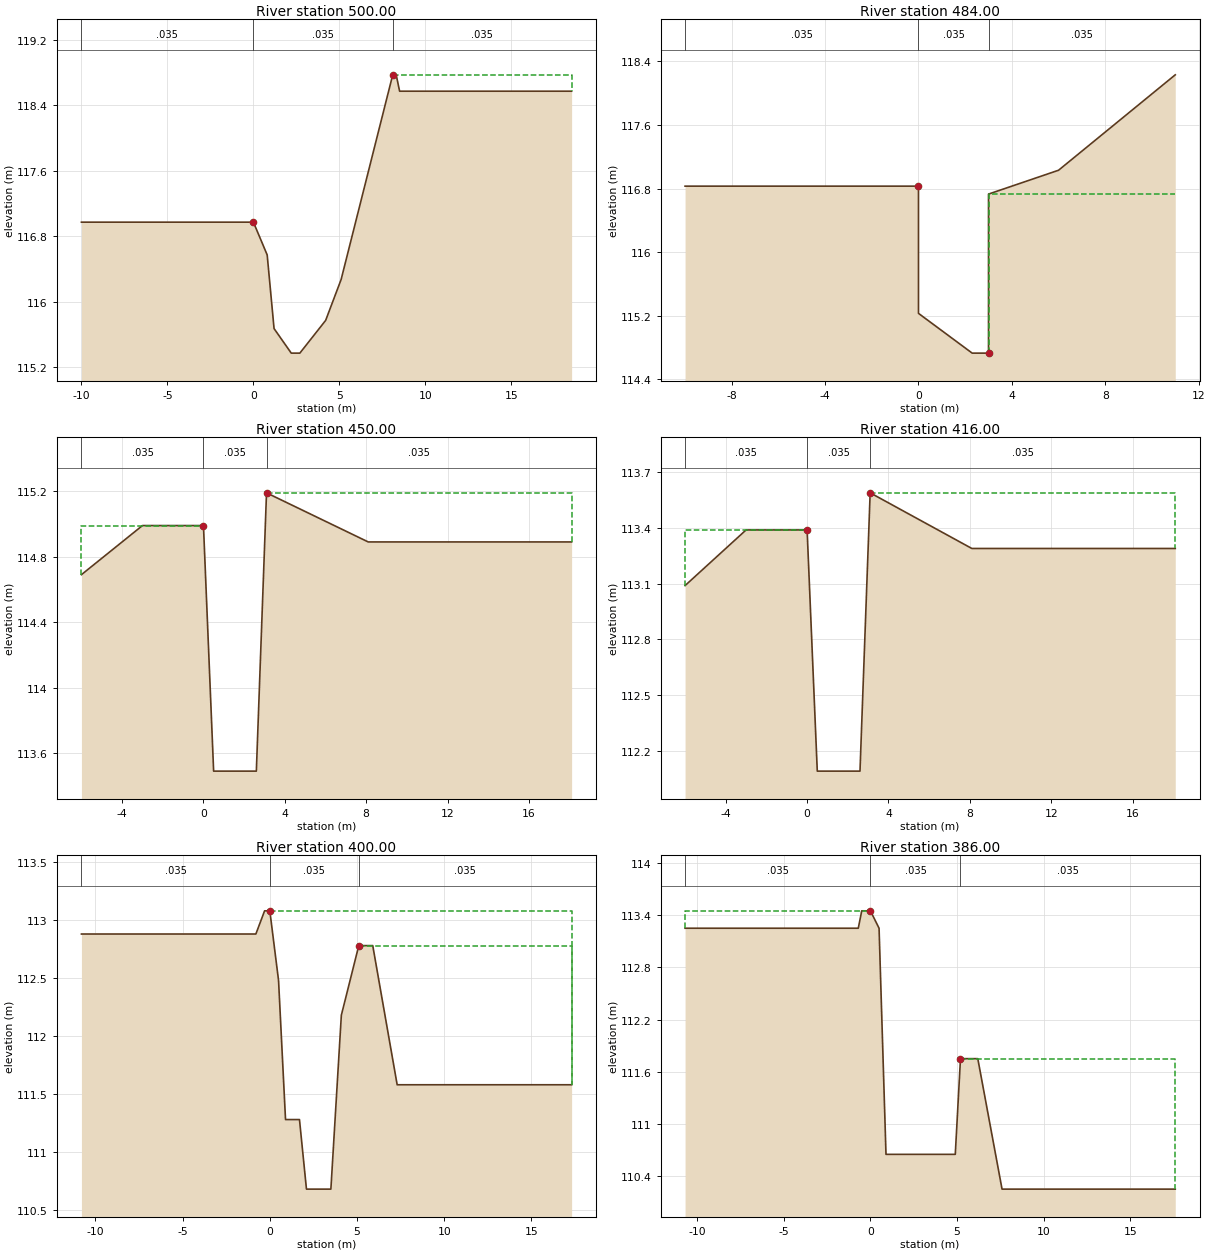
Type RM Length L Ch R = 1 ,500.00  ,16,16,16
BEGIN DESCRIPTION:
10
END DESCRIPTION:
#Sta/Elev= 12
     -10  116.97       0  116.97      .8  116.57     1.2  115.67     2.2  115.37
     2.7  115.37     4.2  115.77     5.1  116.27     8.1  118.77     8.3  118.77
     8.5  118.57    18.5  118.57
#Mann= 3 , 0 , 0
     -10    .035       0       0    .035       0     8.1    .035       0
#XS Ineff= 2 , 0
               0  116.97     8.1          118.77
Permanent Ineff=
       F       F
Bank Sta=0,8.1
XS Rating Curve= 0
Exp/Cntr=.3,.1

Type RM Length L Ch R = 1 ,484.00  ,34,34,34
BEGIN DESCRIPTION:
9.034
END DESCRIPTION:
#Sta/Elev= 8
     -10  116.83       0  116.83       0  115.23     2.3  114.73       3  114.73
       3  116.73       6  117.03      11  118.23
#Mann= 3 , 0 , 0
     -10    .035       0       0    .035       0       3    .035       0
#XS Ineff= 2 , 0
               0  116.83       3          116.73
Permanent Ineff=
       F       F
Bank Sta=0,3
XS Rating Curve= 0
Exp/Cntr=.3,.1

Type RM Length L Ch R = 1 ,450.00  ,34,34,34
BEGIN DESCRIPTION:
9
END DESCRIPTION:
#Sta/Elev= 8
      -6  114.69      -3  114.99       0  114.99      .5  113.49     2.6  113.49
     3.1  115.19     8.1  114.89    18.1  114.89
#Mann= 3 , 0 , 0
      -6    .035       0       0    .035       0     3.1    .035       0
#XS Ineff= 2 , 0
               0  114.99     3.1          115.19
Permanent Ineff=
       F       F
Bank Sta=0,3.1
XS Rating Curve= 0
Exp/Cntr=.3,.1

Type RM Length L Ch R = 1 ,416.00  ,16,16,16
BEGIN DESCRIPTION:
8.016
END DESCRIPTION:
#Sta/Elev= 8
      -6  113.09      -3  113.39       0  113.39      .5  112.09     2.6  112.09
     3.1  113.59     8.1  113.29    18.1  113.29
#Mann= 3 , 0 , 0
      -6    .035       0       0    .035       0     3.1    .035       0
#XS Ineff= 2 , 0
               0  113.39     3.1          113.59
Permanent Ineff=
       F       F
Bank Sta=0,3.1
XS Rating Curve= 0
Exp/Cntr=.3,.1

Type RM Length L Ch R = 1 ,400.00  ,14,14,14
BEGIN DESCRIPTION:
8
END DESCRIPTION:
#Sta/Elev= 14
   -10.8  112.88     -.8  112.88     -.3  113.08       0  113.08      .5  112.48
      .9  111.28     1.7  111.28     2.1  110.68     3.5  110.68     4.1  112.18
     5.1  112.78     5.9  112.78     7.3  111.58    17.3  111.58
#Mann= 3 , 0 , 0
   -10.8    .035       0       0    .035       0     5.1    .035       0
#XS Ineff= 2 , 0
       0       0  113.08     5.1       0  112.78
Permanent Ineff=
       F       F
Bank Sta=0,5.1
XS Rating Curve= 0
Exp/Cntr=.3,.1

Type RM Length L Ch R = 1 ,386.00  ,1,1,1
BEGIN DESCRIPTION:
7.036
END DESCRIPTION:
#Sta/Elev= 11
   -10.7  113.25     -.7  113.25     -.5  113.45       0  113.45      .5  113.25
      .9  110.65     4.9  110.65     5.2  111.75     6.2  111.75     7.6  110.25
    17.6  110.25
#Mann= 3 , 0 , 0
   -10.7    .035       0       0    .035       0     5.2    .035       0
#XS Ineff= 2 , 0
               0  113.45     5.2          111.75
Permanent Ineff=
       F       F
Bank Sta=0,5.2
XS Rating Curve= 0
Exp/Cntr=.3,.1

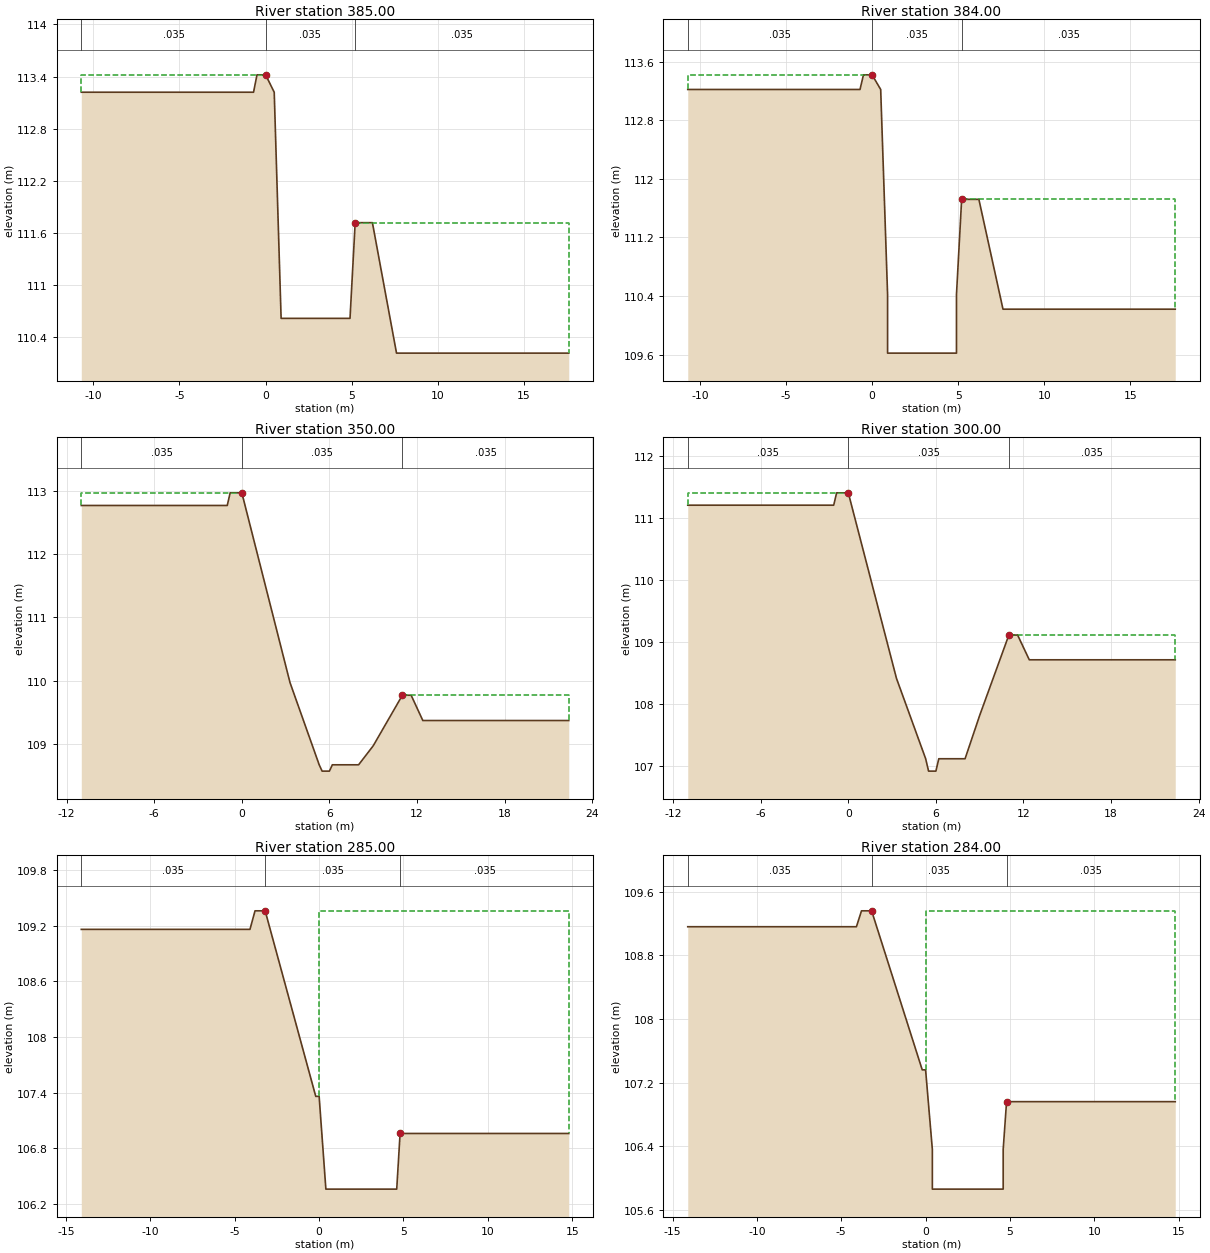
Type RM Length L Ch R = 1 ,385.00  ,1,1,1
BEGIN DESCRIPTION:
7.035
END DESCRIPTION:
#Sta/Elev= 11
   -10.7  113.22     -.7  113.22     -.5  113.42       0  113.42      .5  113.22
      .9  110.62     4.9  110.62     5.2  111.72     6.2  111.72     7.6  110.22
    17.6  110.22
#Mann= 3 , 0 , 0
   -10.7    .035       0       0    .035       0     5.2    .035       0
#XS Ineff= 2 , 0
               0  113.42     5.2          111.72
Permanent Ineff=
       F       F
Bank Sta=0,5.2
XS Rating Curve= 0
Exp/Cntr=.3,.1

Type RM Length L Ch R = 1 ,384.00  ,34,34,34
BEGIN DESCRIPTION:
7.034
END DESCRIPTION:
#Sta/Elev= 13
   -10.7  113.22     -.7  113.22     -.5  113.42       0  113.42      .5  113.22
      .9  110.42      .9  109.62     4.9  109.62     4.9  110.42     5.2  111.72
     6.2  111.72     7.6  110.22    17.6  110.22
#Mann= 3 , 0 , 0
   -10.7    .035       0       0    .035       0     5.2    .035       0
#XS Ineff= 2 , 0
               0  113.42     5.2          111.72
Permanent Ineff=
       F       F
Bank Sta=0,5.2
XS Rating Curve= 0
Exp/Cntr=.3,.1

Type RM Length L Ch R = 1 ,350.00  ,50,50,50
BEGIN DESCRIPTION:
7
END DESCRIPTION:
#Sta/Elev= 15
     -11  112.77      -1  112.77     -.8  112.97       0  112.97     3.3  109.97
     5.3  108.67     5.5  108.57       6  108.57     6.2  108.67       8  108.67
       9  108.97      11  109.77    11.6  109.77    12.4  109.37    22.4  109.37
#Mann= 3 , 0 , 0
     -11    .035       0       0    .035       0      11    .035       0
#XS Ineff= 2 , 0
               0  112.97      11          109.77
Permanent Ineff=
       F       F
Bank Sta=0,11
XS Rating Curve= 0
Exp/Cntr=.3,.1

Type RM Length L Ch R = 1 ,300.00  ,15,15,15
BEGIN DESCRIPTION:
6
END DESCRIPTION:
#Sta/Elev= 15
     -11  111.21      -1  111.21     -.8  111.41       0  111.41     3.3  108.41
     5.3  107.11     5.5  106.91       6  106.91     6.2  107.11       8  107.11
       9  107.81      11  109.11    11.6  109.11    12.4  108.71    22.4  108.71
#Mann= 3 , 0 , 0
     -11    .035       0       0    .035       0      11    .035       0
#XS Ineff= 2 , 0
               0  111.41      11          109.11
Permanent Ineff=
       F       F
Bank Sta=0,11
XS Rating Curve= 0
Exp/Cntr=.3,.1

Type RM Length L Ch R = 1 ,285.00  ,1,1,1
BEGIN DESCRIPTION:
5.035
END DESCRIPTION:
#Sta/Elev= 10
   -14.1  109.16    -4.1  109.16    -3.8  109.36    -3.2  109.36     -.2  107.36
       0  107.36      .4  106.36     4.6  106.36     4.8  106.96    14.8  106.96
#Mann= 3 , 0 , 0
   -14.1    .035       0    -3.2    .035       0     4.8    .035       0
#XS Ineff= 2 , 0
       0    -3.2  109.36     4.8       0  106.96
Permanent Ineff=
       F       F
Bank Sta=-3.2,4.8
XS Rating Curve= 0
Exp/Cntr=.3,.1

Type RM Length L Ch R = 1 ,284.00  ,1,1,1
BEGIN DESCRIPTION:
5.034
END DESCRIPTION:
#Sta/Elev= 12
   -14.1  109.16    -4.1  109.16    -3.8  109.36    -3.2  109.36     -.2  107.36
       0  107.36      .4  106.36      .4  105.86     4.6  105.86     4.6  106.36
     4.8  106.96    14.8  106.96
#Mann= 3 , 0 , 0
   -14.1    .035       0    -3.2    .035       0     4.8    .035       0
#XS Ineff= 2 , 0
       0    -3.2  109.36     4.8       0  106.96
Permanent Ineff=
       F       F
Bank Sta=-3.2,4.8
XS Rating Curve= 0
Exp/Cntr=.3,.1

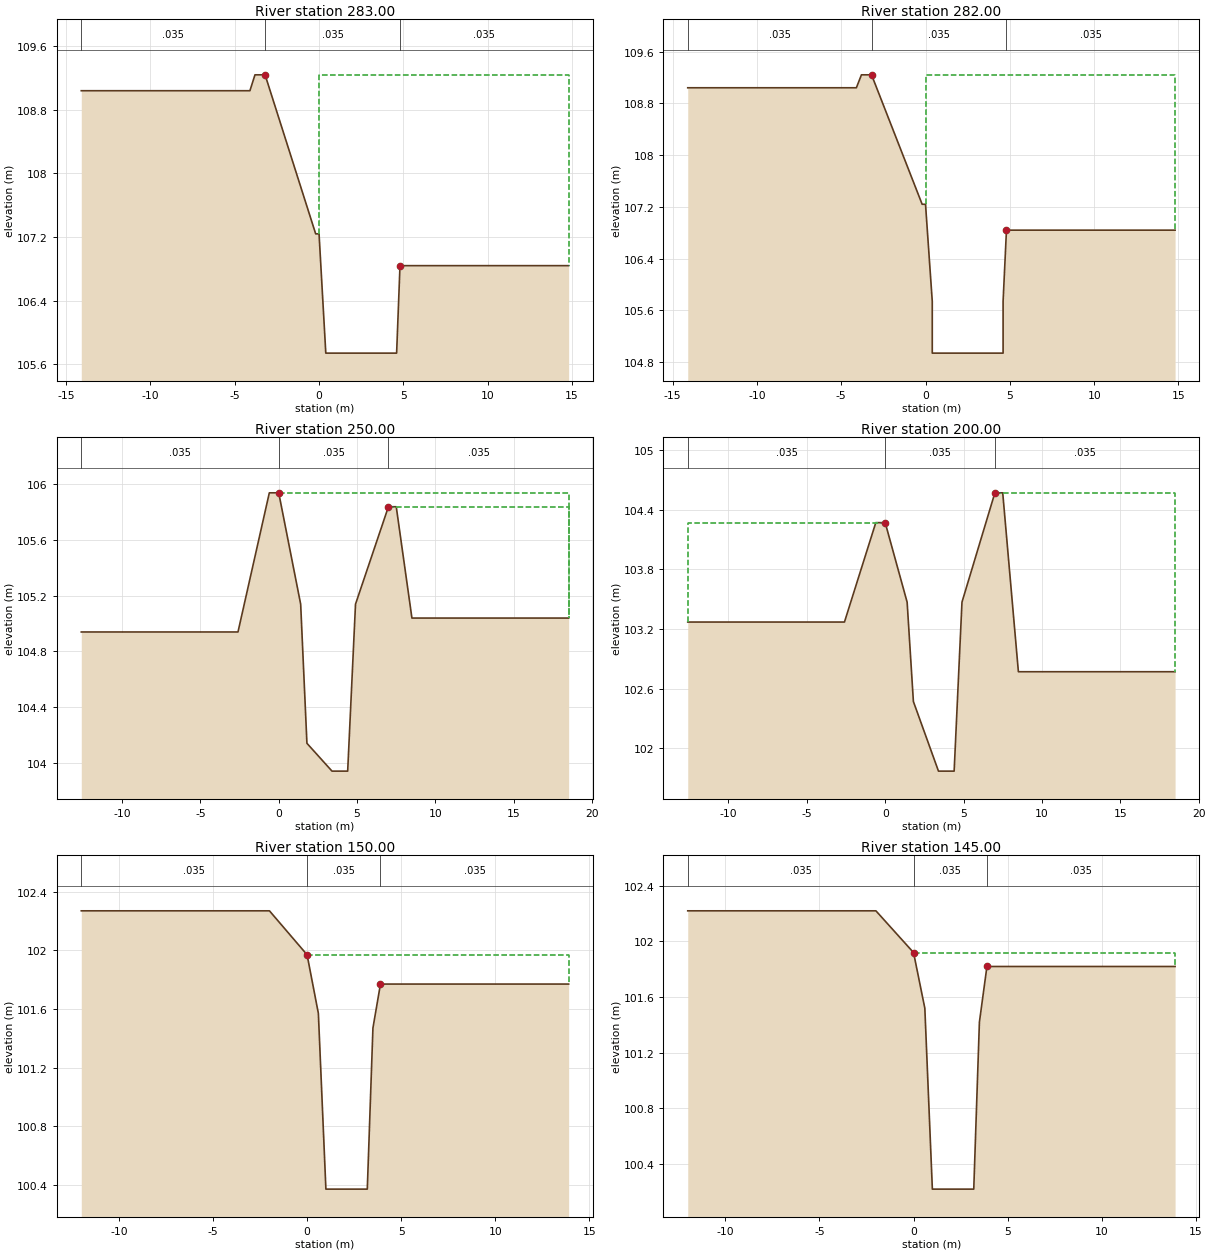
Type RM Length L Ch R = 1 ,283.00  ,1,1,1
BEGIN DESCRIPTION:
5.033
END DESCRIPTION:
#Sta/Elev= 10
   -14.1  109.04    -4.1  109.04    -3.8  109.24    -3.2  109.24     -.2  107.24
       0  107.24      .4  105.74     4.6  105.74     4.8  106.84    14.8  106.84
#Mann= 3 , 0 , 0
   -14.1    .035       0    -3.2    .035       0     4.8    .035       0
#XS Ineff= 2 , 0
       0    -3.2  109.24     4.8       0  106.84
Permanent Ineff=
       F       F
Bank Sta=-3.2,4.8
XS Rating Curve= 0
Exp/Cntr=.3,.1

Type RM Length L Ch R = 1 ,282.00  ,32,32,32
BEGIN DESCRIPTION:
5.032
END DESCRIPTION:
#Sta/Elev= 12
   -14.1  109.04    -4.1  109.04    -3.8  109.24    -3.2  109.24     -.2  107.24
       0  107.24      .4  105.74      .4  104.94     4.6  104.94     4.6  105.74
     4.8  106.84    14.8  106.84
#Mann= 3 , 0 , 0
   -14.1    .035       0    -3.2    .035       0     4.8    .035       0
#XS Ineff= 2 , 0
       0    -3.2  109.24     4.8       0  106.84
Permanent Ineff=
       F       F
Bank Sta=-3.2,4.8
XS Rating Curve= 0
Exp/Cntr=.3,.1

Type RM Length L Ch R = 1 ,250.00  ,50,50,50
BEGIN DESCRIPTION:
5
END DESCRIPTION:
#Sta/Elev= 13
   -12.6  104.94    -2.6  104.94     -.6  105.94       0  105.94     1.4  105.14
     1.8  104.14     3.4  103.94     4.4  103.94     4.9  105.14       7  105.84
     7.5  105.84     8.5  105.04    18.5  105.04
#Mann= 3 , 0 , 0
   -12.6    .035       0       0    .035       0       7    .035       0
#XS Ineff= 2 , 0
       0       0  105.94       7       0  105.84
Permanent Ineff=
       F       F
Bank Sta=0,7
XS Rating Curve= 0
Exp/Cntr=.3,.1

Type RM Length L Ch R = 1 ,200.00  ,50,50,50
BEGIN DESCRIPTION:
4
END DESCRIPTION:
#Sta/Elev= 13
   -12.6  103.27    -2.6  103.27     -.6  104.27       0  104.27     1.4  103.47
     1.8  102.47     3.4  101.77     4.4  101.77     4.9  103.47       7  104.57
     7.5  104.57     8.5  102.77    18.5  102.77
#Mann= 3 , 0 , 0
   -12.6    .035       0       0    .035       0       7    .035       0
#XS Ineff= 2 , 0
               0  104.27       7          104.57
Permanent Ineff=
       F       F
Bank Sta=0,7
XS Rating Curve= 0
Exp/Cntr=.3,.1

Type RM Length L Ch R = 1 ,150.00  ,5,5,5
BEGIN DESCRIPTION:
3
END DESCRIPTION:
#Sta/Elev= 9
     -12  102.27      -2  102.27       0  101.97      .6  101.57       1  100.37
     3.2  100.37     3.5  101.47     3.9  101.77    13.9  101.77
#Mann= 3 , 0 , 0
     -12    .035       0       0    .035       0     3.9    .035       0
#XS Ineff= 2 , 0
       0       0  101.97     3.9       0  101.77
Permanent Ineff=
       F       F
Bank Sta=0,3.9
XS Rating Curve= 0
Exp/Cntr=.3,.1

Type RM Length L Ch R = 1 ,145.00  ,45,45,45
BEGIN DESCRIPTION:
2.045
END DESCRIPTION:
#Sta/Elev= 9
     -12  102.22      -2  102.22       0  101.92      .6  101.52       1  100.22
     3.2  100.22     3.5  101.42     3.9  101.82    13.9  101.82
#Mann= 3 , 0 , 0
     -12    .035       0       0    .035       0     3.9    .035       0
#XS Ineff= 2 , 0
       0       0  101.92     3.9       0  101.82
Permanent Ineff=
       F       F
Bank Sta=0,3.9
XS Rating Curve= 0
Exp/Cntr=.3,.1

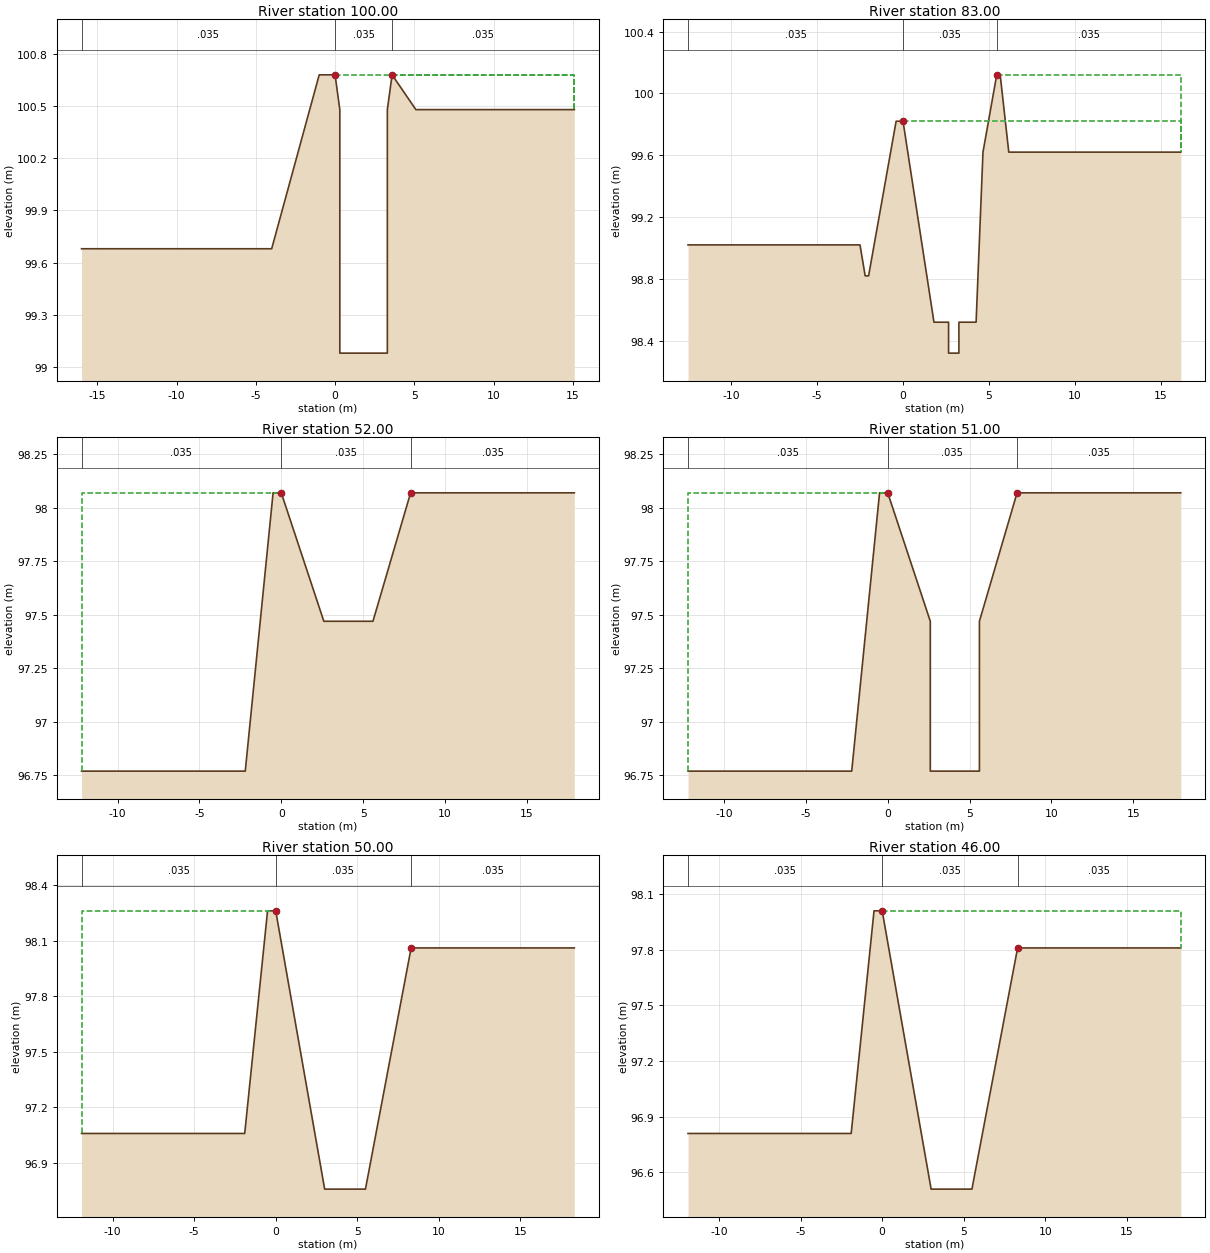
Type RM Length L Ch R = 1 ,100.00  ,17,17,17
BEGIN DESCRIPTION:
2
END DESCRIPTION:
#Sta/Elev= 12
     -16   99.68      -6   99.68      -4   99.68      -1  100.68       0  100.68
      .3  100.48      .3   99.08     3.3   99.08     3.3  100.48     3.6  100.68
     5.1  100.48    15.1  100.48
#Mann= 3 , 0 , 0
     -16    .035       0       0    .035       0     3.6    .035       0
#XS Ineff= 2 , 0
       0       0  100.68     3.6       0  100.68
Permanent Ineff=
       F       F
Bank Sta=0,3.6
XS Rating Curve= 0
Exp/Cntr=.3,.1

Type RM Length L Ch R = 1 ,83.00   ,31,31,31
BEGIN DESCRIPTION:
1.033
END DESCRIPTION:
#Sta/Elev= 17
   -12.5   99.02    -2.5   99.02    -2.2   98.82      -2   98.82     -.4   99.82
       0   99.82     1.8   98.52    2.65   98.52    2.65   98.32    3.25   98.32
    3.25   98.52    4.25   98.52    4.65   99.62    5.45  100.12    5.65  100.12
    6.15   99.62   16.15   99.62
#Mann= 3 , 0 , 0
   -12.5    .035       0       0    .035       0    5.45    .035       0
#XS Ineff= 2 , 0
       0       0   99.82    5.45       0  100.12
Permanent Ineff=
       F       F
Bank Sta=0,5.45
XS Rating Curve= 0
Exp/Cntr=.3,.1

Type RM Length L Ch R = 1 ,52.00   ,1,1,1
BEGIN DESCRIPTION:
1.002
END DESCRIPTION:
#Sta/Elev= 8
   -12.2   96.77    -2.2   96.77     -.5   98.07       0   98.07     2.6   97.47
     5.6   97.47     7.9   98.07    17.9   98.07
#Mann= 3 , 0 , 0
   -12.2    .035       0       0    .035       0     7.9    .035       0
#XS Ineff= 2 , 0
               0   98.07     7.9           98.07
Permanent Ineff=
       F       F
Bank Sta=0,7.9
XS Rating Curve= 0
Exp/Cntr=.3,.1

Type RM Length L Ch R = 1 ,51.00   ,1,1,1
BEGIN DESCRIPTION:
1.001
END DESCRIPTION:
#Sta/Elev= 10
   -12.2   96.77    -2.2   96.77     -.5   98.07       0   98.07     2.6   97.47
     2.6   96.77     5.6   96.77     5.6   97.47     7.9   98.07    17.9   98.07
#Mann= 3 , 0 , 0
   -12.2    .035       0       0    .035       0     7.9    .035       0
#XS Ineff= 2 , 0
               0   98.07     7.9           98.07
Permanent Ineff=
       F       F
Bank Sta=0,7.9
XS Rating Curve= 0
Exp/Cntr=.3,.1

Type RM Length L Ch R = 1 ,50.00   ,4,4,4
BEGIN DESCRIPTION:
1
END DESCRIPTION:
#Sta/Elev= 8
   -11.9   97.06    -1.9   97.06     -.5   98.26       0   98.26       3   96.76
     5.5   96.76     8.3   98.06    18.3   98.06
#Mann= 3 , 0 , 0
   -11.9    .035       0       0    .035       0     8.3    .035       0
#XS Ineff= 2 , 0
               0   98.26     8.3           98.06
Permanent Ineff=
       F       F
Bank Sta=0,8.3
XS Rating Curve= 0
Exp/Cntr=.3,.1

Type RM Length L Ch R = 1 ,46.00   ,1,1,1
BEGIN DESCRIPTION:
0.046
END DESCRIPTION:
#Sta/Elev= 8
   -11.9   96.81    -1.9   96.81     -.5   98.01       0   98.01       3   96.51
     5.5   96.51     8.3   97.81    18.3   97.81
#Mann= 3 , 0 , 0
   -11.9    .035       0       0    .035       0     8.3    .035       0
#XS Ineff= 2 , 0
       0       0   98.01     8.3       0   97.81
Permanent Ineff=
       F       F
Bank Sta=0,8.3
XS Rating Curve= 0
Exp/Cntr=.3,.1

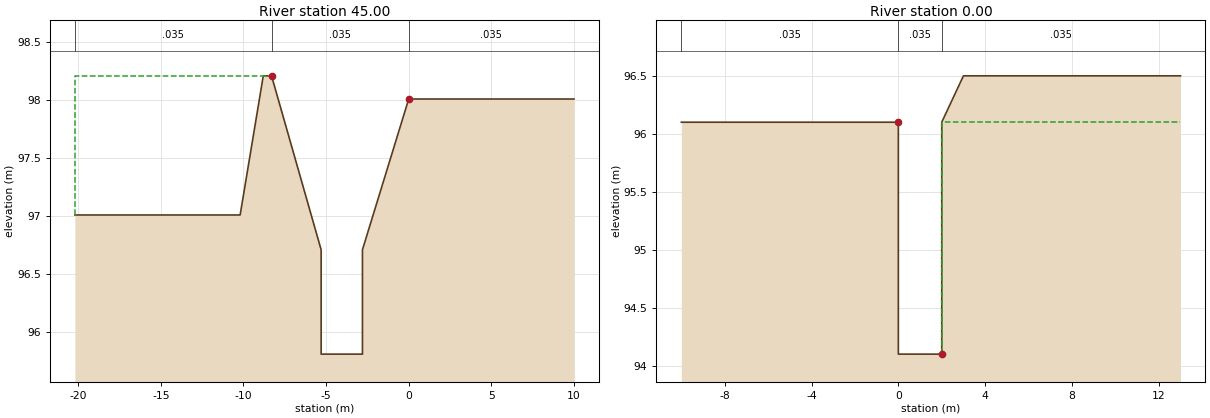
Type RM Length L Ch R = 1 ,45.00   ,45,45,45
BEGIN DESCRIPTION:
0.045
END DESCRIPTION:
#Sta/Elev= 10
   -20.2   97.01   -10.2   97.01    -8.8   98.21    -8.3   98.21    -5.3   96.71
    -5.3   95.81    -2.8   95.81    -2.8   96.71       0   98.01      10   98.01
#Mann= 3 , 0 , 0
   -20.2    .035       0    -8.3    .035       0       0    .035       0
#XS Ineff= 2 , 0
            -8.3   98.21       0           98.01
Permanent Ineff=
       F       F
Bank Sta=-8.3,0
XS Rating Curve= 0
Exp/Cntr=.3,.1

Type RM Length L Ch R = 1 ,0.00    ,0,0,0
BEGIN DESCRIPTION:
0
END DESCRIPTION:
#Sta/Elev= 7
     -10    96.1       0    96.1       0    94.1       2    94.1       2    96.1
       3    96.5      13    96.5
#Mann= 3 , 0 , 0
     -10    .035       0       0    .035       0       2    .035       0
#XS Ineff= 2 , 0
               0    96.1       2            96.1
Permanent Ineff=
       F       F
Bank Sta=0,2
XS Rating Curve= 0
Exp/Cntr=.3,.1

Chan Stop Cuts=-1