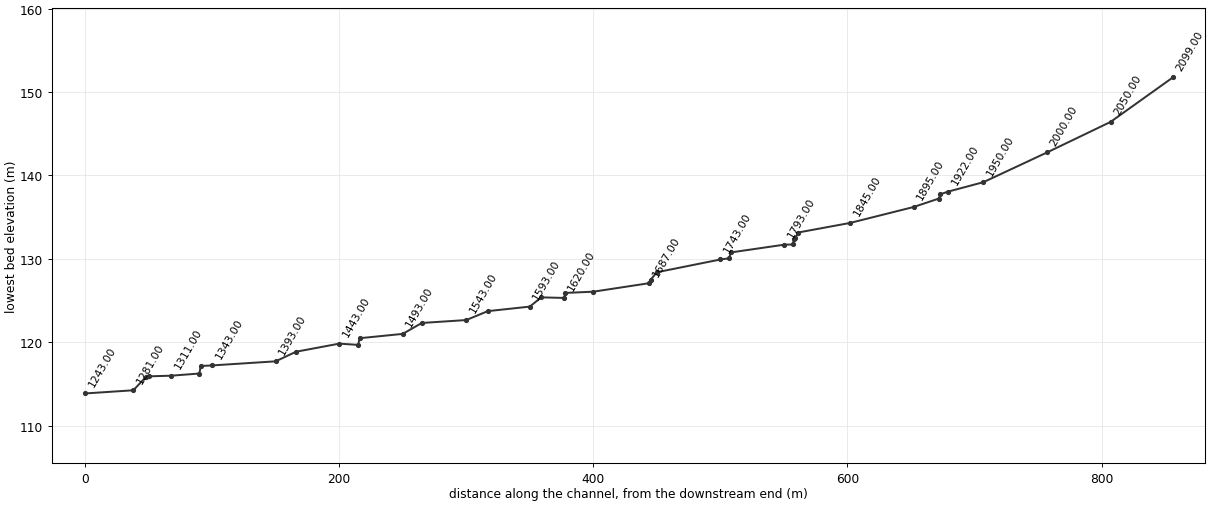
--- MSC.prj (project) ---

Proj Title=MSC
Current Plan=p01
Default Exp/Contr=.3,.1
SI Units
Geom File=g01
Flow File=f01
Plan File=p01
Y Axis Title=Elevation
X Axis Title(PF)=Main Channel Distance
X Axis Title(XS)=Station
BEGIN DESCRIPTION:
           BACK WATER COMPUTATION
      APPLICATION OF HEC-2 BY Samju Construction Engineering
      namshim-cheon: 10,20,30,50,80 yr
END DESCRIPTION:
DSS Export Rating Curves= 0
DSS Export Rating Curve Sorted= 0
DSS Export Volume Flow Curves= 0
DXF OffsetX= 0
DXF OffsetY= 0
DXF ScaleX= 1
DXF ScaleY= 10

--- MSC.p01 (plan) ---

Plan Title=Imported Plan 01
Version=Version 3.0.1  Mar 2001
Short Identifier=Imported Pla
Geom File=g01
Flow File=f01
Subcritical Flow
K Sum by GR= 0
Std Step Tol= 0.003
Critical Tol= 0.003
Num of Std Step Trials= 20
Max Error Tol= 0.1
Flow Tol Ratio= 0.001
Split Flow NTrial= 30
Split Flow Tol= 0.02
Split Flow Ratio= 0.02
Log Output Level= 0
Friction Slope Method= 1
Unsteady Friction Slope Method= 2
Parabolic Critical Depth
Global Vel Dist= 0 , 0 , 0
Global Log Level= 0
CheckData=True
Encroach Param=-1 ,0,0, 0
Computation Interval=1HOUR
Output Interval=1HOUR
Run HTab= 0
Run UNet= 0
Run PostProcess= 0
UNET Theta= 1
UNET ZTol= 0.02
UNET ZSATol= 0.1
UNET MxIter= 20
UNET MaxInSteps= 20
UNET DtIC= 0
UNET DtMin= 0
UNET MaxCRTS= 20
UNET WFStab= 2
UNET SFStab= 1
UNET WFX= 1
UNET SFX= 1
UNET Convert EG Bridges=-1
UNET Use Existing IB Tables=-1
Instantaneous Interval=1HOUR
Write IC File= 0
Write Velocity= 0
Write Detailed= 0

--- MSC.f01 (steady flow) ---

Flow Title=Imported Flow 01
Version=Version 3.0.1  Mar 2001
Number of Profiles= 5
Profile Names=10YR,20YR,30YR,50YR,80YR
River Rch & RM=RIVER-1,Reach-1         ,2099.00
    13.2   14.53    15.3   16.28   17.19
River Rch & RM=RIVER-1,Reach-1         ,1093.00
   27.85   30.68   32.33   34.42   36.34
Boundary for River Rch & Prof#=RIVER-1,Reach-1         , 1
Up Type= 0
Dn Type= 3
Dn Slope=.045
Boundary for River Rch & Prof#=RIVER-1,Reach-1         , 2
Up Type= 0
Dn Type= 3
Dn Slope=.045
Boundary for River Rch & Prof#=RIVER-1,Reach-1         , 3
Up Type= 0
Dn Type= 3
Dn Slope=.045
Boundary for River Rch & Prof#=RIVER-1,Reach-1         , 4
Up Type= 0
Dn Type= 3
Dn Slope=.045
Boundary for River Rch & Prof#=RIVER-1,Reach-1         , 5
Up Type= 0
Dn Type= 3
Dn Slope=.045
DSS Import GetInterval= 0
DSS Import GetPeak= 0
DSS Import FillOption= 0

--- MSC.g01 (geometry) ---

Geom Title=Imported Geom 01
Version=Version 3.0.1  Mar 2001

River Reach=RIVER-1         ,Reach-1
Reach XY= 2
              .5             .95              .5             .05

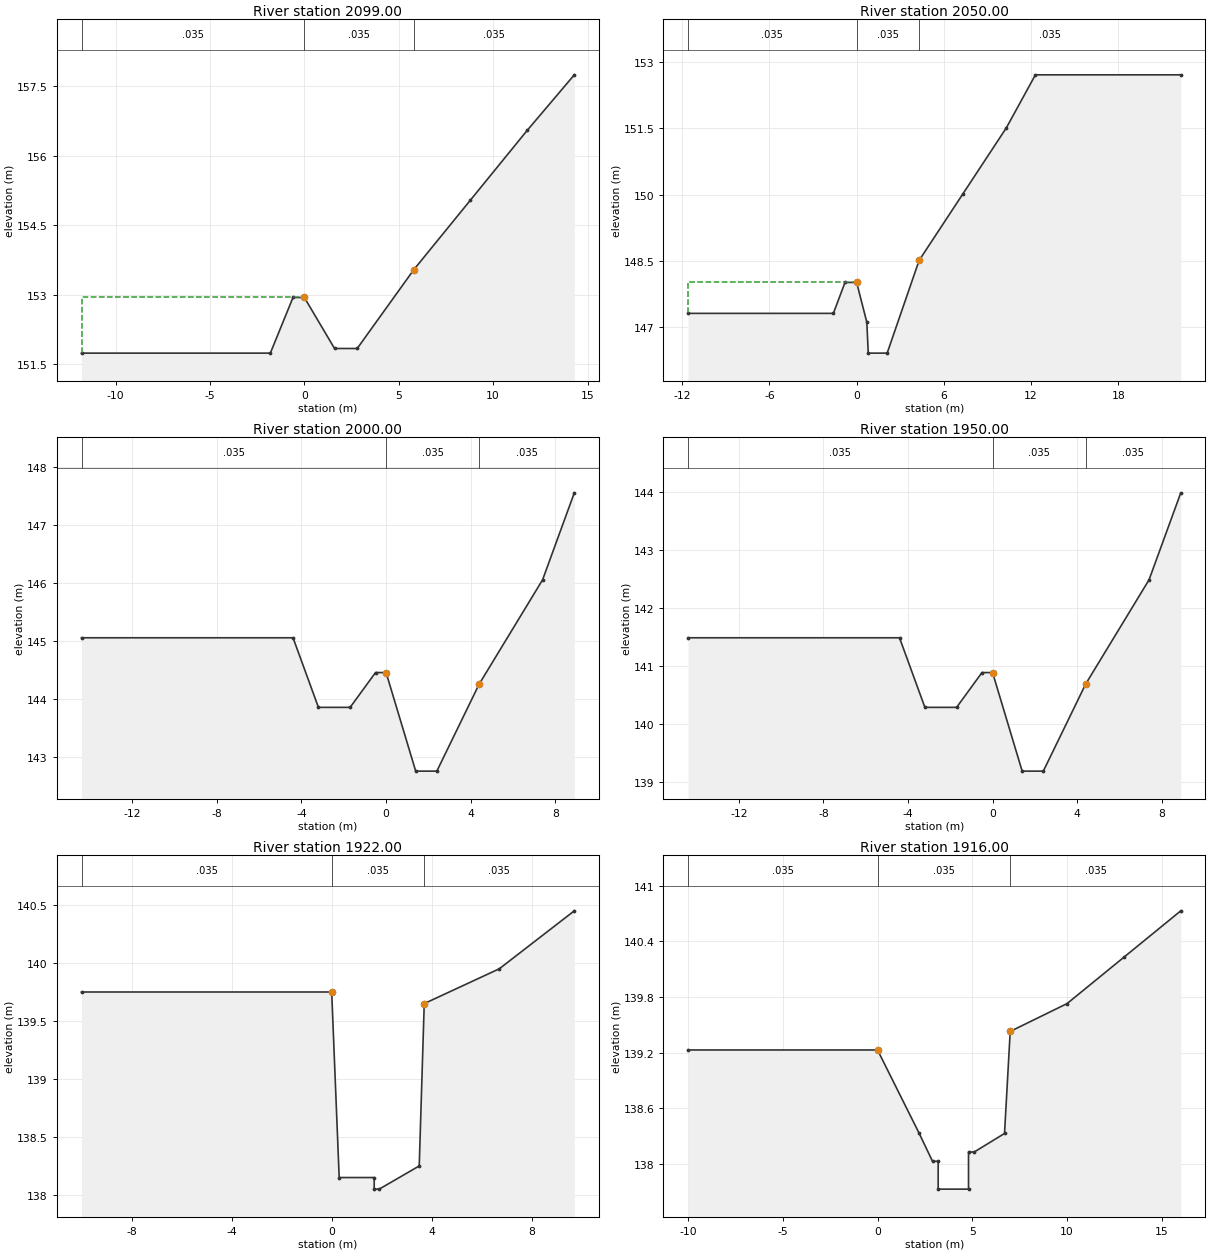
Type RM Length L Ch R = 1 ,2099.00 ,49,49,49
BEGIN DESCRIPTION:
40.049
END DESCRIPTION:
#Sta/Elev= 10
   -11.8  151.74    -1.8  151.74     -.6  152.94       0  152.94     1.6  151.84
     2.8  151.84     5.8  153.54     8.8  155.04    11.8  156.54    14.3  157.74
#Mann= 3 , 0 , 0
   -11.8    .035       0       0    .035       0     5.8    .035       0
#XS Ineff= 2 , 0
               0  152.94     5.8          153.54
Permanent Ineff=
       F       F
Bank Sta=0,5.8
XS Rating Curve= 0
Exp/Cntr=.3,.1

Type RM Length L Ch R = 1 ,2050.00 ,50,50,50
BEGIN DESCRIPTION:
40
END DESCRIPTION:
#Sta/Elev= 12
   -11.6  147.31    -1.6  147.31     -.8  148.01       0  148.01      .7  147.11
      .8  146.41     2.1  146.41     4.3  148.51     7.3  150.01    10.3  151.51
    12.3  152.71    22.3  152.71
#Mann= 3 , 0 , 0
   -11.6    .035       0       0    .035       0     4.3    .035       0
#XS Ineff= 2 , 0
               0  148.01     4.3          148.51
Permanent Ineff=
       F       F
Bank Sta=0,4.3
XS Rating Curve= 0
Exp/Cntr=.3,.1

Type RM Length L Ch R = 1 ,2000.00 ,50,50,50
BEGIN DESCRIPTION:
39
END DESCRIPTION:
#Sta/Elev= 11
   -14.4  145.05    -4.4  145.05    -3.2  143.85    -1.7  143.85     -.5  144.45
       0  144.45     1.4  142.75     2.4  142.75     4.4  144.25     7.4  146.05
     8.9  147.55
#Mann= 3 , 0 , 0
   -14.4    .035       0       0    .035       0     4.4    .035       0
#XS Ineff= 2 , 0
               0  144.45     4.4          144.25
Permanent Ineff=
       F       F
Bank Sta=0,4.4
XS Rating Curve= 0
Exp/Cntr=.3,.1

Type RM Length L Ch R = 1 ,1950.00 ,28,28,28
BEGIN DESCRIPTION:
38
END DESCRIPTION:
#Sta/Elev= 11
   -14.4  141.49    -4.4  141.49    -3.2  140.29    -1.7  140.29     -.5  140.89
       0  140.89     1.4  139.19     2.4  139.19     4.4  140.69     7.4  142.49
     8.9  143.99
#Mann= 3 , 0 , 0
   -14.4    .035       0       0    .035       0     4.4    .035       0
#XS Ineff= 2 , 0
               0  140.89     4.4          140.69
Permanent Ineff=
       F       F
Bank Sta=0,4.4
XS Rating Curve= 0
Exp/Cntr=.3,.1

Type RM Length L Ch R = 1 ,1922.00 ,6,6,6
BEGIN DESCRIPTION:
37.027
END DESCRIPTION:
#Sta/Elev= 10
     -10  139.75       0  139.75      .3  138.15     1.7  138.15     1.7  138.05
     1.9  138.05     3.5  138.25     3.7  139.65     6.7  139.95     9.7  140.45
#Mann= 3 , 0 , 0
     -10    .035       0       0    .035       0     3.7    .035       0
#XS Ineff= 2 , 0
               0  139.75     3.7          139.65
Permanent Ineff=
       F       F
Bank Sta=0,3.7
XS Rating Curve= 0
Exp/Cntr=.3,.1

Type RM Length L Ch R = 1 ,1916.00 ,1,1,1
BEGIN DESCRIPTION:
37.021
END DESCRIPTION:
#Sta/Elev= 14
     -10  139.23       0  139.23     2.2  138.33     2.9  138.03     3.2  138.03
     3.2  137.73     4.8  137.73     4.8  138.13     5.1  138.13     6.7  138.33
       7  139.43      10  139.73      13  140.23      16  140.73
#Mann= 3 , 0 , 0
     -10    .035       0       0    .035       0       7    .035       0
#XS Ineff= 2 , 0
               0  139.23       7          139.43
Permanent Ineff=
       F       F
Bank Sta=0,7
XS Rating Curve= 0
Exp/Cntr=.3,.1

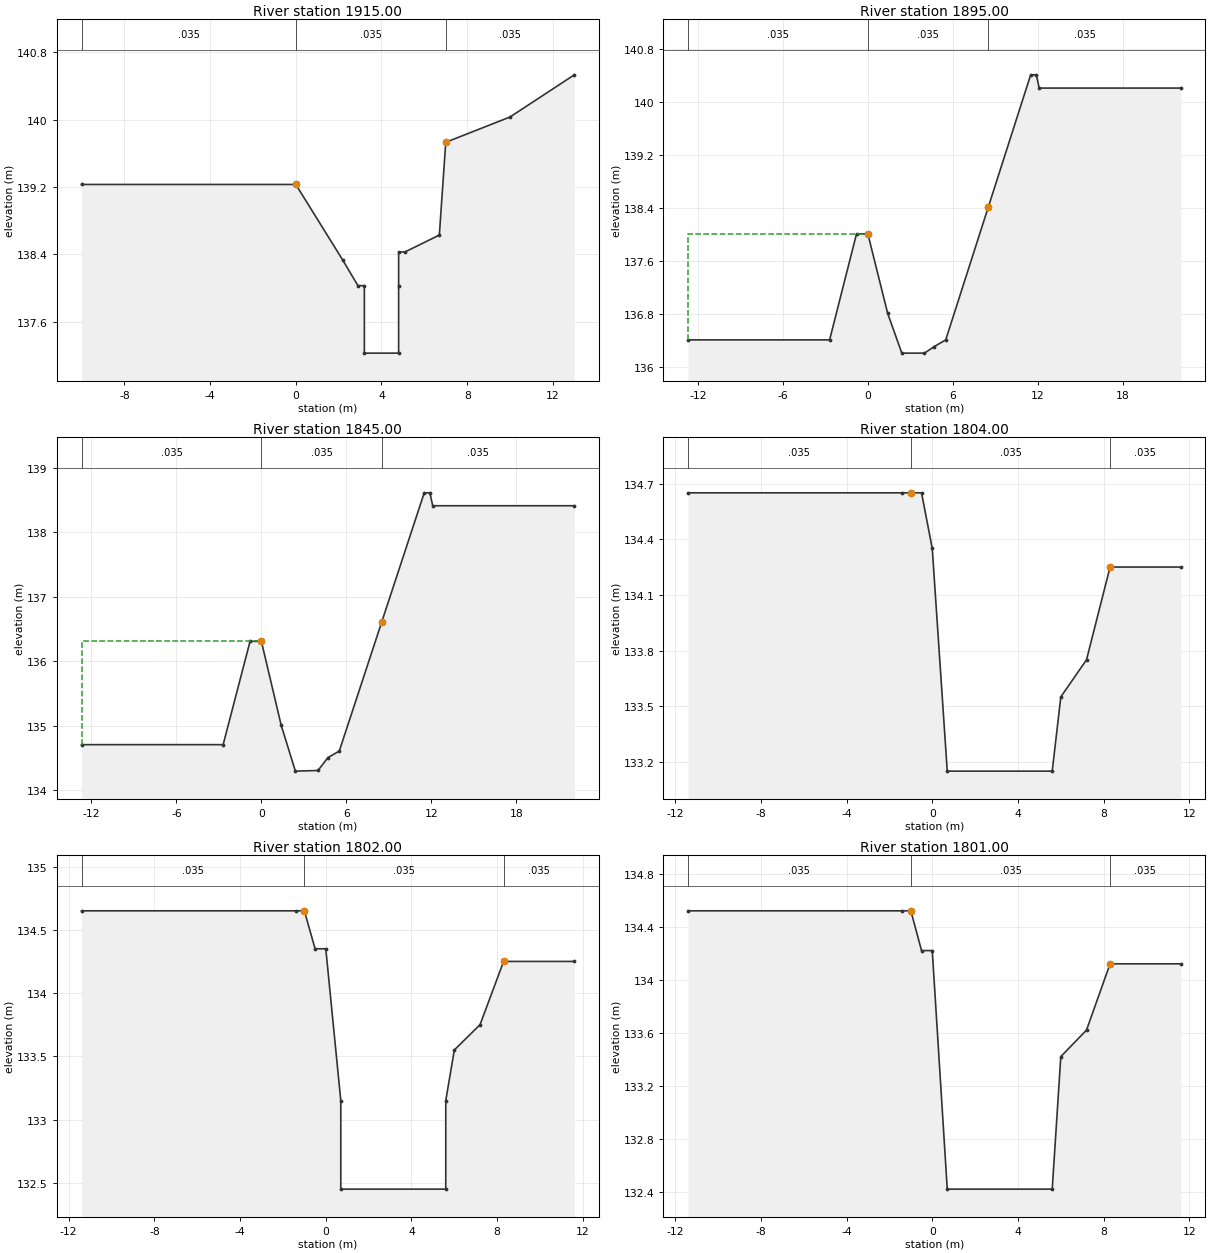
Type RM Length L Ch R = 1 ,1915.00 ,20,20,20
BEGIN DESCRIPTION:
37.02
END DESCRIPTION:
#Sta/Elev= 14
     -10  139.23       0  139.23     2.2  138.33     2.9  138.03     3.2  138.03
     3.2  137.23     4.8  137.23     4.8  138.03     4.8  138.43     5.1  138.43
     6.7  138.63       7  139.73      10  140.03      13  140.53
#Mann= 3 , 0 , 0
     -10    .035       0       0    .035       0       7    .035       0
#XS Ineff= 2 , 0
               0  139.23       7          139.73
Permanent Ineff=
       F       F
Bank Sta=0,7
XS Rating Curve= 0
Exp/Cntr=.3,.1

Type RM Length L Ch R = 1 ,1895.00 ,50,50,50
BEGIN DESCRIPTION:
37
END DESCRIPTION:
#Sta/Elev= 14
   -12.7  136.41    -2.7  136.41     -.8  138.01       0  138.01     1.4  136.81
     2.4  136.21       4  136.21     4.7  136.31     5.5  136.41     8.5  138.41
    11.5  140.41    11.9  140.41    12.1  140.21    22.1  140.21
#Mann= 3 , 0 , 0
   -12.7    .035       0       0    .035       0     8.5    .035       0
#XS Ineff= 2 , 0
               0  138.01     8.5          138.41
Permanent Ineff=
       F       F
Bank Sta=0,8.5
XS Rating Curve= 0
Exp/Cntr=.3,.1

Type RM Length L Ch R = 1 ,1845.00 ,41,41,41
BEGIN DESCRIPTION:
36
END DESCRIPTION:
#Sta/Elev= 14
   -12.7  134.71    -2.7  134.71     -.8  136.31       0  136.31     1.4  135.01
     2.4   134.3       4  134.31     4.7  134.51     5.5  134.61     8.5  136.61
    11.5  138.61    11.9  138.61    12.1  138.41    22.1  138.41
#Mann= 3 , 0 , 0
   -12.7    .035       0       0    .035       0     8.5    .035       0
#XS Ineff= 2 , 0
               0  136.31     8.5          136.61
Permanent Ineff=
       F       F
Bank Sta=0,8.5
XS Rating Curve= 0
Exp/Cntr=.3,.1

Type RM Length L Ch R = 1 ,1804.00 ,2,2,2
BEGIN DESCRIPTION:
35.01
END DESCRIPTION:
#Sta/Elev= 11
   -11.4  134.65    -1.4  134.65      -1  134.65     -.5  134.65       0  134.35
      .7  133.15     5.6  133.15       6  133.55     7.2  133.75     8.3  134.25
    11.6  134.25
#Mann= 3 , 0 , 0
   -11.4    .035       0      -1    .035       0     8.3    .035       0
#XS Ineff= 2 , 0
              -1  134.65     8.3          134.25
Permanent Ineff=
       F       F
Bank Sta=-1,8.3
XS Rating Curve= 0
Exp/Cntr=.3,.1

Type RM Length L Ch R = 1 ,1802.00 ,1,1,1
BEGIN DESCRIPTION:
35.009
END DESCRIPTION:
#Sta/Elev= 13
   -11.4  134.65    -1.4  134.65      -1  134.65     -.5  134.35       0  134.35
      .7  133.15      .7  132.45     5.6  132.45     5.6  133.15       6  133.55
     7.2  133.75     8.3  134.25    11.6  134.25
#Mann= 3 , 0 , 0
   -11.4    .035       0      -1    .035       0     8.3    .035       0
#XS Ineff= 2 , 0
              -1  134.65     8.3          134.25
Permanent Ineff=
       F       F
Bank Sta=-1,8.3
XS Rating Curve= 0
Exp/Cntr=.3,.1

Type RM Length L Ch R = 1 ,1801.00 ,1,1,1
BEGIN DESCRIPTION:
35.008
END DESCRIPTION:
#Sta/Elev= 11
   -11.4  134.52    -1.4  134.52      -1  134.52     -.5  134.22       0  134.22
      .7  132.42     5.6  132.42       6  133.42     7.2  133.62     8.3  134.12
    11.6  134.12
#Mann= 3 , 0 , 0
   -11.4    .035       0      -1    .035       0     8.3    .035       0
#XS Ineff= 2 , 0
              -1  134.52     8.3          134.12
Permanent Ineff=
       F       F
Bank Sta=-1,8.3
XS Rating Curve= 0
Exp/Cntr=.3,.1

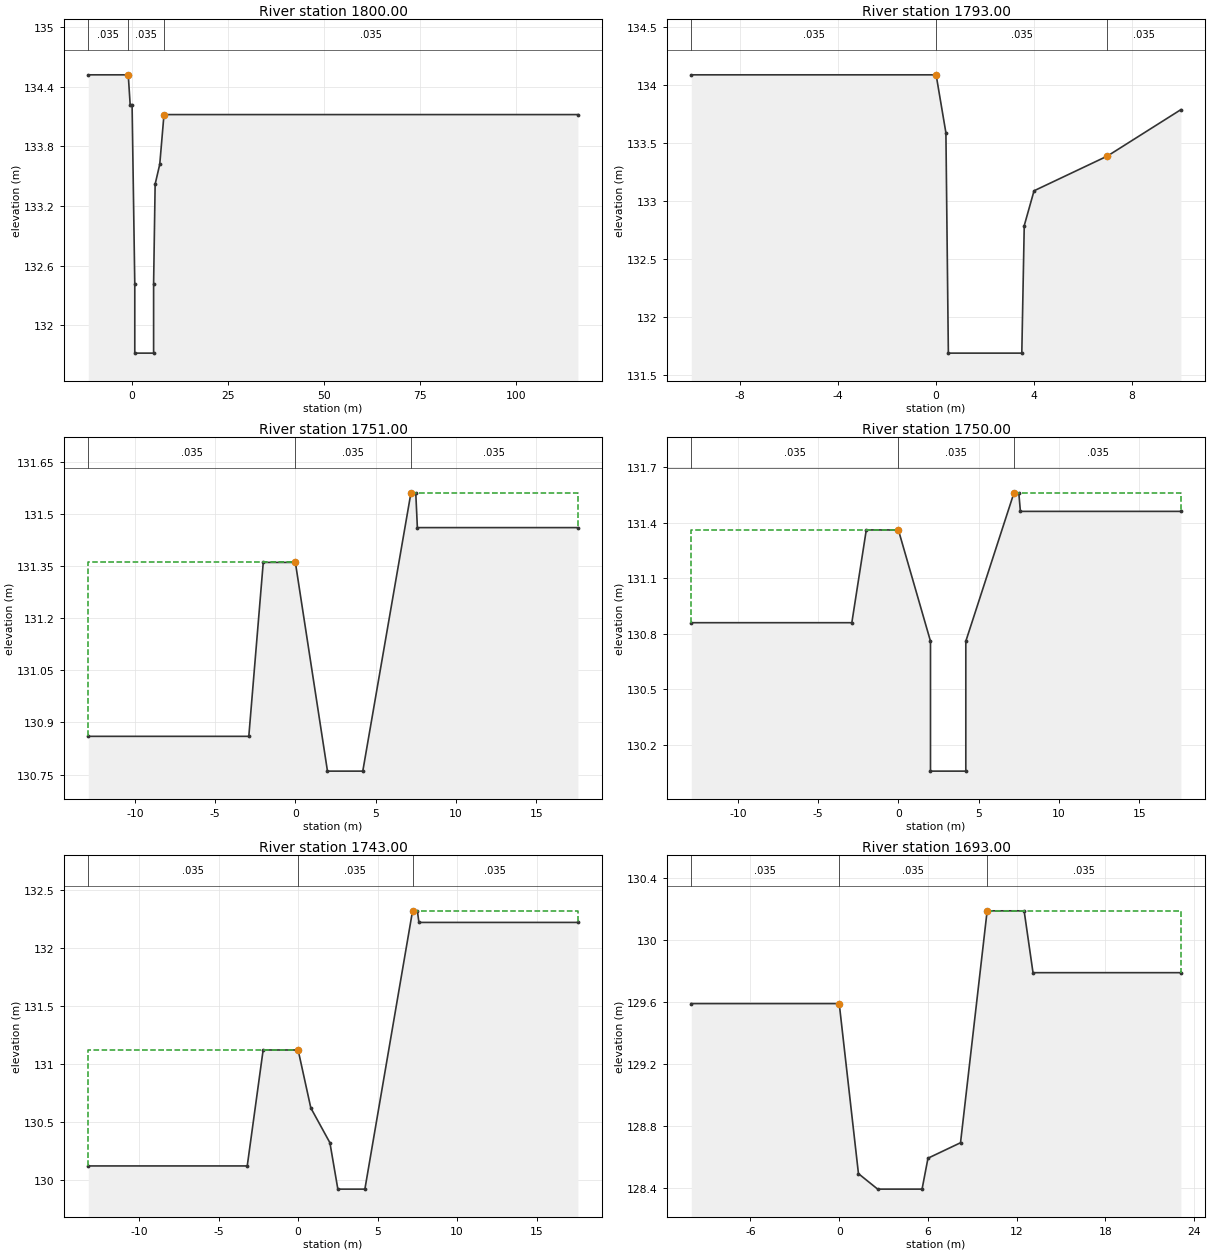
Type RM Length L Ch R = 1 ,1800.00 ,7,7,7
BEGIN DESCRIPTION:
35.007
END DESCRIPTION:
#Sta/Elev= 13
   -11.4  134.52    -1.4  134.52      -1  134.52     -.5  134.22       0  134.22
      .7  132.42      .7  131.72     5.6  131.72     5.6  132.42       6  133.42
     7.2  133.62     8.3  134.12     116  134.12
#Mann= 3 , 0 , 0
   -11.4    .035       0      -1    .035       0     8.3    .035       0
#XS Ineff= 2 , 0
              -1  134.52     8.3          134.12
Permanent Ineff=
       F       F
Bank Sta=-1,8.3
XS Rating Curve= 0
Exp/Cntr=.3,.1

Type RM Length L Ch R = 1 ,1793.00 ,42,42,42
BEGIN DESCRIPTION:
35
END DESCRIPTION:
#Sta/Elev= 9
     -10  134.09       0  134.09      .4  133.59      .5  131.69     3.5  131.69
     3.6  132.79       4  133.09       7  133.39      10  133.79
#Mann= 3 , 0 , 0
     -10    .035       0       0    .035       0       7    .035       0
#XS Ineff= 2 , 0
               0  134.09       7          133.39
Permanent Ineff=
       F       F
Bank Sta=0,7
XS Rating Curve= 0
Exp/Cntr=.3,.1

Type RM Length L Ch R = 1 ,1751.00 ,1,1,1
BEGIN DESCRIPTION:
34.008
END DESCRIPTION:
#Sta/Elev= 10
   -12.9  130.86    -2.9  130.86      -2  131.36       0  131.36       2  130.76
     4.2  130.76     7.2  131.56     7.5  131.56     7.6  131.46    17.6  131.46
#Mann= 3 , 0 , 0
   -12.9    .035       0       0    .035       0     7.2    .035       0
#XS Ineff= 2 , 0
               0  131.36     7.2          131.56
Permanent Ineff=
       F       F
Bank Sta=0,7.2
XS Rating Curve= 0
Exp/Cntr=.3,.1

Type RM Length L Ch R = 1 ,1750.00 ,7,7,7
BEGIN DESCRIPTION:
34.007
END DESCRIPTION:
#Sta/Elev= 12
   -12.9  130.86    -2.9  130.86      -2  131.36       0  131.36       2  130.76
       2  130.06     4.2  130.06     4.2  130.76     7.2  131.56     7.5  131.56
     7.6  131.46    17.6  131.46
#Mann= 3 , 0 , 0
   -12.9    .035       0       0    .035       0     7.2    .035       0
#XS Ineff= 2 , 0
               0  131.36     7.2          131.56
Permanent Ineff=
       F       F
Bank Sta=0,7.2
XS Rating Curve= 0
Exp/Cntr=.3,.1

Type RM Length L Ch R = 1 ,1743.00 ,50,50,50
BEGIN DESCRIPTION:
34
END DESCRIPTION:
#Sta/Elev= 12
   -13.2  130.12    -3.2  130.12    -2.2  131.12       0  131.12      .8  130.62
       2  130.32     2.5  129.92     4.2  129.92     7.2  132.32     7.5  132.32
     7.6  132.22    17.6  132.22
#Mann= 3 , 0 , 0
   -13.2    .035       0       0    .035       0     7.2    .035       0
#XS Ineff= 2 , 0
               0  131.12     7.2          132.32
Permanent Ineff=
       F       F
Bank Sta=0,7.2
XS Rating Curve= 0
Exp/Cntr=.3,.1

Type RM Length L Ch R = 1 ,1693.00 ,5,5,5
BEGIN DESCRIPTION:
33
END DESCRIPTION:
#Sta/Elev= 11
     -10  129.59       0  129.59     1.3  128.49     2.6  128.39     5.6  128.39
       6  128.59     8.2  128.69      10  130.19    12.5  130.19    13.1  129.79
    23.1  129.79
#Mann= 3 , 0 , 0
     -10    .035       0       0    .035       0      10    .035       0
#XS Ineff= 2 , 0
               0  129.59      10          130.19
Permanent Ineff=
       F       F
Bank Sta=0,10
XS Rating Curve= 0
Exp/Cntr=.3,.1

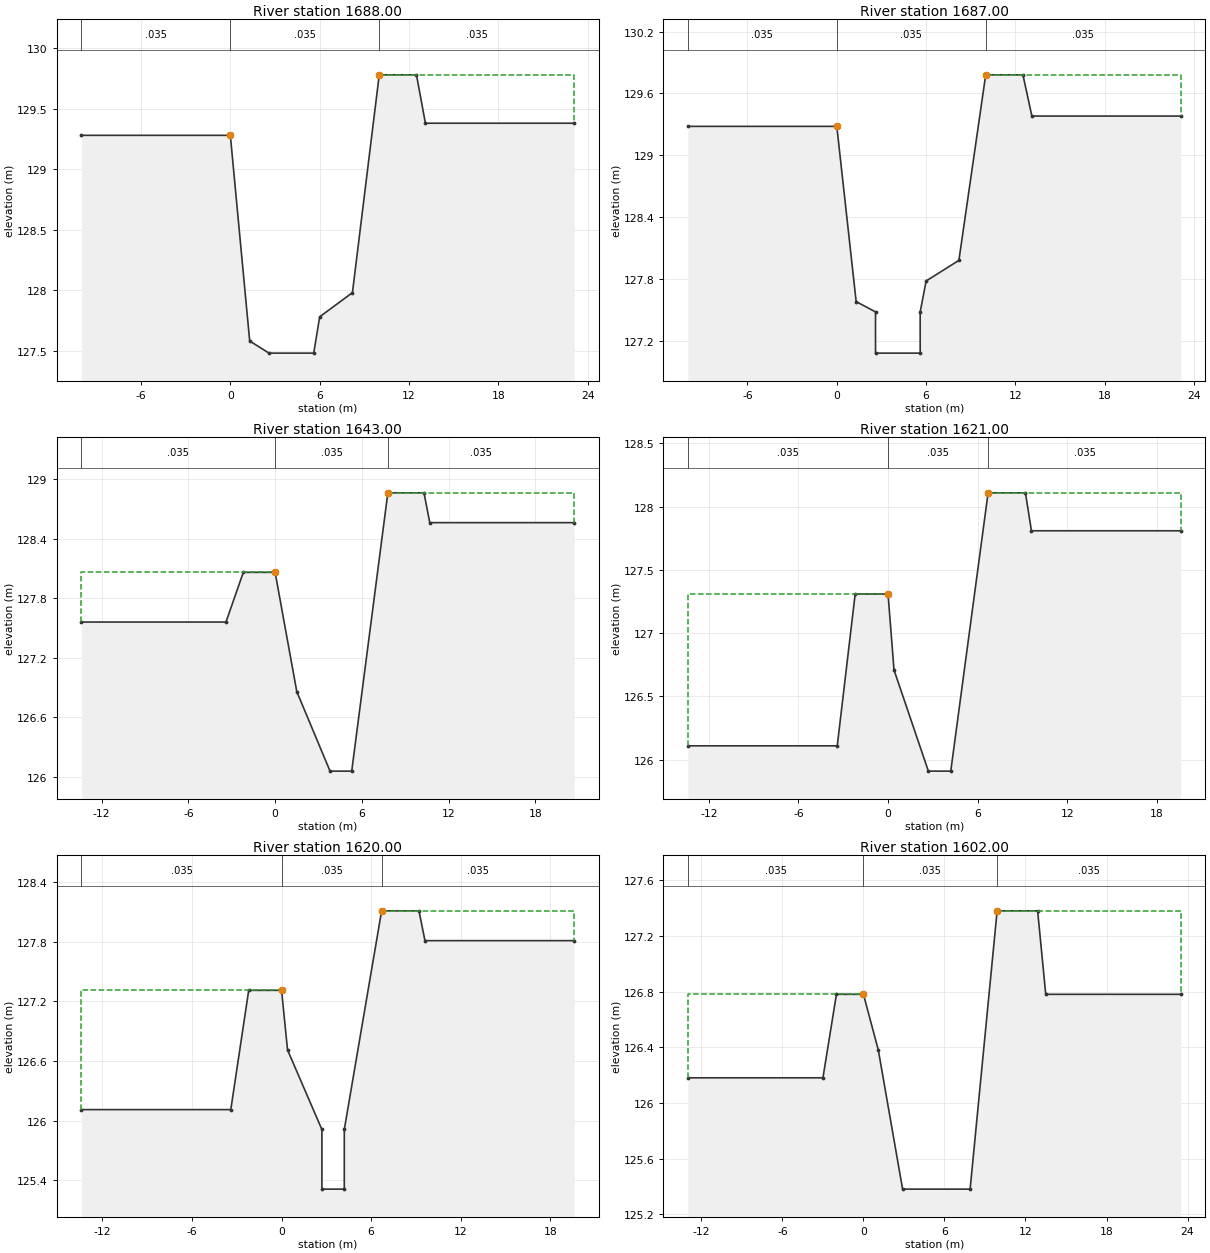
Type RM Length L Ch R = 1 ,1688.00 ,1,1,1
BEGIN DESCRIPTION:
32.045
END DESCRIPTION:
#Sta/Elev= 11
     -10  129.28       0  129.28     1.3  127.58     2.6  127.48     5.6  127.48
       6  127.78     8.2  127.98      10  129.78    12.5  129.78    13.1  129.38
    23.1  129.38
#Mann= 3 , 0 , 0
     -10    .035       0       0    .035       0      10    .035       0
#XS Ineff= 2 , 0
               0  129.28      10          129.78
Permanent Ineff=
       F       F
Bank Sta=0,10
XS Rating Curve= 0
Exp/Cntr=.3,.1

Type RM Length L Ch R = 1 ,1687.00 ,44,44,44
BEGIN DESCRIPTION:
32.044
END DESCRIPTION:
#Sta/Elev= 13
     -10  129.28       0  129.28     1.3  127.58     2.6  127.48     2.6  127.08
     5.6  127.08     5.6  127.48       6  127.78     8.2  127.98      10  129.78
    12.5  129.78    13.1  129.38    23.1  129.38
#Mann= 3 , 0 , 0
     -10    .035       0       0    .035       0      10    .035       0
#XS Ineff= 2 , 0
               0  129.28      10          129.78
Permanent Ineff=
       F       F
Bank Sta=0,10
XS Rating Curve= 0
Exp/Cntr=.3,.1

Type RM Length L Ch R = 1 ,1643.00 ,22,22,22
BEGIN DESCRIPTION:
32
END DESCRIPTION:
#Sta/Elev= 11
   -13.4  127.56    -3.4  127.56    -2.2  128.06       0  128.06     1.5  126.86
     3.8  126.06     5.3  126.06     7.8  128.86    10.3  128.86    10.7  128.56
    20.7  128.56
#Mann= 3 , 0 , 0
   -13.4    .035       0       0    .035       0     7.8    .035       0
#XS Ineff= 2 , 0
               0  128.06     7.8          128.86
Permanent Ineff=
       F       F
Bank Sta=0,7.8
XS Rating Curve= 0
Exp/Cntr=.3,.1

Type RM Length L Ch R = 1 ,1621.00 ,1,1,1
BEGIN DESCRIPTION:
31.028
END DESCRIPTION:
#Sta/Elev= 11
   -13.4  126.11    -3.4  126.11    -2.2  127.31       0  127.31      .4  126.71
     2.7  125.91     4.2  125.91     6.7  128.11     9.2  128.11     9.6  127.81
    19.6  127.81
#Mann= 3 , 0 , 0
   -13.4    .035       0       0    .035       0     6.7    .035       0
#XS Ineff= 2 , 0
               0  127.31     6.7          128.11
Permanent Ineff=
       F       F
Bank Sta=0,6.7
XS Rating Curve= 0
Exp/Cntr=.3,.1

Type RM Length L Ch R = 1 ,1620.00 ,18,18,18
BEGIN DESCRIPTION:
31.027
END DESCRIPTION:
#Sta/Elev= 13
   -13.4  126.11    -3.4  126.11    -2.2  127.31       0  127.31      .4  126.71
     2.7  125.91     2.7  125.31     4.2  125.31     4.2  125.91     6.7  128.11
     9.2  128.11     9.6  127.81    19.6  127.81
#Mann= 3 , 0 , 0
   -13.4    .035       0       0    .035       0     6.7    .035       0
#XS Ineff= 2 , 0
               0  127.31     6.7          128.11
Permanent Ineff=
       F       F
Bank Sta=0,6.7
XS Rating Curve= 0
Exp/Cntr=.3,.1

Type RM Length L Ch R = 1 ,1602.00 ,9,9,9
BEGIN DESCRIPTION:
31.009
END DESCRIPTION:
#Sta/Elev= 11
     -13  126.18      -3  126.18      -2  126.78       0  126.78     1.1  126.38
     2.9  125.38     7.9  125.38     9.9  127.38    12.9  127.38    13.5  126.78
    23.5  126.78
#Mann= 3 , 0 , 0
     -13    .035       0       0    .035       0     9.9    .035       0
#XS Ineff= 2 , 0
               0  126.78     9.9          127.38
Permanent Ineff=
       F       F
Bank Sta=0,9.9
XS Rating Curve= 0
Exp/Cntr=.3,.1

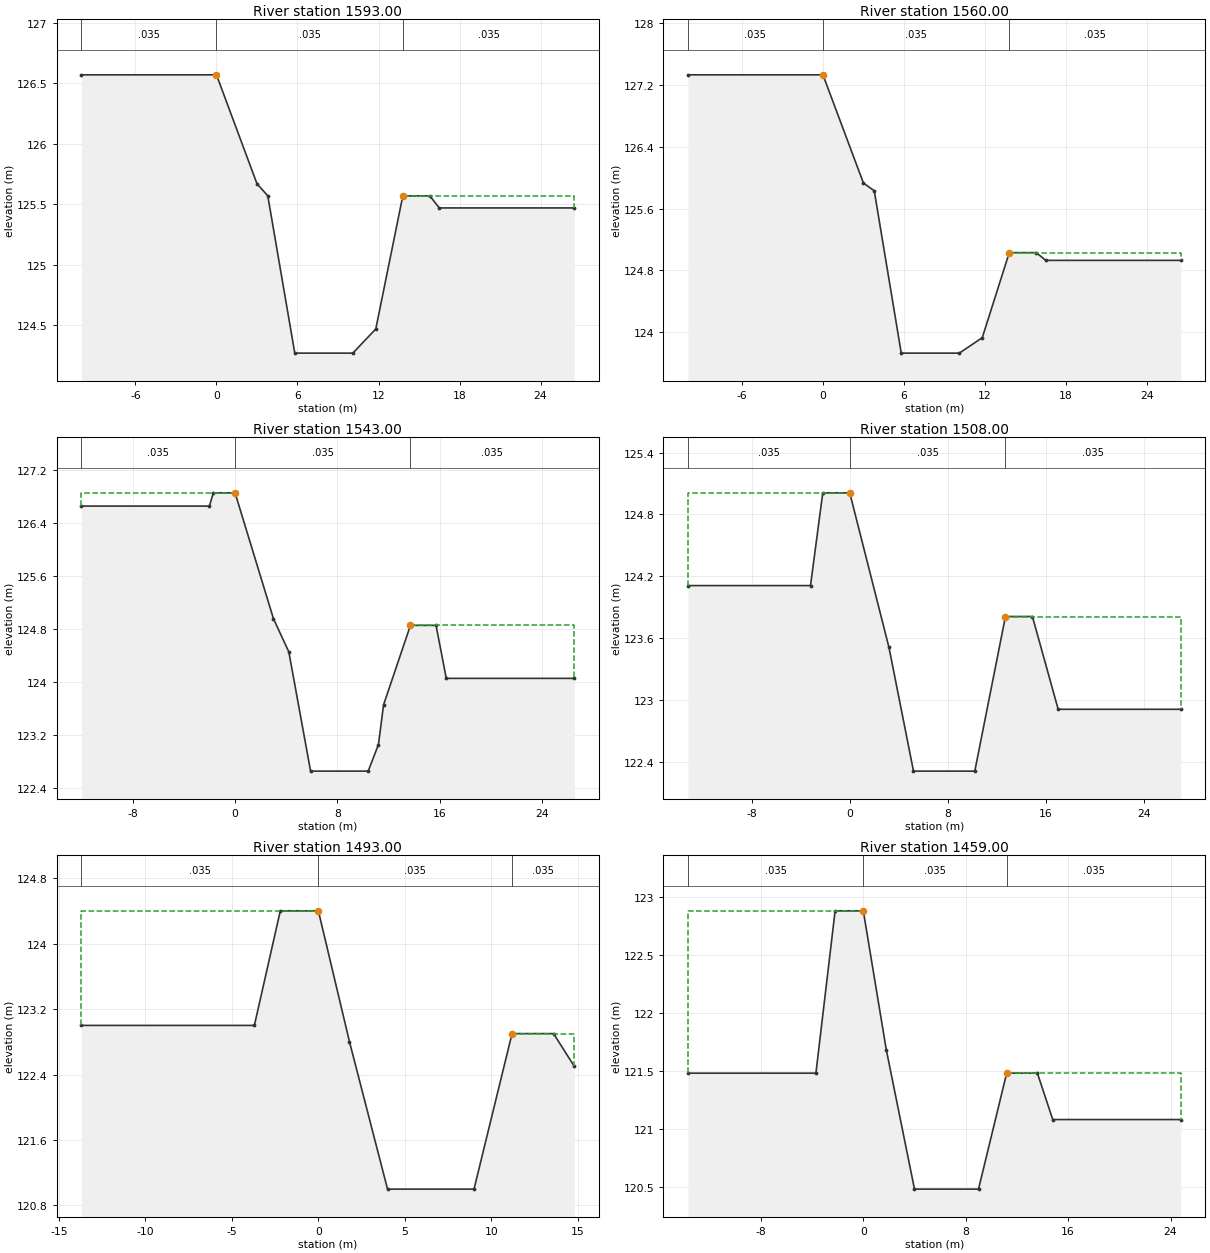
Type RM Length L Ch R = 1 ,1593.00 ,33,33,33
BEGIN DESCRIPTION:
31
END DESCRIPTION:
#Sta/Elev= 11
     -10  126.57       0  126.57       3  125.67     3.8  125.57     5.8  124.27
    10.1  124.27    11.8  124.47    13.8  125.57    15.8  125.57    16.5  125.47
    26.5  125.47
#Mann= 3 , 0 , 0
     -10    .035       0       0    .035       0    13.8    .035       0
#XS Ineff= 2 , 0
               0  126.57    13.8          125.57
Permanent Ineff=
       F       F
Bank Sta=0,13.8
XS Rating Curve= 0
Exp/Cntr=.3,.1

Type RM Length L Ch R = 1 ,1560.00 ,17,17,17
BEGIN DESCRIPTION:
30.017
END DESCRIPTION:
#Sta/Elev= 11
     -10  127.33       0  127.33       3  125.93     3.8  125.83     5.8  123.73
    10.1  123.73    11.8  123.93    13.8  125.03    15.8  125.03    16.5  124.93
    26.5  124.93
#Mann= 3 , 0 , 0
     -10    .035       0       0    .035       0    13.8    .035       0
#XS Ineff= 2 , 0
               0  127.33    13.8          125.03
Permanent Ineff=
       F       F
Bank Sta=0,13.8
XS Rating Curve= 0
Exp/Cntr=.3,.1

Type RM Length L Ch R = 1 ,1543.00 ,35,35,35
BEGIN DESCRIPTION:
30
END DESCRIPTION:
#Sta/Elev= 14
     -12  126.66      -2  126.66    -1.7  126.86       0  126.86       3  124.96
     4.2  124.46     5.9  122.66    10.4  122.66    11.2  123.06    11.6  123.66
    13.7  124.86    15.7  124.86    16.5  124.06    26.5  124.06
#Mann= 3 , 0 , 0
     -12    .035       0       0    .035       0    13.7    .035       0
#XS Ineff= 2 , 0
               0  126.86    13.7          124.86
Permanent Ineff=
       F       F
Bank Sta=0,13.7
XS Rating Curve= 0
Exp/Cntr=.3,.1

Type RM Length L Ch R = 1 ,1508.00 ,15,15,15
BEGIN DESCRIPTION:
29.015
END DESCRIPTION:
#Sta/Elev= 11
   -13.2  124.11    -3.2  124.11    -2.2  125.01       0  125.01     3.2  123.51
     5.2  122.31    10.2  122.31    12.7  123.81    14.9  123.81      17  122.91
      27  122.91
#Mann= 3 , 0 , 0
   -13.2    .035       0       0    .035       0    12.7    .035       0
#XS Ineff= 2 , 0
               0  125.01    12.7          123.81
Permanent Ineff=
       F       F
Bank Sta=0,12.7
XS Rating Curve= 0
Exp/Cntr=.3,.1

Type RM Length L Ch R = 1 ,1493.00 ,34,34,34
BEGIN DESCRIPTION:
29
END DESCRIPTION:
#Sta/Elev= 10
   -13.7     123    -3.7     123    -2.2   124.4       0   124.4     1.8   122.8
       4     121       9     121    11.2   122.9    13.6   122.9    14.8   122.5
#Mann= 3 , 0 , 0
   -13.7    .035       0       0    .035       0    11.2    .035       0
#XS Ineff= 2 , 0
               0   124.4    11.2           122.9
Permanent Ineff=
       F       F
Bank Sta=0,11.2
XS Rating Curve= 0
Exp/Cntr=.3,.1

Type RM Length L Ch R = 1 ,1459.00 ,1,1,1
BEGIN DESCRIPTION:
28.016
END DESCRIPTION:
#Sta/Elev= 11
   -13.7  121.48    -3.7  121.48    -2.2  122.88       0  122.88     1.8  121.68
       4  120.48       9  120.48    11.2  121.48    13.6  121.48    14.8  121.08
    24.8  121.08
#Mann= 3 , 0 , 0
   -13.7    .035       0       0    .035       0    11.2    .035       0
#XS Ineff= 2 , 0
               0  122.88    11.2          121.48
Permanent Ineff=
       F       F
Bank Sta=0,11.2
XS Rating Curve= 0
Exp/Cntr=.3,.1

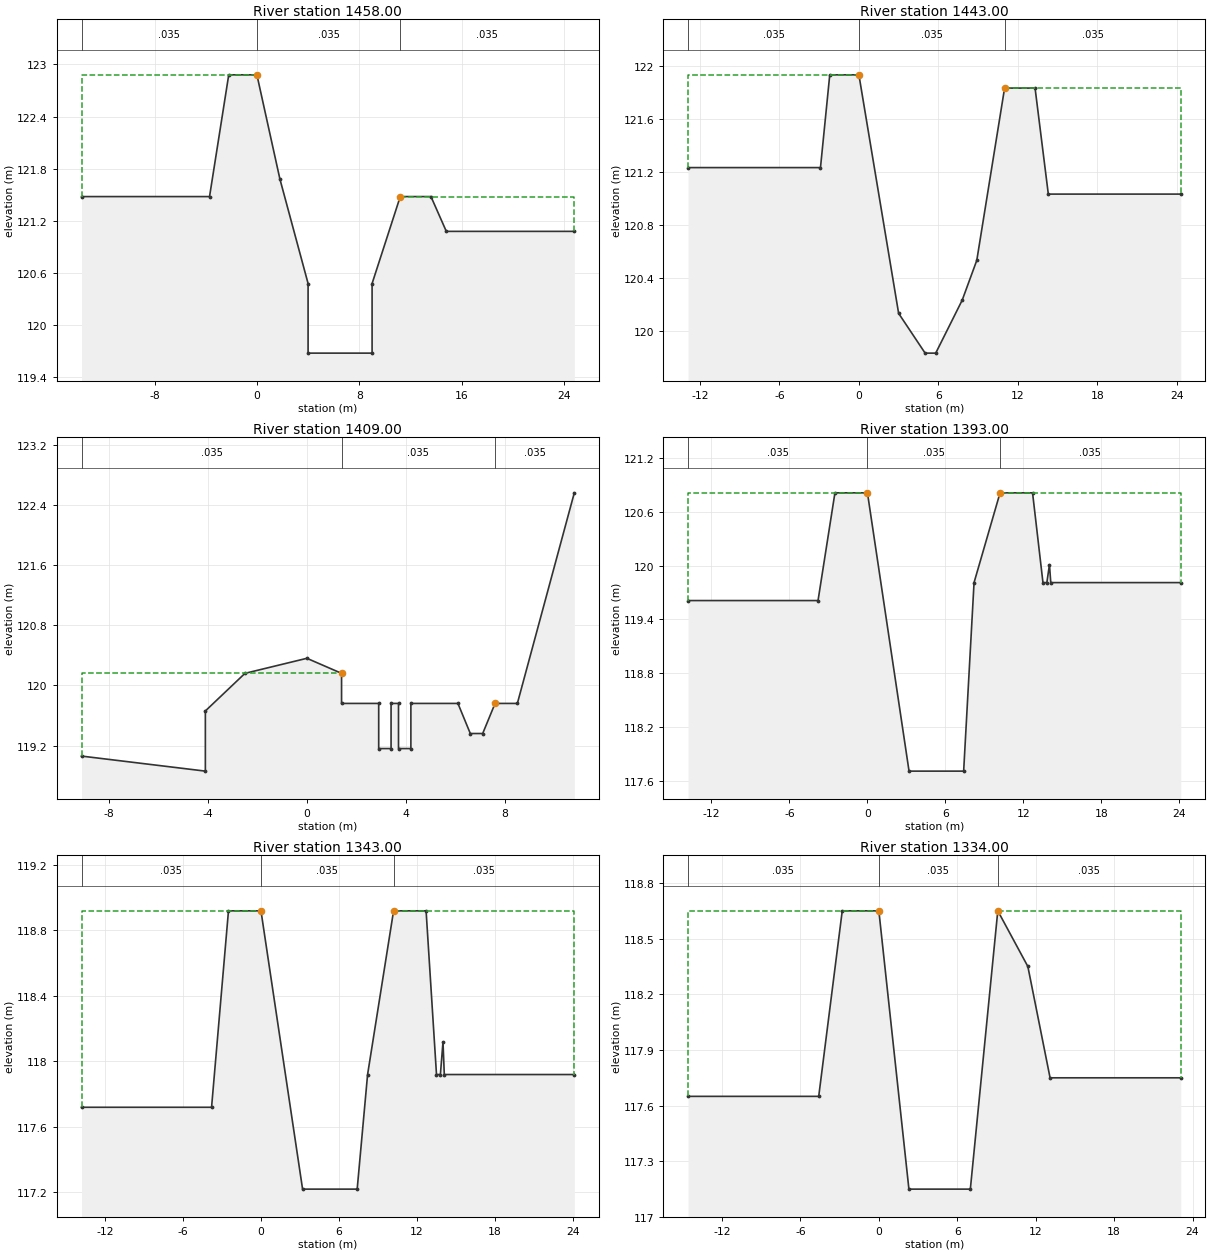
Type RM Length L Ch R = 1 ,1458.00 ,15,15,15
BEGIN DESCRIPTION:
28.015
END DESCRIPTION:
#Sta/Elev= 13
   -13.7  121.48    -3.7  121.48    -2.2  122.88       0  122.88     1.8  121.68
       4  120.48       4  119.68       9  119.68       9  120.48    11.2  121.48
    13.6  121.48    14.8  121.08    24.8  121.08
#Mann= 3 , 0 , 0
   -13.7    .035       0       0    .035       0    11.2    .035       0
#XS Ineff= 2 , 0
               0  122.88    11.2          121.48
Permanent Ineff=
       F       F
Bank Sta=0,11.2
XS Rating Curve= 0
Exp/Cntr=.3,.1

Type RM Length L Ch R = 1 ,1443.00 ,34,34,34
BEGIN DESCRIPTION:
28
END DESCRIPTION:
#Sta/Elev= 13
   -12.9  121.23    -2.9  121.23    -2.2  121.93       0  121.93       3  120.13
       5  119.83     5.8  119.83     7.8  120.23     8.9  120.53      11  121.83
    13.3  121.83    14.3  121.03    24.3  121.03
#Mann= 3 , 0 , 0
   -12.9    .035       0       0    .035       0      11    .035       0
#XS Ineff= 2 , 0
               0  121.93      11          121.83
Permanent Ineff=
       F       F
Bank Sta=0,11
XS Rating Curve= 0
Exp/Cntr=.3,.1

Type RM Length L Ch R = 1 ,1409.00 ,16,16,16
BEGIN DESCRIPTION:
27.016
END DESCRIPTION:
#Sta/Elev= 21
    -9.1  119.06    -4.1  118.86    -4.1  119.66    -2.5  120.16       0  120.36
     1.4  120.16     1.4  119.76     2.9  119.76     2.9  119.16     3.4  119.16
     3.4  119.76     3.7  119.76     3.7  119.16     4.2  119.16     4.2  119.76
     6.1  119.76     6.6  119.36     7.1  119.36     7.6  119.76     8.5  119.76
    10.8  122.56
#Mann= 3 , 0 , 0
    -9.1    .035       0     1.4    .035       0     7.6    .035       0
#XS Ineff= 2 , 0
             1.4  120.16     7.6          119.76
Permanent Ineff=
       F       F
Bank Sta=1.4,7.6
XS Rating Curve= 0
Exp/Cntr=.3,.1

Type RM Length L Ch R = 1 ,1393.00 ,50,50,50
BEGIN DESCRIPTION:
27
END DESCRIPTION:
#Sta/Elev= 14
   -13.8  119.61    -3.8  119.61    -2.5  120.81       0  120.81     3.2  117.71
     7.4  117.71     8.2  119.81    10.2  120.81    12.7  120.81    13.5  119.81
    13.8  119.81      14  120.01    14.1  119.81    24.1  119.81
#Mann= 3 , 0 , 0
   -13.8    .035       0       0    .035       0    10.2    .035       0
#XS Ineff= 2 , 0
               0  120.81    10.2          120.81
Permanent Ineff=
       F       F
Bank Sta=0,10.2
XS Rating Curve= 0
Exp/Cntr=.3,.1

Type RM Length L Ch R = 1 ,1343.00 ,9,9,9
BEGIN DESCRIPTION:
26
END DESCRIPTION:
#Sta/Elev= 14
   -13.8  117.72    -3.8  117.72    -2.5  118.92       0  118.92     3.2  117.22
     7.4  117.22     8.2  117.92    10.2  118.92    12.7  118.92    13.5  117.92
    13.8  117.92      14  118.12    14.1  117.92    24.1  117.92
#Mann= 3 , 0 , 0
   -13.8    .035       0       0    .035       0    10.2    .035       0
#XS Ineff= 2 , 0
               0  118.92    10.2          118.92
Permanent Ineff=
       F       F
Bank Sta=0,10.2
XS Rating Curve= 0
Exp/Cntr=.3,.1

Type RM Length L Ch R = 1 ,1334.00 ,1,1,1
BEGIN DESCRIPTION:
25.041
END DESCRIPTION:
#Sta/Elev= 10
   -14.6  117.65    -4.6  117.65    -2.8  118.65       0  118.65     2.3  117.15
       7  117.15     9.1  118.65    11.4  118.35    13.1  117.75    23.1  117.75
#Mann= 3 , 0 , 0
   -14.6    .035       0       0    .035       0     9.1    .035       0
#XS Ineff= 2 , 0
               0  118.65     9.1          118.65
Permanent Ineff=
       F       F
Bank Sta=0,9.1
XS Rating Curve= 0
Exp/Cntr=.3,.1

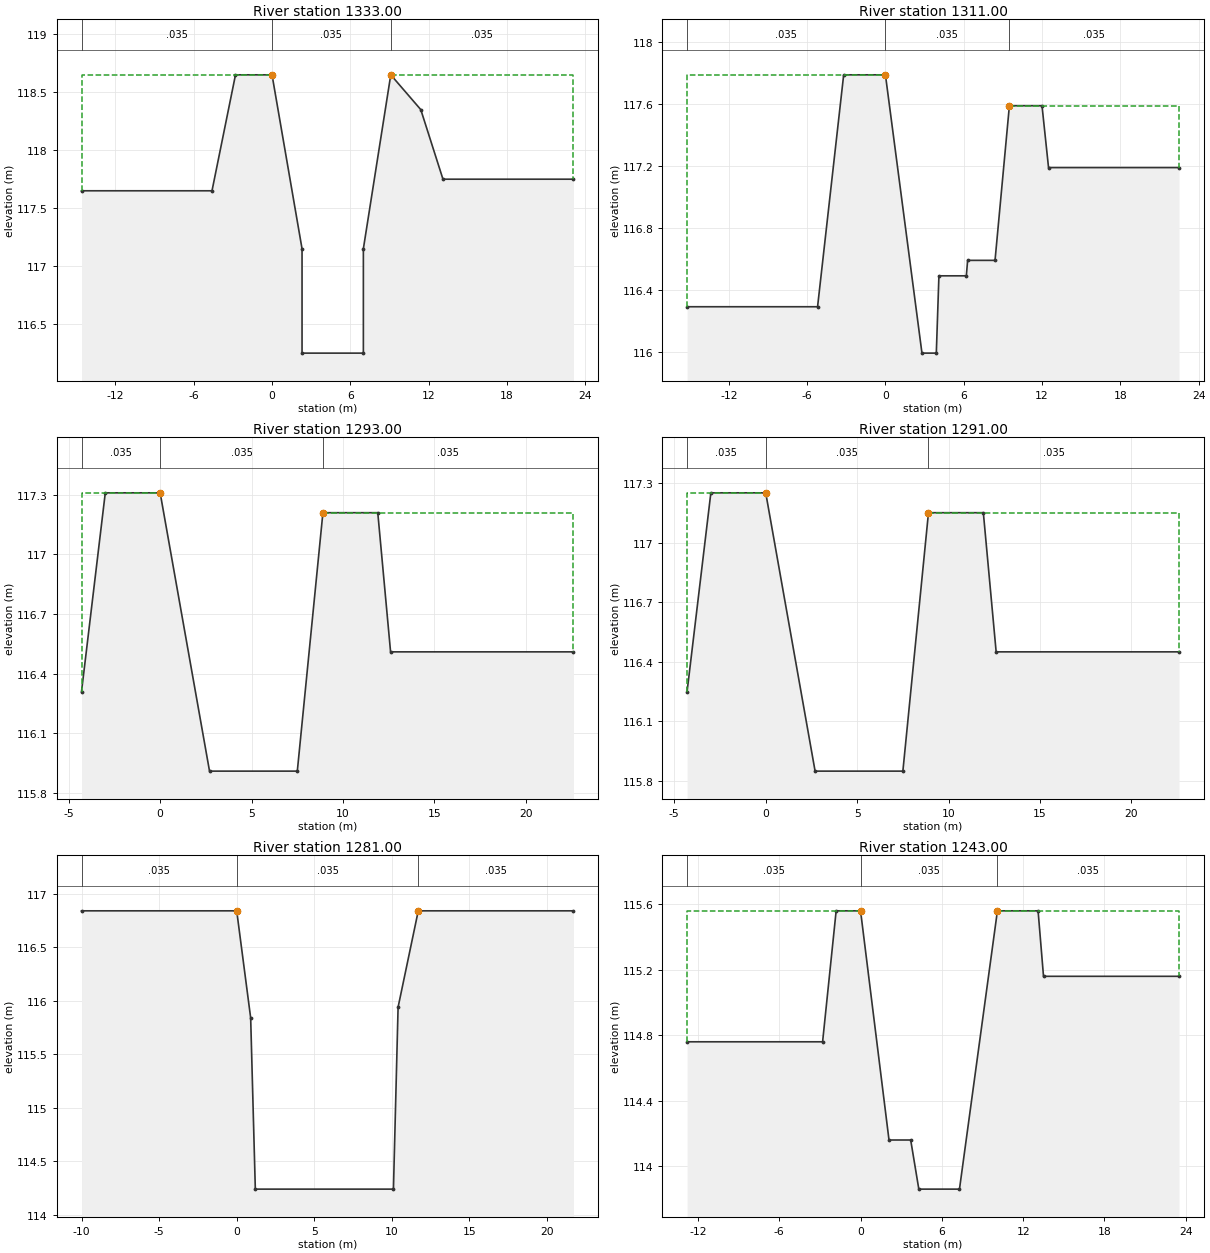
Type RM Length L Ch R = 1 ,1333.00 ,22,22,22
BEGIN DESCRIPTION:
25.04
END DESCRIPTION:
#Sta/Elev= 12
   -14.6  117.65    -4.6  117.65    -2.8  118.65       0  118.65     2.3  117.15
     2.3  116.25       7  116.25       7  117.15     9.1  118.65    11.4  118.35
    13.1  117.75    23.1  117.75
#Mann= 3 , 0 , 0
   -14.6    .035       0       0    .035       0     9.1    .035       0
#XS Ineff= 2 , 0
               0  118.65     9.1          118.65
Permanent Ineff=
       F       F
Bank Sta=0,9.1
XS Rating Curve= 0
Exp/Cntr=.3,.1

Type RM Length L Ch R = 1 ,1311.00 ,18,18,18
BEGIN DESCRIPTION:
25.018
END DESCRIPTION:
#Sta/Elev= 14
   -15.2  116.29    -5.2  116.29    -3.2  117.79       0  117.79     2.8  115.99
     3.9  115.99     4.1  116.49     6.2  116.49     6.3  116.59     8.4  116.59
     9.5  117.59      12  117.59    12.5  117.19    22.5  117.19
#Mann= 3 , 0 , 0
   -15.2    .035       0       0    .035       0     9.5    .035       0
#XS Ineff= 2 , 0
               0  117.79     9.5          117.59
Permanent Ineff=
       F       F
Bank Sta=0,9.5
XS Rating Curve= 0
Exp/Cntr=.3,.1

Type RM Length L Ch R = 1 ,1293.00 ,2,2,2
BEGIN DESCRIPTION:
25
END DESCRIPTION:
#Sta/Elev= 9
    -4.3  116.31      -3  117.31       0  117.31     2.7  115.91     7.5  115.91
     8.9  117.21    11.9  117.21    12.6  116.51    22.6  116.51
#Mann= 3 , 0 , 0
    -4.3    .035       0       0    .035       0     8.9    .035       0
#XS Ineff= 2 , 0
               0  117.31     8.9          117.21
Permanent Ineff=
       F       F
Bank Sta=0,8.9
XS Rating Curve= 0
Exp/Cntr=.3,.1

Type RM Length L Ch R = 1 ,1291.00 ,10,10,10
BEGIN DESCRIPTION:
24.048
END DESCRIPTION:
#Sta/Elev= 9
    -4.3  116.25      -3  117.25       0  117.25     2.7  115.85     7.5  115.85
     8.9  117.15    11.9  117.15    12.6  116.45    22.6  116.45
#Mann= 3 , 0 , 0
    -4.3    .035       0       0    .035       0     8.9    .035       0
#XS Ineff= 2 , 0
               0  117.25     8.9          117.15
Permanent Ineff=
       F       F
Bank Sta=0,8.9
XS Rating Curve= 0
Exp/Cntr=.3,.1

Type RM Length L Ch R = 1 ,1281.00 ,38,38,38
BEGIN DESCRIPTION:
24.038
END DESCRIPTION:
#Sta/Elev= 8
     -10  116.84       0  116.84      .9  115.84     1.2  114.24    10.1  114.24
    10.4  115.94    11.7  116.84    21.7  116.84
#Mann= 3 , 0 , 0
     -10    .035       0       0    .035       0    11.7    .035       0
#XS Ineff= 2 , 0
               0  116.84    11.7          116.84
Permanent Ineff=
       F       F
Bank Sta=0,11.7
XS Rating Curve= 0
Exp/Cntr=.3,.1

Type RM Length L Ch R = 1 ,1243.00 ,12,12,12
BEGIN DESCRIPTION:
24
END DESCRIPTION:
#Sta/Elev= 12
   -12.8  114.76    -2.8  114.76    -1.8  115.56       0  115.56     2.1  114.16
     3.7  114.16     4.3  113.86     7.3  113.86    10.1  115.56    13.1  115.56
    13.5  115.16    23.5  115.16
#Mann= 3 , 0 , 0
   -12.8    .035       0       0    .035       0    10.1    .035       0
#XS Ineff= 2 , 0
               0  115.56    10.1          115.56
Permanent Ineff=
       F       F
Bank Sta=0,10.1
XS Rating Curve= 0
Exp/Cntr=.3,.1