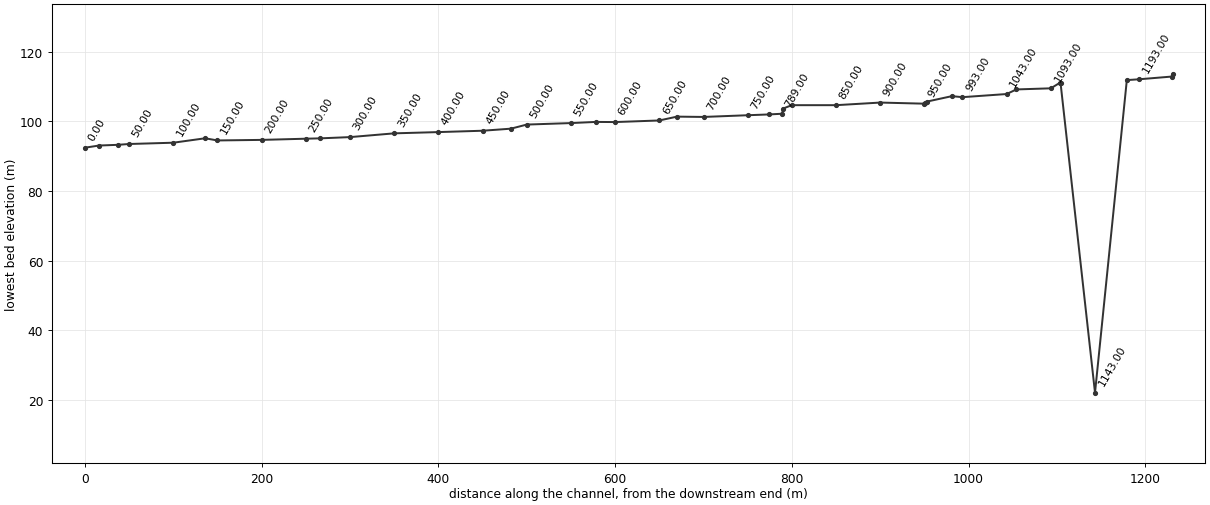
HEC-RAS study MSC.prj: MSC

--- MSC.g01 (geometry) --- (continued)

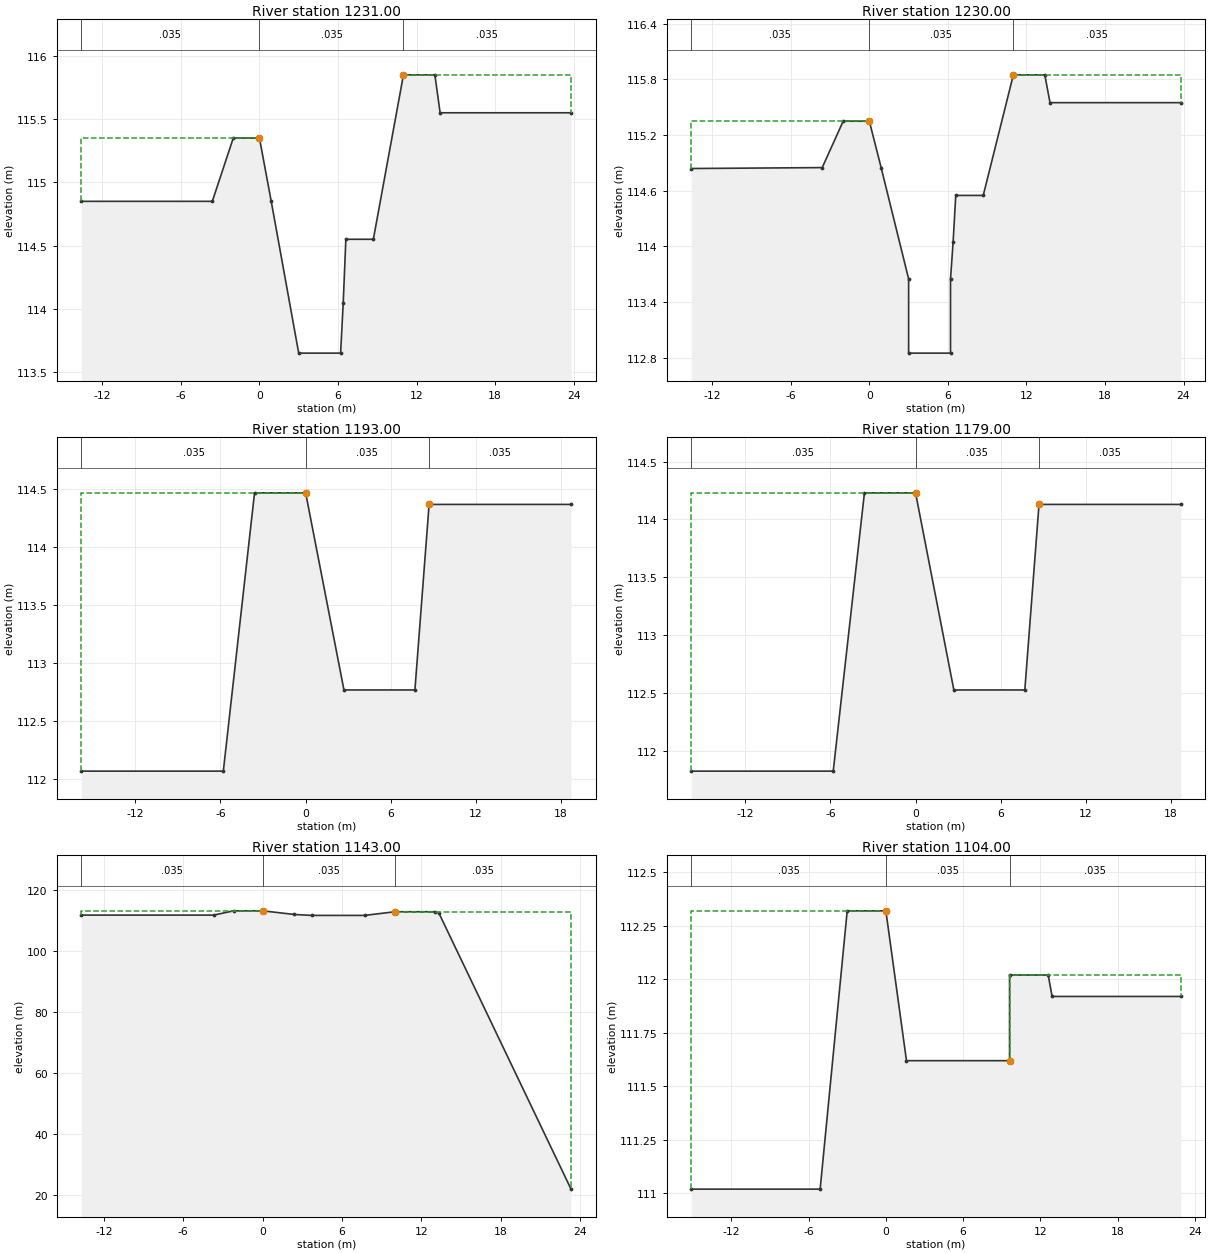
Type RM Length L Ch R = 1 ,1231.00 ,1,1,1
BEGIN DESCRIPTION:
23.038
END DESCRIPTION:
#Sta/Elev= 14
   -13.6  114.85    -3.6  114.85      -2  115.35       0  115.35      .9  114.85
       3  113.65     6.2  113.65     6.4  114.05     6.6  114.55     8.7  114.55
      11  115.85    13.4  115.85    13.8  115.55    23.8  115.55
#Mann= 3 , 0 , 0
   -13.6    .035       0       0    .035       0      11    .035       0
#XS Ineff= 2 , 0
               0  115.35      11          115.85
Permanent Ineff=
       F       F
Bank Sta=0,11
XS Rating Curve= 0
Exp/Cntr=.3,.1

Type RM Length L Ch R = 1 ,1230.00 ,37,37,37
BEGIN DESCRIPTION:
23.037
END DESCRIPTION:
#Sta/Elev= 16
   -13.6  114.84    -3.6  114.85      -2  115.35       0  115.35      .9  114.85
       3  113.65       3  112.85     6.2  112.85     6.2  113.65     6.4  114.05
     6.6  114.55     8.7  114.55      11  115.85    13.4  115.85    13.8  115.55
    23.8  115.55
#Mann= 3 , 0 , 0
   -13.6    .035       0       0    .035       0      11    .035       0
#XS Ineff= 2 , 0
               0  115.35      11          115.85
Permanent Ineff=
       F       F
Bank Sta=0,11
XS Rating Curve= 0
Exp/Cntr=.3,.1

Type RM Length L Ch R = 1 ,1193.00 ,14,14,14
BEGIN DESCRIPTION:
23
END DESCRIPTION:
#Sta/Elev= 8
   -15.8  112.07    -5.8  112.07    -3.6  114.47       0  114.47     2.7  112.77
     7.7  112.77     8.7  114.37    18.7  114.37
#Mann= 3 , 0 , 0
   -15.8    .035       0       0    .035       0     8.7    .035       0
#XS Ineff= 2 , 0
               0  114.47     8.7          114.37
Permanent Ineff=
       F       F
Bank Sta=0,8.7
XS Rating Curve= 0
Exp/Cntr=.3,.1

Type RM Length L Ch R = 1 ,1179.00 ,36,36,36
BEGIN DESCRIPTION:
22.036
END DESCRIPTION:
#Sta/Elev= 8
   -15.8  111.83    -5.8  111.83    -3.6  114.23       0  114.23     2.7  112.53
     7.7  112.53     8.7  114.13    18.7  114.13
#Mann= 3 , 0 , 0
   -15.8    .035       0       0    .035       0     8.7    .035       0
#XS Ineff= 2 , 0
               0  114.23     8.7          114.13
Permanent Ineff=
       F       F
Bank Sta=0,8.7
XS Rating Curve= 0
Exp/Cntr=.3,.1

Type RM Length L Ch R = 1 ,1143.00 ,39,39,39
BEGIN DESCRIPTION:
22
END DESCRIPTION:
#Sta/Elev= 11
   -13.7  111.79    -3.7  111.79    -2.2  113.19       0  113.19     2.4  111.99
     3.7  111.69     7.7  111.69      10  112.89      13  112.89    13.3  112.59
    23.3  22.036
#Mann= 3 , 0 , 0
   -13.7    .035       0       0    .035       0      10    .035       0
#XS Ineff= 2 , 0
               0  113.19      10          112.89
Permanent Ineff=
       F       F
Bank Sta=0,10
XS Rating Curve= 0
Exp/Cntr=.3,.1

Type RM Length L Ch R = 1 ,1104.00 ,1,1,1
BEGIN DESCRIPTION:
21.011
END DESCRIPTION:
#Sta/Elev= 10
   -15.1  111.02    -5.1  111.02      -3  112.32       0  112.32     1.6  111.62
     9.6  111.62     9.6  112.02    12.6  112.02    12.9  111.92    22.9  111.92
#Mann= 3 , 0 , 0
   -15.1    .035       0       0    .035       0     9.6    .035       0
#XS Ineff= 2 , 0
               0  112.32     9.6          112.02
Permanent Ineff=
       F       F
Bank Sta=0,9.6
XS Rating Curve= 0
Exp/Cntr=.3,.1

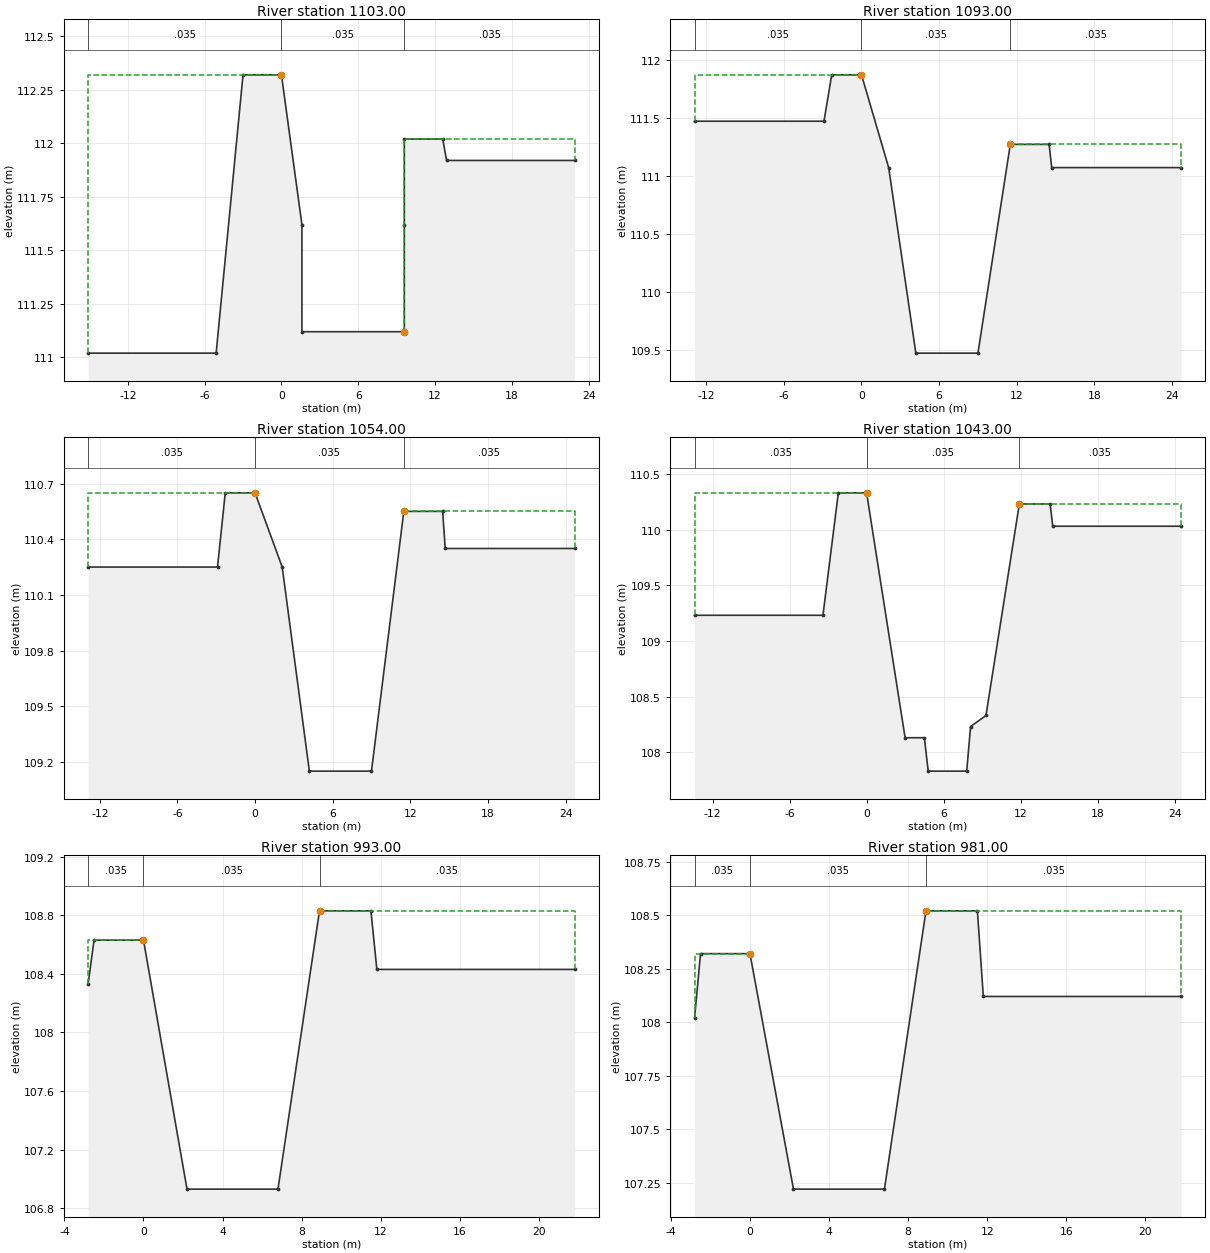
Type RM Length L Ch R = 1 ,1103.00 ,10,10,10
BEGIN DESCRIPTION:
21.01
END DESCRIPTION:
#Sta/Elev= 12
   -15.1  111.02    -5.1  111.02      -3  112.32       0  112.32     1.6  111.62
     1.6  111.12     9.6  111.12     9.6  111.62     9.6  112.02    12.6  112.02
    12.9  111.92    22.9  111.92
#Mann= 3 , 0 , 0
   -15.1    .035       0       0    .035       0     9.6    .035       0
#XS Ineff= 2 , 0
               0  112.32     9.6          112.02
Permanent Ineff=
       F       F
Bank Sta=0,9.6
XS Rating Curve= 0
Exp/Cntr=.3,.1

Type RM Length L Ch R = 1 ,1093.00 ,39,39,39
BEGIN DESCRIPTION:
21
END DESCRIPTION:
#Sta/Elev= 11
   -12.9  111.47    -2.9  111.47    -2.3  111.87       0  111.87     2.1  111.07
     4.2  109.47       9  109.47    11.5  111.27    14.5  111.27    14.7  111.07
    24.7  111.07
#Mann= 3 , 0 , 0
   -12.9    .035       0       0    .035       0    11.5    .035       0
#XS Ineff= 2 , 0
               0  111.87    11.5          111.27
Permanent Ineff=
       F       F
Bank Sta=0,11.5
XS Rating Curve= 0
Exp/Cntr=.3,.1

Type RM Length L Ch R = 1 ,1054.00 ,11,11,11
BEGIN DESCRIPTION:
20.011
END DESCRIPTION:
#Sta/Elev= 11
   -12.9  110.25    -2.9  110.25    -2.3  110.65       0  110.65     2.1  110.25
     4.2  109.15       9  109.15    11.5  110.55    14.5  110.55    14.7  110.35
    24.7  110.35
#Mann= 3 , 0 , 0
   -12.9    .035       0       0    .035       0    11.5    .035       0
#XS Ineff= 2 , 0
               0  110.65    11.5          110.55
Permanent Ineff=
       F       F
Bank Sta=0,11.5
XS Rating Curve= 0
Exp/Cntr=.3,.1

Type RM Length L Ch R = 1 ,1043.00 ,50,50,50
BEGIN DESCRIPTION:
20
END DESCRIPTION:
#Sta/Elev= 14
   -13.4  109.23    -3.4  109.23    -2.2  110.33       0  110.33       3  108.13
     4.5  108.13     4.8  107.83     7.8  107.83     8.1  108.23     9.3  108.33
    11.9  110.23    14.3  110.23    14.5  110.03    24.5  110.03
#Mann= 3 , 0 , 0
   -13.4    .035       0       0    .035       0    11.9    .035       0
#XS Ineff= 2 , 0
               0  110.33    11.9          110.23
Permanent Ineff=
       F       F
Bank Sta=0,11.9
XS Rating Curve= 0
Exp/Cntr=.3,.1

Type RM Length L Ch R = 1 ,993.00  ,12,12,12
BEGIN DESCRIPTION:
19
END DESCRIPTION:
#Sta/Elev= 9
    -2.8  108.33    -2.5  108.63       0  108.63     2.2  106.93     6.8  106.93
     8.9  108.83    11.5  108.83    11.8  108.43    21.8  108.43
#Mann= 3 , 0 , 0
    -2.8    .035       0       0    .035       0     8.9    .035       0
#XS Ineff= 2 , 0
               0  108.63     8.9          108.83
Permanent Ineff=
       F       F
Bank Sta=0,8.9
XS Rating Curve= 0
Exp/Cntr=.3,.1

Type RM Length L Ch R = 1 ,981.00  ,28,28,28
BEGIN DESCRIPTION:
18.038
END DESCRIPTION:
#Sta/Elev= 9
    -2.8  108.02    -2.5  108.32       0  108.32     2.2  107.22     6.8  107.22
     8.9  108.52    11.5  108.52    11.8  108.12    21.8  108.12
#Mann= 3 , 0 , 0
    -2.8    .035       0       0    .035       0     8.9    .035       0
#XS Ineff= 2 , 0
               0  108.32     8.9          108.52
Permanent Ineff=
       F       F
Bank Sta=0,8.9
XS Rating Curve= 0
Exp/Cntr=.3,.1

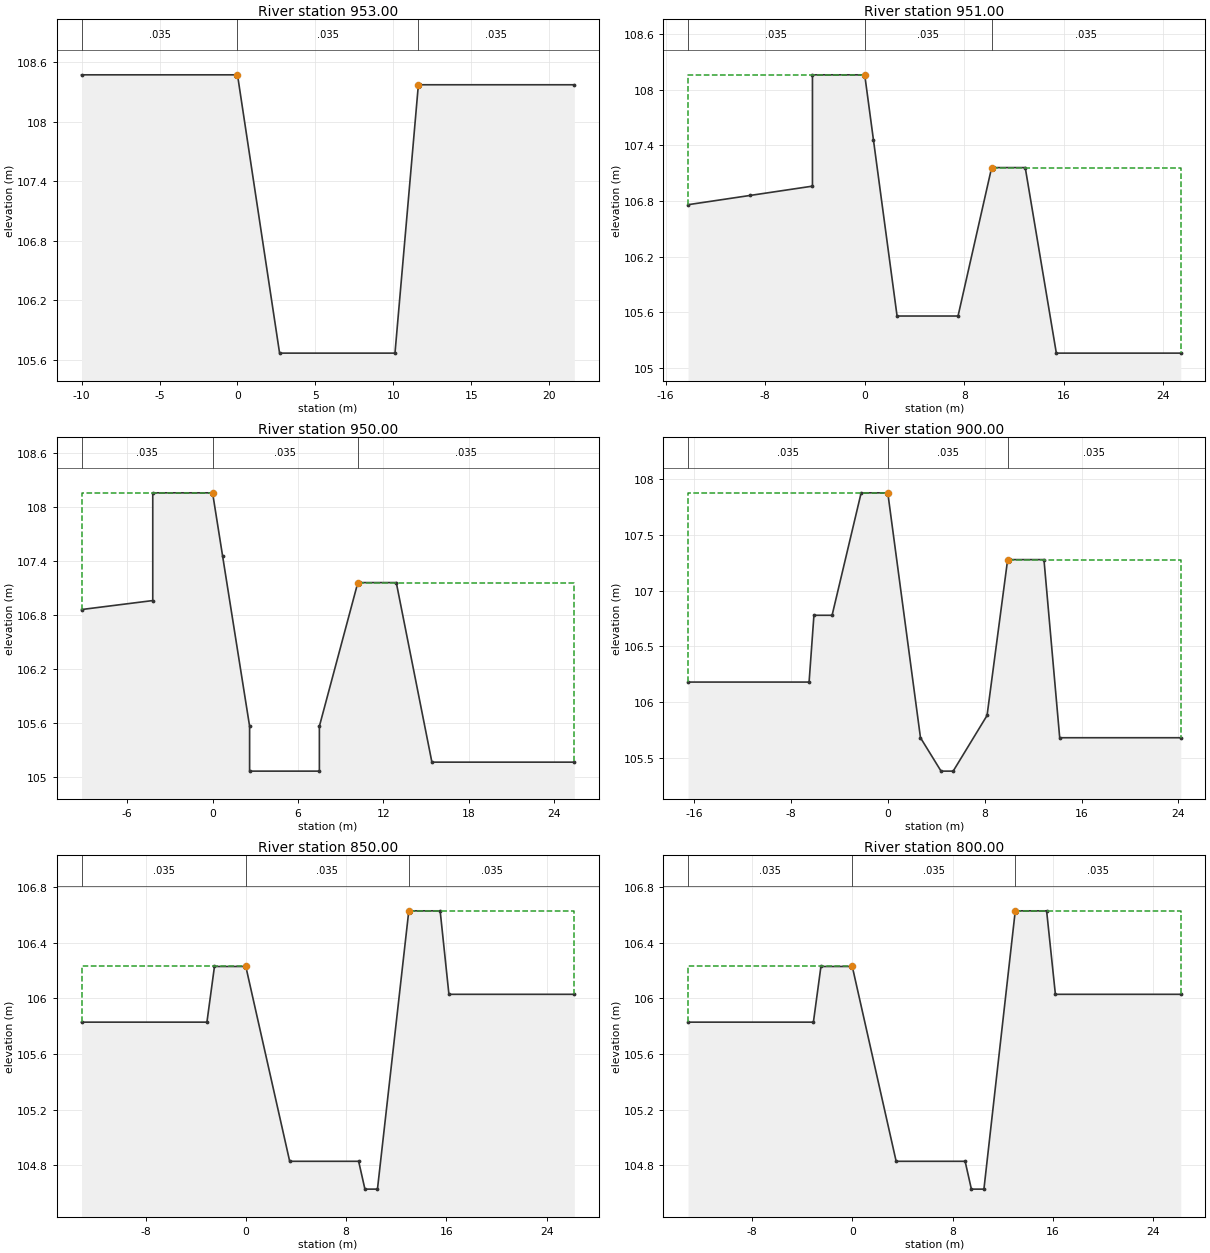
Type RM Length L Ch R = 1 ,953.00  ,2,2,2
BEGIN DESCRIPTION:
18.01
END DESCRIPTION:
#Sta/Elev= 6
     -10  108.47       0  108.47     2.7  105.67    10.1  105.67    11.6  108.37
    21.6  108.37
#Mann= 3 , 0 , 0
     -10    .035       0       0    .035       0    11.6    .035       0
#XS Ineff= 2 , 0
               0  108.47    11.6          108.37
Permanent Ineff=
       F       F
Bank Sta=0,11.6
XS Rating Curve= 0
Exp/Cntr=.3,.1

Type RM Length L Ch R = 1 ,951.00  ,1,1,1
BEGIN DESCRIPTION:
18.008
END DESCRIPTION:
#Sta/Elev= 12
   -14.2  106.76    -9.2  106.86    -4.2  106.96    -4.2  108.16       0  108.16
      .7  107.46     2.6  105.56     7.5  105.56    10.2  107.16    12.9  107.16
    15.4  105.16    25.4  105.16
#Mann= 3 , 0 , 0
   -14.2    .035       0       0    .035       0    10.2    .035       0
#XS Ineff= 2 , 0
               0  108.16    10.2          107.16
Permanent Ineff=
       F       F
Bank Sta=0,10.2
XS Rating Curve= 0
Exp/Cntr=.3,.1

Type RM Length L Ch R = 1 ,950.00  ,50,50,50
BEGIN DESCRIPTION:
18.007
END DESCRIPTION:
#Sta/Elev= 13
    -9.2  106.86    -4.2  106.96    -4.2  108.16       0  108.16      .7  107.46
     2.6  105.56     2.6  105.06     7.5  105.06     7.5  105.56    10.2  107.16
    12.9  107.16    15.4  105.16    25.4  105.16
#Mann= 3 , 0 , 0
    -9.2    .035       0       0    .035       0    10.2    .035       0
#XS Ineff= 2 , 0
               0  108.16    10.2          107.16
Permanent Ineff=
       F       F
Bank Sta=0,10.2
XS Rating Curve= 0
Exp/Cntr=.3,.1

Type RM Length L Ch R = 1 ,900.00  ,50,50,50
BEGIN DESCRIPTION:
18
END DESCRIPTION:
#Sta/Elev= 14
   -16.5  106.18    -6.5  106.18    -6.1  106.78    -4.6  106.78    -2.2  107.88
       0  107.88     2.7  105.68     4.4  105.38     5.4  105.38     8.2  105.88
     9.9  107.28    12.9  107.28    14.2  105.68    24.2  105.68
#Mann= 3 , 0 , 0
   -16.5    .035       0       0    .035       0     9.9    .035       0
#XS Ineff= 2 , 0
               0  107.88     9.9          107.28
Permanent Ineff=
       F       F
Bank Sta=0,9.9
XS Rating Curve= 0
Exp/Cntr=.3,.1

Type RM Length L Ch R = 1 ,850.00  ,50,50,50
BEGIN DESCRIPTION:
17
END DESCRIPTION:
#Sta/Elev= 12
   -13.1  105.83    -3.1  105.83    -2.5  106.23       0  106.23     3.5  104.83
       9  104.83     9.5  104.63    10.5  104.63      13  106.63    15.5  106.63
    16.2  106.03    26.2  106.03
#Mann= 3 , 0 , 0
   -13.1    .035       0       0    .035       0      13    .035       0
#XS Ineff= 2 , 0
               0  106.23      13          106.63
Permanent Ineff=
       F       F
Bank Sta=0,13
XS Rating Curve= 0
Exp/Cntr=.3,.1

Type RM Length L Ch R = 1 ,800.00  ,10,10,10
BEGIN DESCRIPTION:
16
END DESCRIPTION:
#Sta/Elev= 12
   -13.1  105.83    -3.1  105.83    -2.5  106.23       0  106.23     3.5  104.83
       9  104.83     9.5  104.63    10.5  104.63      13  106.63    15.5  106.63
    16.2  106.03    26.2  106.03
#Mann= 3 , 0 , 0
   -13.1    .035       0       0    .035       0      13    .035       0
#XS Ineff= 2 , 0
               0  106.23      13          106.63
Permanent Ineff=
       F       F
Bank Sta=0,13
XS Rating Curve= 0
Exp/Cntr=.3,.1

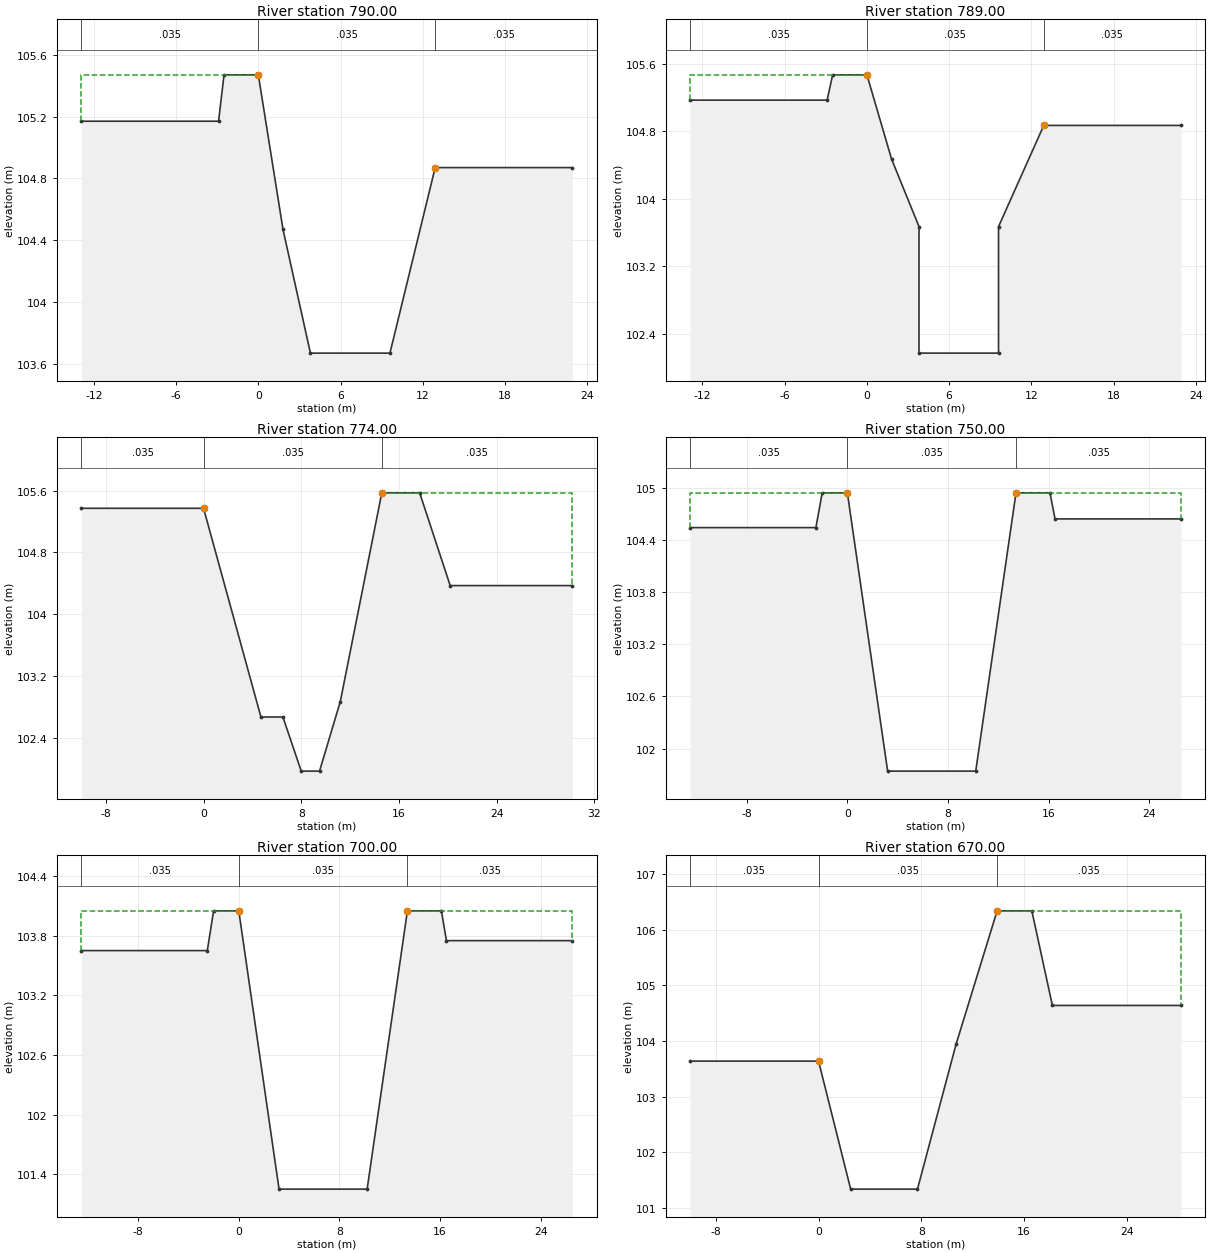
Type RM Length L Ch R = 1 ,790.00  ,1,1,1
BEGIN DESCRIPTION:
15.04
END DESCRIPTION:
#Sta/Elev= 9
   -12.9  105.17    -2.9  105.17    -2.5  105.47       0  105.47     1.8  104.47
     3.8  103.67     9.6  103.67    12.9  104.87    22.9  104.87
#Mann= 3 , 0 , 0
   -12.9    .035       0       0    .035       0    12.9    .035       0
#XS Ineff= 2 , 0
               0  105.47    12.9          104.87
Permanent Ineff=
       F       F
Bank Sta=0,12.9
XS Rating Curve= 0
Exp/Cntr=.3,.1

Type RM Length L Ch R = 1 ,789.00  ,15,15,15
BEGIN DESCRIPTION:
15.039
END DESCRIPTION:
#Sta/Elev= 11
   -12.9  105.17    -2.9  105.17    -2.5  105.47       0  105.47     1.8  104.47
     3.8  103.67     3.8  102.17     9.6  102.17     9.6  103.67    12.9  104.87
    22.9  104.87
#Mann= 3 , 0 , 0
   -12.9    .035       0       0    .035       0    12.9    .035       0
#XS Ineff= 2 , 0
               0  105.47    12.9          104.87
Permanent Ineff=
       F       F
Bank Sta=0,12.9
XS Rating Curve= 0
Exp/Cntr=.3,.1

Type RM Length L Ch R = 1 ,774.00  ,24,24,24
BEGIN DESCRIPTION:
15.024
END DESCRIPTION:
#Sta/Elev= 11
     -10  105.37       0  105.37     4.7  102.67     6.5  102.67       8  101.97
     9.5  101.97    11.2  102.87    14.6  105.57    17.7  105.57    20.2  104.37
    30.2  104.37
#Mann= 3 , 0 , 0
     -10    .035       0       0    .035       0    14.6    .035       0
#XS Ineff= 2 , 0
               0  105.37    14.6          105.57
Permanent Ineff=
       F       F
Bank Sta=0,14.6
XS Rating Curve= 0
Exp/Cntr=.3,.1

Type RM Length L Ch R = 1 ,750.00  ,50,50,50
BEGIN DESCRIPTION:
15
END DESCRIPTION:
#Sta/Elev= 10
   -12.5  104.54    -2.5  104.54      -2  104.94       0  104.94     3.2  101.74
    10.2  101.74    13.4  104.94    16.1  104.94    16.5  104.64    26.5  104.64
#Mann= 3 , 0 , 0
   -12.5    .035       0       0    .035       0    13.4    .035       0
#XS Ineff= 2 , 0
               0  104.94    13.4          104.94
Permanent Ineff=
       F       F
Bank Sta=0,13.4
XS Rating Curve= 0
Exp/Cntr=.3,.1

Type RM Length L Ch R = 1 ,700.00  ,30,30,30
BEGIN DESCRIPTION:
14
END DESCRIPTION:
#Sta/Elev= 10
   -12.5  103.65    -2.5  103.65      -2  104.05       0  104.05     3.2  101.25
    10.2  101.25    13.4  104.05    16.1  104.05    16.5  103.75    26.5  103.75
#Mann= 3 , 0 , 0
   -12.5    .035       0       0    .035       0    13.4    .035       0
#XS Ineff= 2 , 0
               0  104.05    13.4          104.05
Permanent Ineff=
       F       F
Bank Sta=0,13.4
XS Rating Curve= 0
Exp/Cntr=.3,.1

Type RM Length L Ch R = 1 ,670.00  ,20,20,20
BEGIN DESCRIPTION:
13.02
END DESCRIPTION:
#Sta/Elev= 9
     -10  103.64       0  103.64     2.5  101.34     7.7  101.34    10.7  103.94
    13.9  106.34    16.6  106.34    18.2  104.64    28.2  104.64
#Mann= 3 , 0 , 0
     -10    .035       0       0    .035       0    13.9    .035       0
#XS Ineff= 2 , 0
               0  103.64    13.9          106.34
Permanent Ineff=
       F       F
Bank Sta=0,13.9
XS Rating Curve= 0
Exp/Cntr=.3,.1

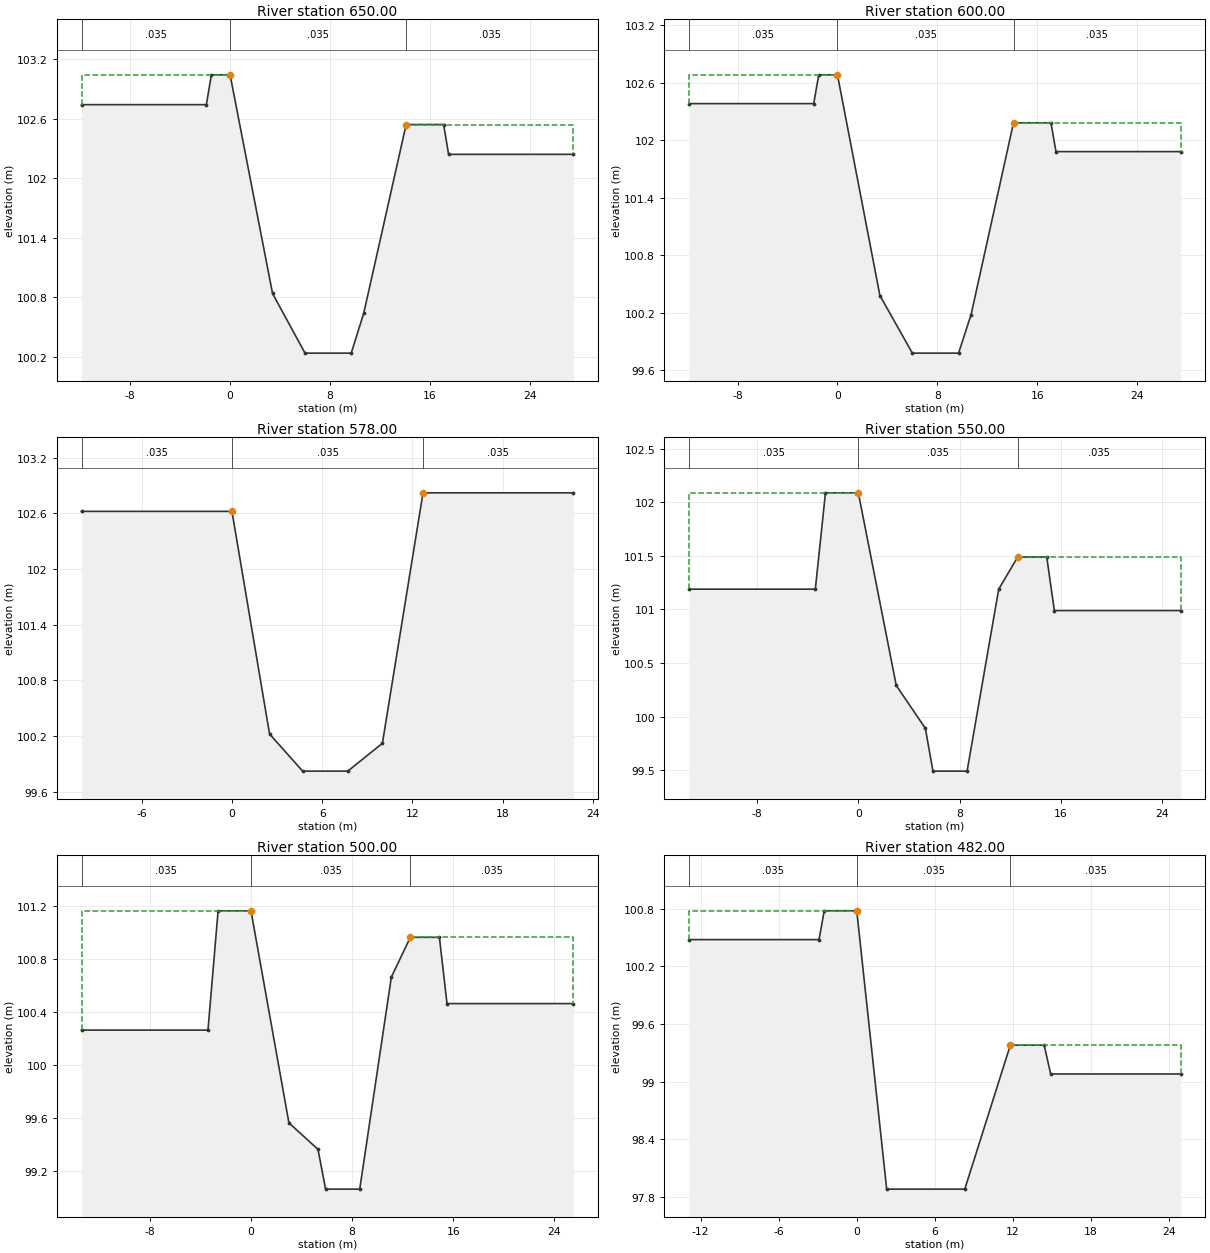
Type RM Length L Ch R = 1 ,650.00  ,50,50,50
BEGIN DESCRIPTION:
13
END DESCRIPTION:
#Sta/Elev= 12
   -11.9  102.74    -1.9  102.74    -1.5  103.04       0  103.04     3.4  100.84
       6  100.24     9.7  100.24    10.7  100.64    14.1  102.54    17.1  102.54
    17.5  102.24    27.5  102.24
#Mann= 3 , 0 , 0
   -11.9    .035       0       0    .035       0    14.1    .035       0
#XS Ineff= 2 , 0
               0  103.04    14.1          102.54
Permanent Ineff=
       F       F
Bank Sta=0,14.1
XS Rating Curve= 0
Exp/Cntr=.3,.1

Type RM Length L Ch R = 1 ,600.00  ,22,22,22
BEGIN DESCRIPTION:
12
END DESCRIPTION:
#Sta/Elev= 12
   -11.9  102.38    -1.9  102.38    -1.5  102.68       0  102.68     3.4  100.38
       6   99.78     9.7   99.78    10.7  100.18    14.1  102.18    17.1  102.18
    17.5  101.88    27.5  101.88
#Mann= 3 , 0 , 0
   -11.9    .035       0       0    .035       0    14.1    .035       0
#XS Ineff= 2 , 0
               0  102.68    14.1          102.18
Permanent Ineff=
       F       F
Bank Sta=0,14.1
XS Rating Curve= 0
Exp/Cntr=.3,.1

Type RM Length L Ch R = 1 ,578.00  ,28,28,28
BEGIN DESCRIPTION:
11.028
END DESCRIPTION:
#Sta/Elev= 8
     -10  102.62       0  102.62     2.5  100.22     4.7   99.82     7.7   99.82
      10  100.12    12.7  102.82    22.7  102.82
#Mann= 3 , 0 , 0
     -10    .035       0       0    .035       0    12.7    .035       0
#XS Ineff= 2 , 0
               0  102.62    12.7          102.82
Permanent Ineff=
       F       F
Bank Sta=0,12.7
XS Rating Curve= 0
Exp/Cntr=.3,.1

Type RM Length L Ch R = 1 ,550.00  ,50,50,50
BEGIN DESCRIPTION:
11
END DESCRIPTION:
#Sta/Elev= 13
   -13.4  101.19    -3.4  101.19    -2.6  102.09       0  102.09       3  100.29
     5.3   99.89     5.9   99.49     8.6   99.49    11.1  101.19    12.6  101.49
    14.9  101.49    15.5  100.99    25.5  100.99
#Mann= 3 , 0 , 0
   -13.4    .035       0       0    .035       0    12.6    .035       0
#XS Ineff= 2 , 0
               0  102.09    12.6          101.49
Permanent Ineff=
       F       F
Bank Sta=0,12.6
XS Rating Curve= 0
Exp/Cntr=.3,.1

Type RM Length L Ch R = 1 ,500.00  ,18,18,18
BEGIN DESCRIPTION:
10
END DESCRIPTION:
#Sta/Elev= 13
   -13.4  100.26    -3.4  100.26    -2.6  101.16       0  101.16       3   99.56
     5.3   99.36     5.9   99.06     8.6   99.06    11.1  100.66    12.6  100.96
    14.9  100.96    15.5  100.46    25.5  100.46
#Mann= 3 , 0 , 0
   -13.4    .035       0       0    .035       0    12.6    .035       0
#XS Ineff= 2 , 0
               0  101.16    12.6          100.96
Permanent Ineff=
       F       F
Bank Sta=0,12.6
XS Rating Curve= 0
Exp/Cntr=.3,.1

Type RM Length L Ch R = 1 ,482.00  ,32,32,32
BEGIN DESCRIPTION:
9.032
END DESCRIPTION:
#Sta/Elev= 10
   -12.9  100.48    -2.9  100.48    -2.5  100.78       0  100.78     2.3   97.88
     8.3   97.88    11.8   99.38    14.4   99.38    14.9   99.08    24.9   99.08
#Mann= 3 , 0 , 0
   -12.9    .035       0       0    .035       0    11.8    .035       0
#XS Ineff= 2 , 0
               0  100.78    11.8           99.38
Permanent Ineff=
       F       F
Bank Sta=0,11.8
XS Rating Curve= 0
Exp/Cntr=.3,.1

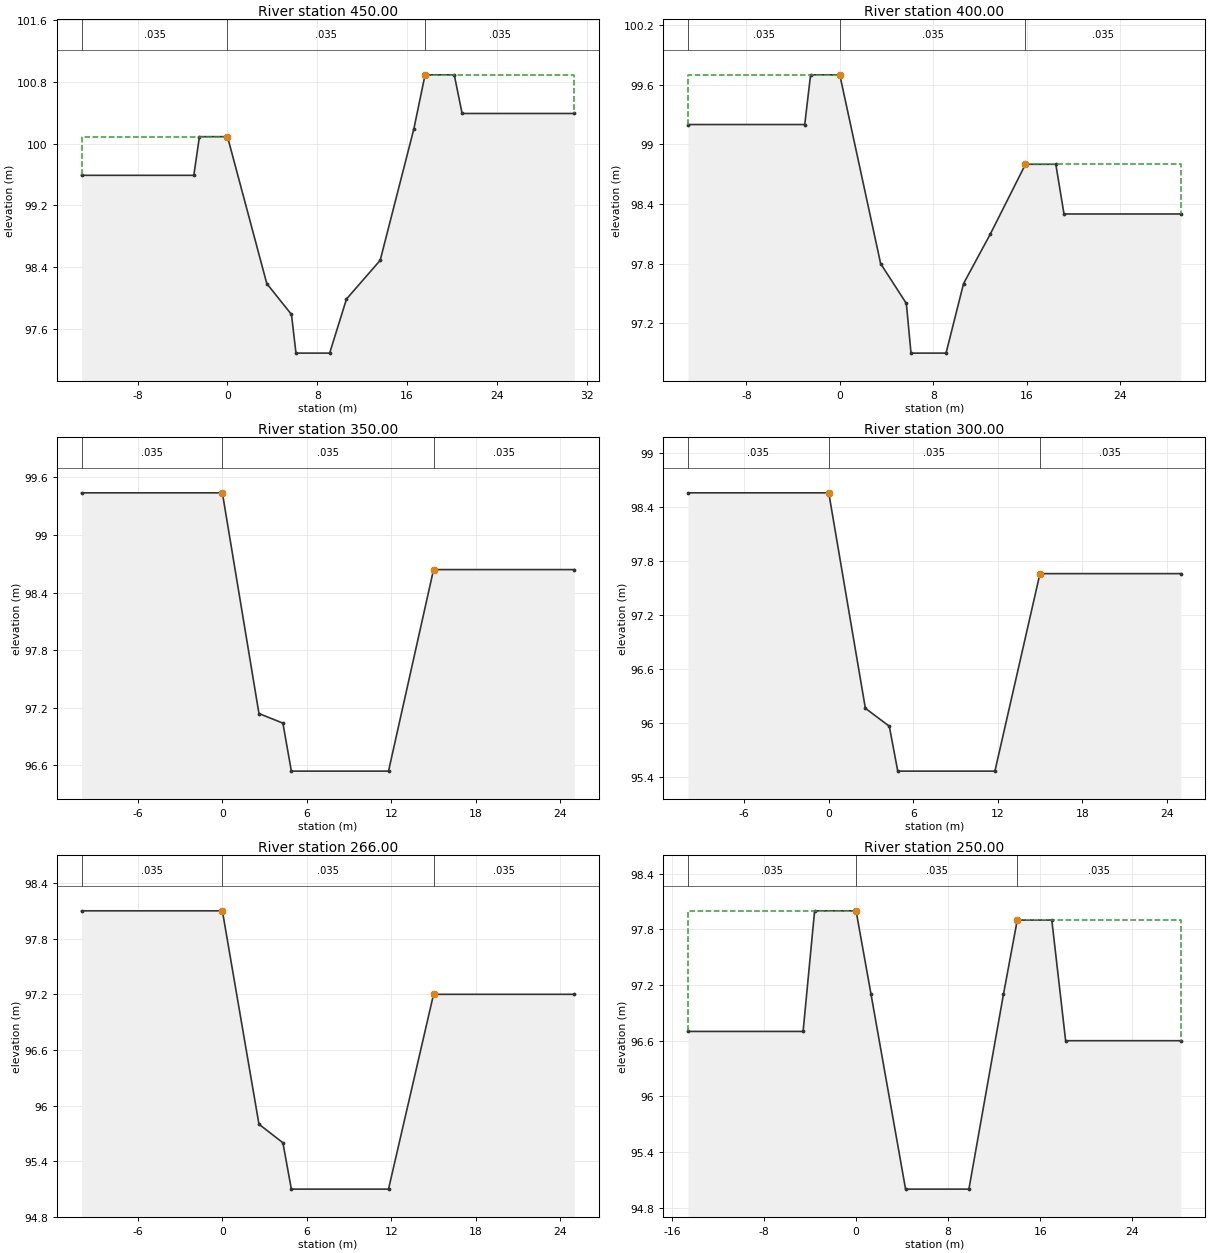
Type RM Length L Ch R = 1 ,450.00  ,50,50,50
BEGIN DESCRIPTION:
9
END DESCRIPTION:
#Sta/Elev= 15
     -13   99.59      -3   99.59    -2.5  100.09       0  100.09     3.5   98.19
     5.7   97.79     6.1   97.29     9.1   97.29    10.6   97.99    13.6   98.49
    16.6  100.19    17.6  100.89    20.2  100.89    20.9  100.39    30.9  100.39
#Mann= 3 , 0 , 0
     -13    .035       0       0    .035       0    17.6    .035       0
#XS Ineff= 2 , 0
               0  100.09    17.6          100.89
Permanent Ineff=
       F       F
Bank Sta=0,17.6
XS Rating Curve= 0
Exp/Cntr=.3,.1

Type RM Length L Ch R = 1 ,400.00  ,50,50,50
BEGIN DESCRIPTION:
8
END DESCRIPTION:
#Sta/Elev= 14
     -13    99.2      -3    99.2    -2.5    99.7       0    99.7     3.5    97.8
     5.7    97.4     6.1    96.9     9.1    96.9    10.6    97.6    12.9    98.1
    15.9    98.8    18.5    98.8    19.2    98.3    29.2    98.3
#Mann= 3 , 0 , 0
     -13    .035       0       0    .035       0    15.9    .035       0
#XS Ineff= 2 , 0
               0    99.7    15.9            98.8
Permanent Ineff=
       F       F
Bank Sta=0,15.9
XS Rating Curve= 0
Exp/Cntr=.3,.1

Type RM Length L Ch R = 1 ,350.00  ,50,50,50
BEGIN DESCRIPTION:
7
END DESCRIPTION:
#Sta/Elev= 8
     -10   99.44       0   99.44     2.6   97.14     4.3   97.04     4.9   96.54
    11.8   96.54      15   98.64      25   98.64
#Mann= 3 , 0 , 0
     -10    .035       0       0    .035       0      15    .035       0
#XS Ineff= 2 , 0
               0   99.44      15           98.64
Permanent Ineff=
       F       F
Bank Sta=0,15
XS Rating Curve= 0
Exp/Cntr=.3,.1

Type RM Length L Ch R = 1 ,300.00  ,34,34,34
BEGIN DESCRIPTION:
6
END DESCRIPTION:
#Sta/Elev= 8
     -10   98.56       0   98.56     2.6   96.16     4.3   95.96     4.9   95.46
    11.8   95.46      15   97.66      25   97.66
#Mann= 3 , 0 , 0
     -10    .035       0       0    .035       0      15    .035       0
#XS Ineff= 2 , 0
               0   98.56      15           97.66
Permanent Ineff=
       F       F
Bank Sta=0,15
XS Rating Curve= 0
Exp/Cntr=.3,.1

Type RM Length L Ch R = 1 ,266.00  ,16,16,16
BEGIN DESCRIPTION:
5.016
END DESCRIPTION:
#Sta/Elev= 8
     -10    98.1       0    98.1     2.6    95.8     4.3    95.6     4.9    95.1
    11.8    95.1      15    97.2      25    97.2
#Mann= 3 , 0 , 0
     -10    .035       0       0    .035       0      15    .035       0
#XS Ineff= 2 , 0
               0    98.1      15            97.2
Permanent Ineff=
       F       F
Bank Sta=0,15
XS Rating Curve= 0
Exp/Cntr=.3,.1

Type RM Length L Ch R = 1 ,250.00  ,50,50,50
BEGIN DESCRIPTION:
5
END DESCRIPTION:
#Sta/Elev= 12
   -14.6    96.7    -4.6    96.7    -3.6      98       0      98     1.3    97.1
     4.3      95     9.8      95    12.8    97.1      14    97.9      17    97.9
    18.2    96.6    28.2    96.6
#Mann= 3 , 0 , 0
   -14.6    .035       0       0    .035       0      14    .035       0
#XS Ineff= 2 , 0
               0      98      14            97.9
Permanent Ineff=
       F       F
Bank Sta=0,14
XS Rating Curve= 0
Exp/Cntr=.3,.1

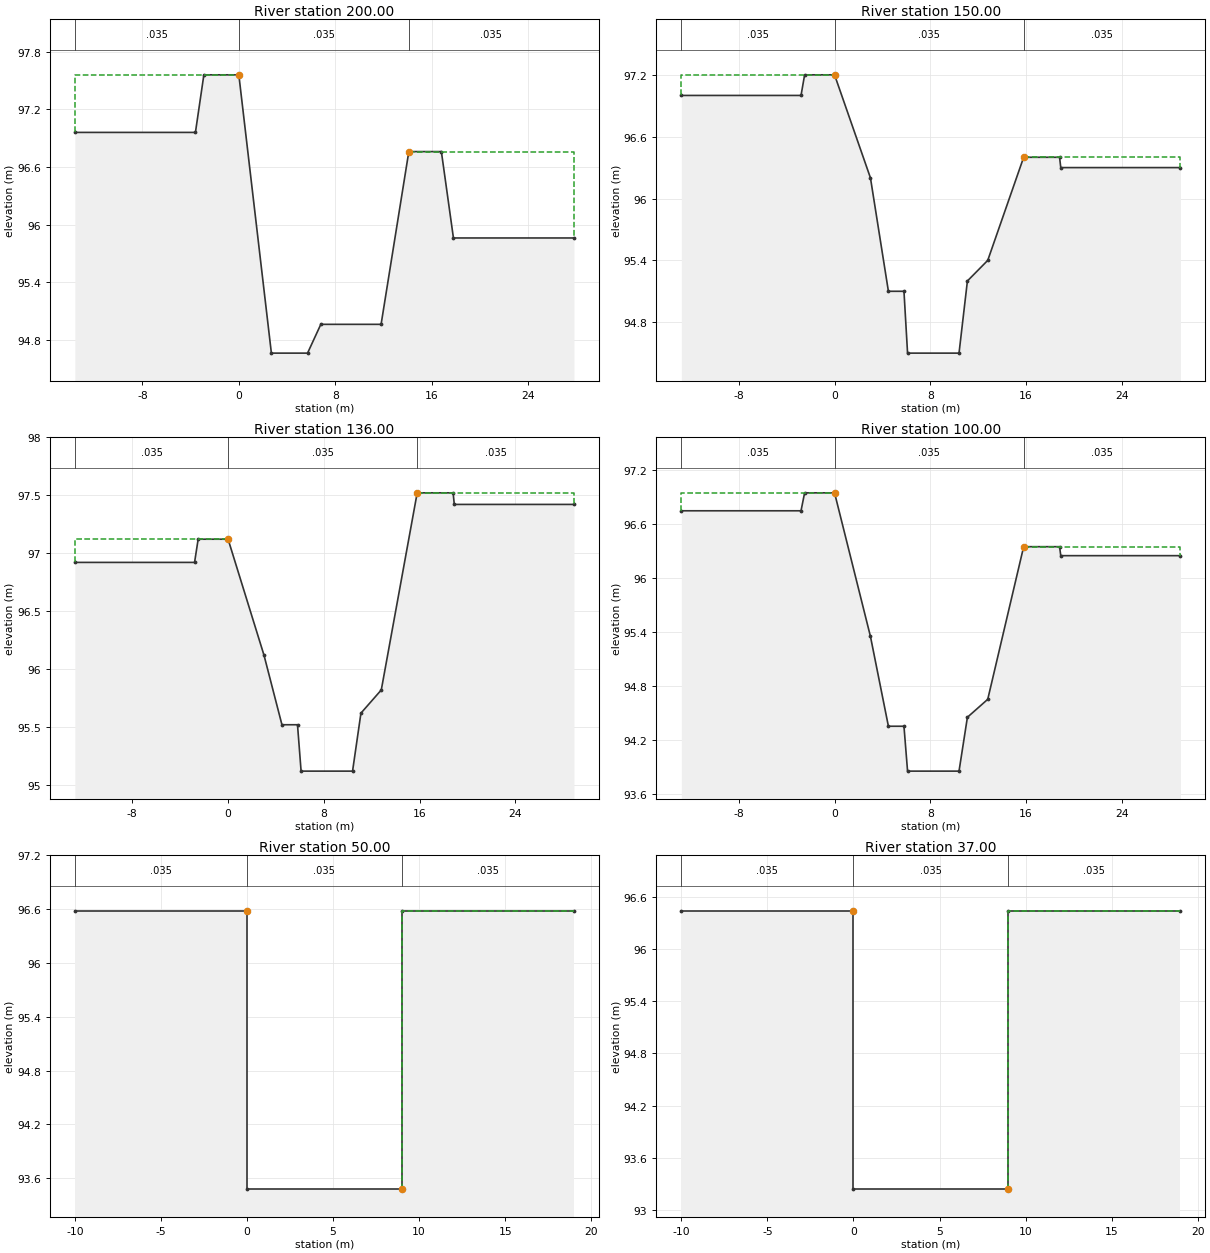
Type RM Length L Ch R = 1 ,200.00  ,50,50,50
BEGIN DESCRIPTION:
4
END DESCRIPTION:
#Sta/Elev= 12
   -13.6   96.96    -3.6   96.96    -2.9   97.56       0   97.56     2.7   94.66
     5.7   94.66     6.8   94.96    11.8   94.96    14.1   96.76    16.8   96.76
    17.8   95.86    27.8   95.86
#Mann= 3 , 0 , 0
   -13.6    .035       0       0    .035       0    14.1    .035       0
#XS Ineff= 2 , 0
               0   97.56    14.1           96.76
Permanent Ineff=
       F       F
Bank Sta=0,14.1
XS Rating Curve= 0
Exp/Cntr=.3,.1

Type RM Length L Ch R = 1 ,150.00  ,14,14,14
BEGIN DESCRIPTION:
3
END DESCRIPTION:
#Sta/Elev= 15
   -12.8      97    -2.8      97    -2.5    97.2       0    97.2       3    96.2
     4.5    95.1     5.8    95.1     6.1    94.5    10.4    94.5    11.1    95.2
    12.8    95.4    15.8    96.4    18.8    96.4    18.9    96.3    28.9    96.3
#Mann= 3 , 0 , 0
   -12.8    .035       0       0    .035       0    15.8    .035       0
#XS Ineff= 2 , 0
               0    97.2    15.8            96.4
Permanent Ineff=
       F       F
Bank Sta=0,15.8
XS Rating Curve= 0
Exp/Cntr=.3,.1

Type RM Length L Ch R = 1 ,136.00  ,36,36,36
BEGIN DESCRIPTION:
2.036
END DESCRIPTION:
#Sta/Elev= 15
   -12.8   96.92    -2.8   96.92    -2.5   97.12       0   97.12       3   96.12
     4.5   95.52     5.8   95.52     6.1   95.12    10.4   95.12    11.1   95.62
    12.8   95.82    15.8   97.52    18.8   97.52    18.9   97.42    28.9   97.42
#Mann= 3 , 0 , 0
   -12.8    .035       0       0    .035       0    15.8    .035       0
#XS Ineff= 2 , 0
               0   97.12    15.8           97.52
Permanent Ineff=
       F       F
Bank Sta=0,15.8
XS Rating Curve= 0
Exp/Cntr=.3,.1

Type RM Length L Ch R = 1 ,100.00  ,50,50,50
BEGIN DESCRIPTION:
2
END DESCRIPTION:
#Sta/Elev= 15
   -12.8   96.75    -2.8   96.75    -2.5   96.95       0   96.95       3   95.35
     4.5   94.35     5.8   94.35     6.1   93.85    10.4   93.85    11.1   94.45
    12.8   94.65    15.8   96.35    18.8   96.35    18.9   96.25    28.9   96.25
#Mann= 3 , 0 , 0
   -12.8    .035       0       0    .035       0    15.8    .035       0
#XS Ineff= 2 , 0
               0   96.95    15.8           96.35
Permanent Ineff=
       F       F
Bank Sta=0,15.8
XS Rating Curve= 0
Exp/Cntr=.3,.1

Type RM Length L Ch R = 1 ,50.00   ,13,13,13
BEGIN DESCRIPTION:
1
END DESCRIPTION:
#Sta/Elev= 6
     -10   96.58       0   96.58       0   93.48       9   93.48       9   96.58
      19   96.58
#Mann= 3 , 0 , 0
     -10    .035       0       0    .035       0       9    .035       0
#XS Ineff= 2 , 0
               0   96.58       9           96.58
Permanent Ineff=
       F       F
Bank Sta=0,9
XS Rating Curve= 0
Exp/Cntr=.3,.1

Type RM Length L Ch R = 1 ,37.00   ,21,21,21
BEGIN DESCRIPTION:
0.037
END DESCRIPTION:
#Sta/Elev= 6
     -10   96.44       0   96.44       0   93.24       9   93.24       9   96.44
      19   96.44
#Mann= 3 , 0 , 0
     -10    .035       0       0    .035       0       9    .035       0
#XS Ineff= 2 , 0
               0   96.44       9           96.44
Permanent Ineff=
       F       F
Bank Sta=0,9
XS Rating Curve= 0
Exp/Cntr=.3,.1

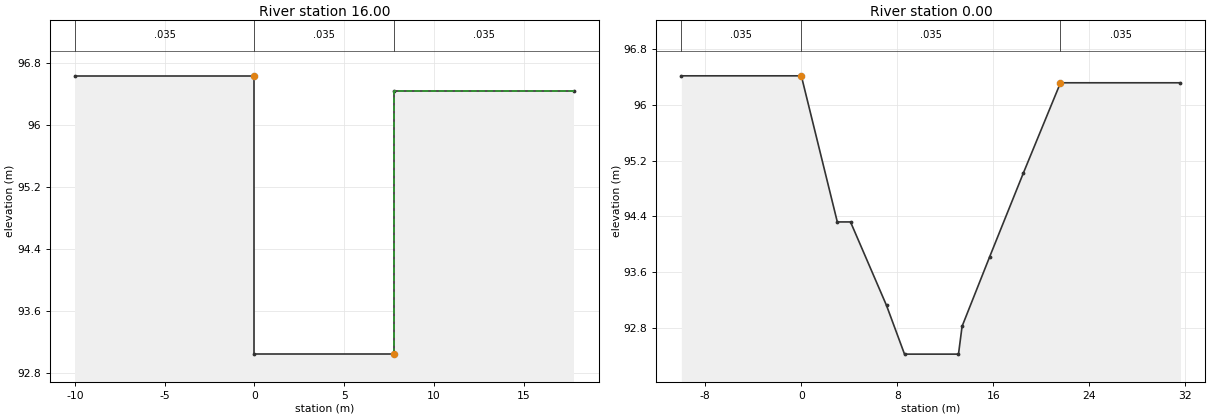
Type RM Length L Ch R = 1 ,16.00   ,16,16,16
BEGIN DESCRIPTION:
0.016
END DESCRIPTION:
#Sta/Elev= 6
     -10   96.64       0   96.64       0   93.04     7.8   93.04     7.8   96.44
    17.8   96.44
#Mann= 3 , 0 , 0
     -10    .035       0       0    .035       0     7.8    .035       0
#XS Ineff= 2 , 0
               0   96.64     7.8           96.44
Permanent Ineff=
       F       F
Bank Sta=0,7.8
XS Rating Curve= 0
Exp/Cntr=.3,.1

Type RM Length L Ch R = 1 ,0.00    ,0,0,0
BEGIN DESCRIPTION:
0
END DESCRIPTION:
#Sta/Elev= 12
     -10   96.42       0   96.42       3   94.32     4.1   94.32     7.1   93.12
     8.6   92.42    13.1   92.42    13.4   92.82    15.7   93.82    18.5   95.02
    21.6   96.32    31.6   96.32
#Mann= 3 , 0 , 0
     -10    .035       0       0    .035       0    21.6    .035       0
#XS Ineff= 2 , 0
               0   96.42    21.6           96.32
Permanent Ineff=
       F       F
Bank Sta=0,21.6
XS Rating Curve= 0
Exp/Cntr=.3,.1

Chan Stop Cuts=-1