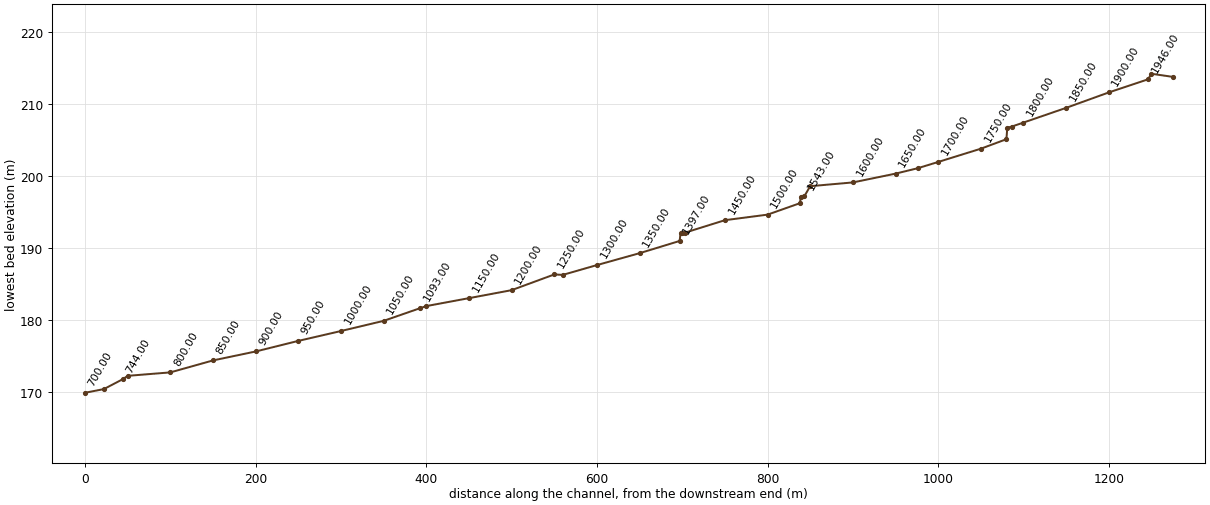
--- MBC.prj (project) ---

Proj Title=meukbang-ch
Current Plan=p01
Default Exp/Contr=.3,.1
SI Units
Geom File=g01
Flow File=f01
Plan File=p01
Y Axis Title=Elevation
X Axis Title(PF)=Main Channel Distance
X Axis Title(XS)=Station
BEGIN DESCRIPTION:
           BACK WATER COMPUTATION
      APPLICATION OF HEC-2 BY Samju Construction Engineering
      meukbang-ch: 10,20,30,50,80 yr
END DESCRIPTION:
DSS Export Rating Curves= 0
DSS Export Rating Curve Sorted= 0
DSS Export Volume Flow Curves= 0
DXF OffsetX= 0
DXF OffsetY= 0
DXF ScaleX= 1
DXF ScaleY= 10

--- MBC.p01 (plan) ---

Plan Title=Imported Plan 01
Version=Version 3.0.1  Mar 2001
Short Identifier=Imported Pla
Geom File=g01
Flow File=f01
Subcritical Flow
K Sum by GR= 0
Std Step Tol= 0.003
Critical Tol= 0.003
Num of Std Step Trials= 20
Max Error Tol= 0.1
Flow Tol Ratio= 0.001
Split Flow NTrial= 30
Split Flow Tol= 0.02
Split Flow Ratio= 0.02
Log Output Level= 0
Friction Slope Method= 1
Unsteady Friction Slope Method= 2
Parabolic Critical Depth
Global Vel Dist= 0 , 0 , 0
Global Log Level= 0
CheckData=True
Encroach Param=-1 ,0,0, 0
Computation Interval=1HOUR
Output Interval=1HOUR
Run HTab= 0
Run UNet= 0
Run PostProcess= 0
UNET Theta= 1
UNET ZTol= 0.02
UNET ZSATol= 0.1
UNET MxIter= 20
UNET MaxInSteps= 20
UNET DtIC= 0
UNET DtMin= 0
UNET MaxCRTS= 20
UNET WFStab= 2
UNET SFStab= 1
UNET WFX= 1
UNET SFX= 1
UNET Convert EG Bridges=-1
UNET Use Existing IB Tables=-1
Instantaneous Interval=1HOUR
Write IC File= 0
Write Velocity= 0
Write Detailed= 0

--- MBC.f01 (steady flow) ---

Flow Title=Imported Flow 01
Version=Version 3.0.1  Mar 2001
Number of Profiles= 5
Profile Names=10YR,20YR,30YR,50YR,80YR
River Rch & RM=RIVER-1,Reach-1         ,1975.00
   32.41   35.72   37.65   40.09   42.34
River Rch & RM=RIVER-1,Reach-1         ,900.00
   40.44   44.59   47.01   50.06   52.87
Boundary for River Rch & Prof#=RIVER-1,Reach-1         , 1
Up Type= 0
Dn Type= 3
Dn Slope=.032
Boundary for River Rch & Prof#=RIVER-1,Reach-1         , 2
Up Type= 0
Dn Type= 3
Dn Slope=.032
Boundary for River Rch & Prof#=RIVER-1,Reach-1         , 3
Up Type= 0
Dn Type= 3
Dn Slope=.032
Boundary for River Rch & Prof#=RIVER-1,Reach-1         , 4
Up Type= 0
Dn Type= 3
Dn Slope=.032
Boundary for River Rch & Prof#=RIVER-1,Reach-1         , 5
Up Type= 0
Dn Type= 3
Dn Slope=.032
DSS Import GetInterval= 0
DSS Import GetPeak= 0
DSS Import FillOption= 0

--- MBC.g01 (geometry) ---

Geom Title=Imported Geom 01
Version=Version 3.0.1  Mar 2001

River Reach=RIVER-1         ,Reach-1
Reach XY= 2
              .5             .95              .5             .05

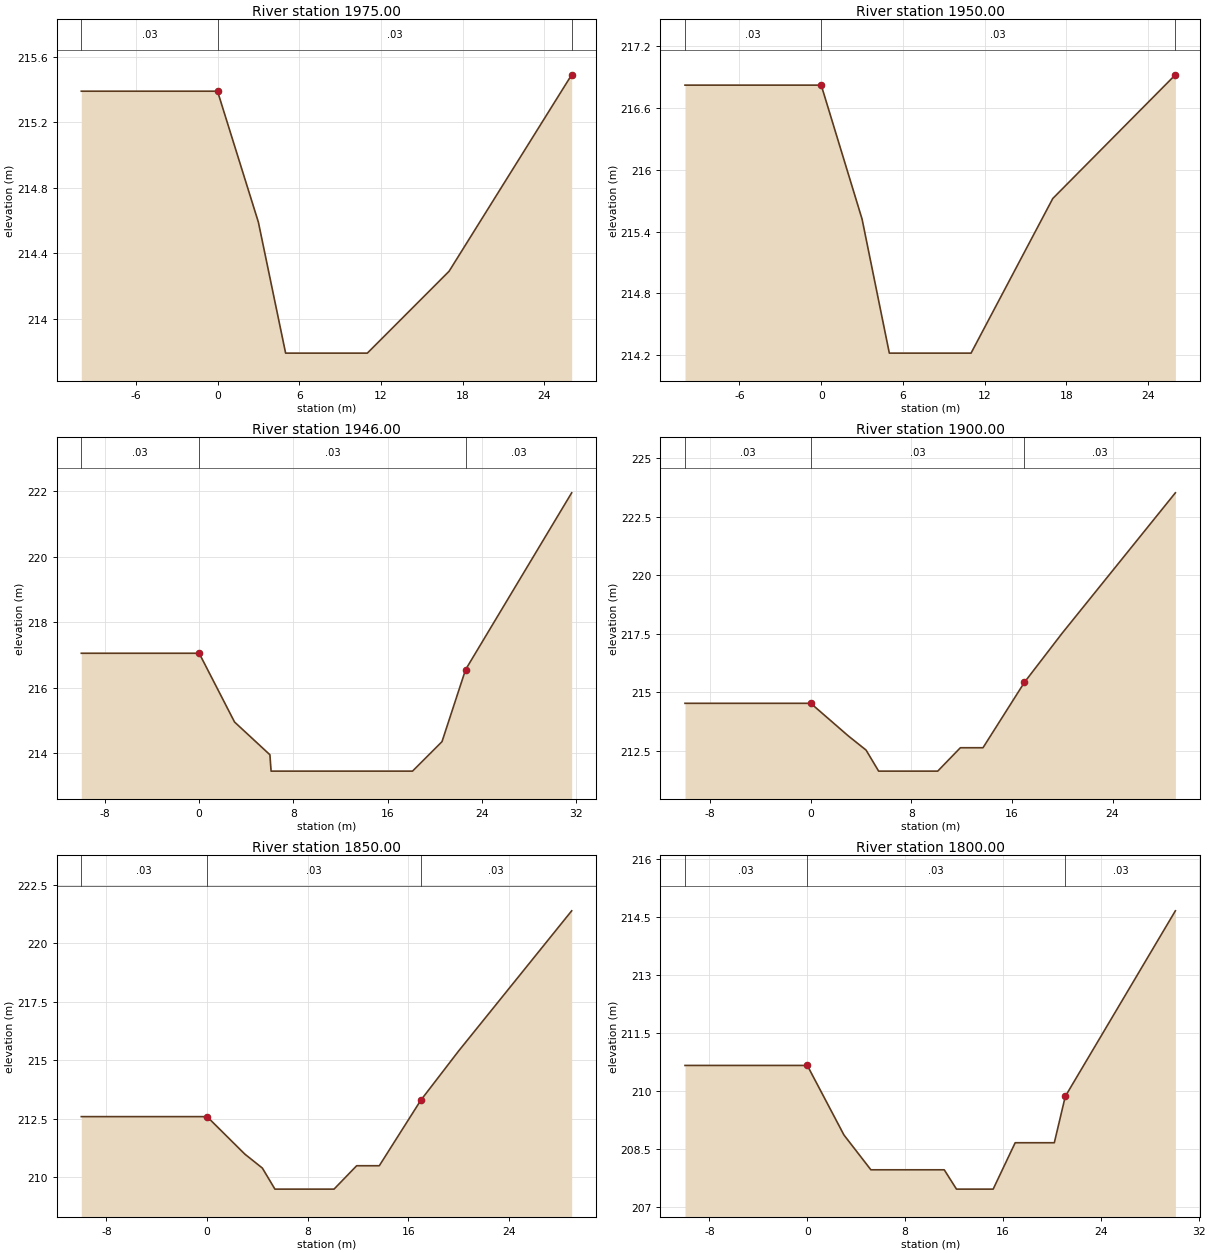
Type RM Length L Ch R = 1 ,1975.00 ,25,25,25
BEGIN DESCRIPTION:
39.025
END DESCRIPTION:
#Sta/Elev= 7
     -10  215.39       0  215.39       3  214.59       5  213.79      11  213.79
      17  214.29      26  215.49
#Mann= 3 , 0 , 0
     -10     .03       0       0     .03       0      26     .03       0
#XS Ineff= 2 , 0
               0  215.39      26          215.49
Permanent Ineff=
       F       F
Bank Sta=0,26
XS Rating Curve= 0
Exp/Cntr=.3,.1

Type RM Length L Ch R = 1 ,1950.00 ,4,4,4
BEGIN DESCRIPTION:
39
END DESCRIPTION:
#Sta/Elev= 7
     -10  216.82       0  216.82       3  215.52       5  214.22      11  214.22
      17  215.72      26  216.92
#Mann= 3 , 0 , 0
     -10     .03       0       0     .03       0      26     .03       0
#XS Ineff= 2 , 0
               0  216.82      26          216.92
Permanent Ineff=
       F       F
Bank Sta=0,26
XS Rating Curve= 0
Exp/Cntr=.3,.1

Type RM Length L Ch R = 1 ,1946.00 ,46,46,46
BEGIN DESCRIPTION:
38.046
END DESCRIPTION:
#Sta/Elev= 9
     -10  217.05       0  217.05       3  214.95       6  213.95     6.1  213.45
    18.1  213.45    20.6  214.35    22.6  216.55    31.6  221.95
#Mann= 3 , 0 , 0
     -10     .03       0       0     .03       0    22.6     .03       0
#XS Ineff= 2 , 0
               0  217.05    22.6          216.55
Permanent Ineff=
       F       F
Bank Sta=0,22.6
XS Rating Curve= 0
Exp/Cntr=.3,.1

Type RM Length L Ch R = 1 ,1900.00 ,50,50,50
BEGIN DESCRIPTION:
38
END DESCRIPTION:
#Sta/Elev= 11
     -10  214.53       0  214.53       3  213.13     4.4  212.53     5.4  211.63
    10.1  211.63    11.9  212.63    13.7  212.63      17  215.43      20  217.53
      29  223.53
#Mann= 3 , 0 , 0
     -10     .03       0       0     .03       0      17     .03       0
#XS Ineff= 2 , 0
               0  214.53      17          215.43
Permanent Ineff=
       F       F
Bank Sta=0,17
XS Rating Curve= 0
Exp/Cntr=.3,.1

Type RM Length L Ch R = 1 ,1850.00 ,50,50,50
BEGIN DESCRIPTION:
37
END DESCRIPTION:
#Sta/Elev= 11
     -10  212.59       0  212.59       3  210.99     4.4  210.39     5.4  209.49
    10.1  209.49    11.9  210.49    13.7  210.49      17  213.29      20  215.39
      29  221.39
#Mann= 3 , 0 , 0
     -10     .03       0       0     .03       0      17     .03       0
#XS Ineff= 2 , 0
               0  212.59      17          213.29
Permanent Ineff=
       F       F
Bank Sta=0,17
XS Rating Curve= 0
Exp/Cntr=.3,.1

Type RM Length L Ch R = 1 ,1800.00 ,14,14,14
BEGIN DESCRIPTION:
36
END DESCRIPTION:
#Sta/Elev= 11
     -10  210.65       0  210.65       3  208.85     5.2  207.95    11.2  207.95
    12.2  207.45    15.2  207.45      17  208.65    20.2  208.65    21.1  209.85
    30.1  214.65
#Mann= 3 , 0 , 0
     -10     .03       0       0     .03       0    21.1     .03       0
#XS Ineff= 2 , 0
               0  210.65    21.1          209.85
Permanent Ineff=
       F       F
Bank Sta=0,21.1
XS Rating Curve= 0
Exp/Cntr=.3,.1

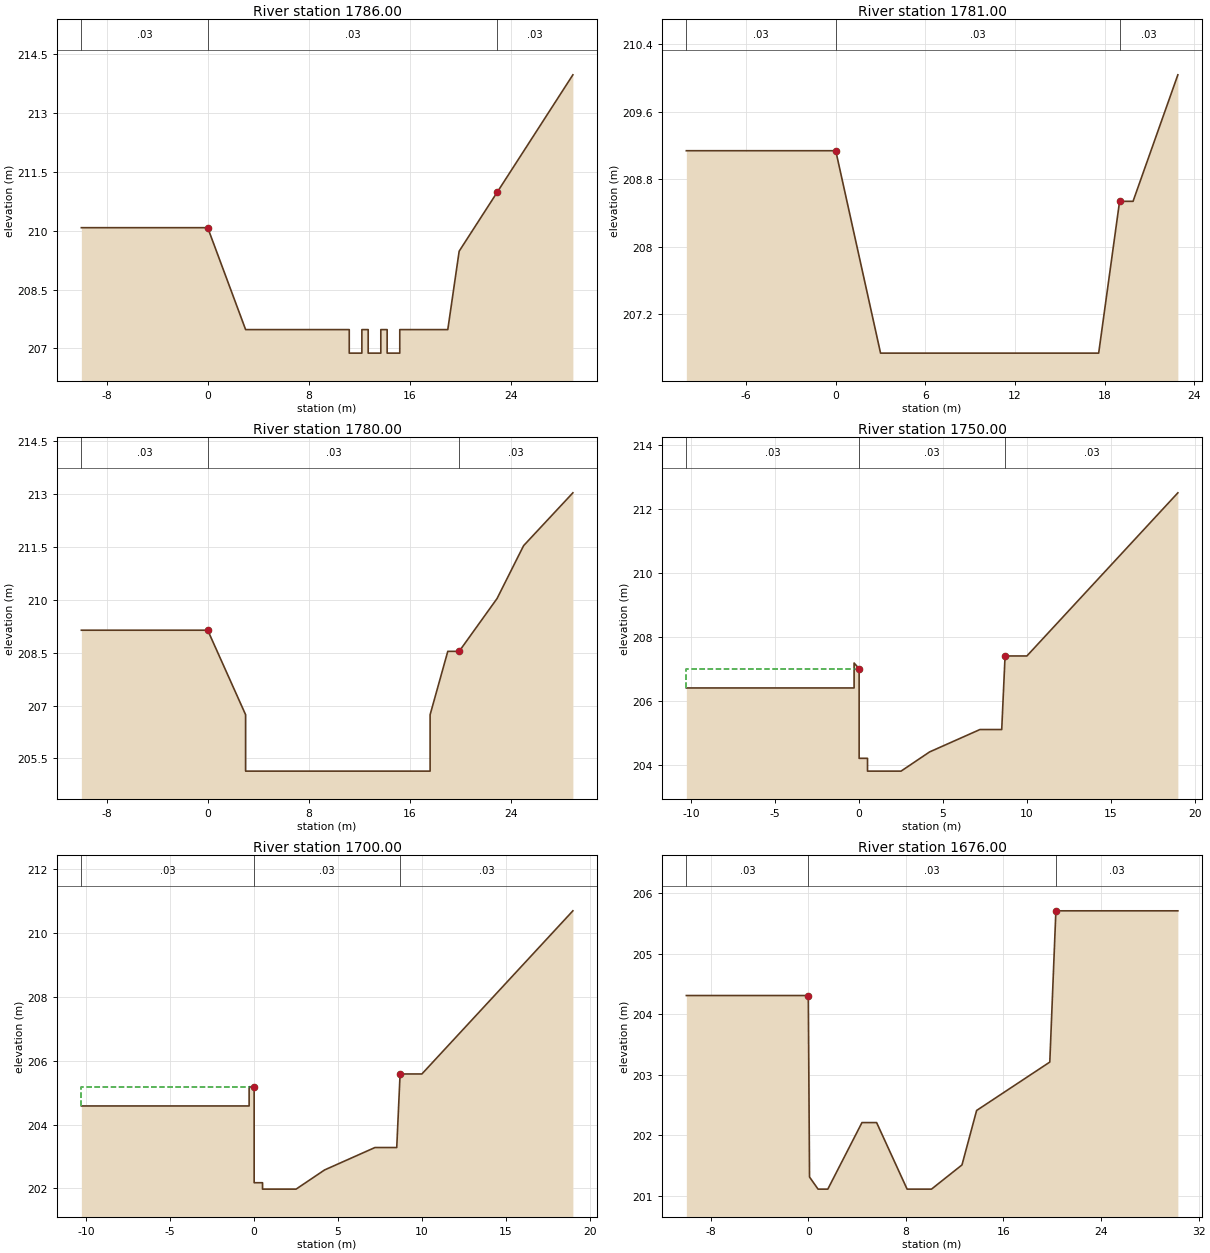
Type RM Length L Ch R = 1 ,1786.00 ,5,5,5
BEGIN DESCRIPTION:
35.036
END DESCRIPTION:
#Sta/Elev= 20
     -10  210.08       0  210.08       3  207.48    11.2  207.48    11.2  206.88
    12.2  206.88    12.2  207.48    12.7  207.48    12.7  206.88    13.7  206.88
    13.7  207.48    14.2  207.48    14.2  206.88    15.2  206.88    15.2  207.48
      19  207.48    19.9  209.48    22.9  210.98    25.9  212.48    28.9  213.98
#Mann= 3 , 0 , 0
     -10     .03       0       0     .03       0    22.9     .03       0
#XS Ineff= 2 , 0
               0  210.08    22.9          210.98
Permanent Ineff=
       F       F
Bank Sta=0,22.9
XS Rating Curve= 0
Exp/Cntr=.3,.1

Type RM Length L Ch R = 1 ,1781.00 ,1,1,1
BEGIN DESCRIPTION:
35.031
END DESCRIPTION:
#Sta/Elev= 7
     -10  209.14       0  209.14       3  206.74    17.6  206.74      19  208.54
    19.9  208.54    22.9  210.04
#Mann= 3 , 0 , 0
     -10     .03       0       0     .03       0      19     .03       0
#XS Ineff= 2 , 0
               0  209.14      19          208.54
Permanent Ineff=
       F       F
Bank Sta=0,19
XS Rating Curve= 0
Exp/Cntr=.3,.1

Type RM Length L Ch R = 1 ,1780.00 ,30,30,30
BEGIN DESCRIPTION:
35.03
END DESCRIPTION:
#Sta/Elev= 11
     -10  209.14       0  209.14       3  206.74       3  205.14    17.6  205.14
    17.6  206.74      19  208.54    19.9  208.54    22.9  210.04      25  211.54
    28.9  213.04
#Mann= 3 , 0 , 0
     -10     .03       0       0     .03       0    19.9     .03       0
#XS Ineff= 2 , 0
       0       0  209.14    19.9       0  208.54
Permanent Ineff=
       F       F
Bank Sta=0,19.9
XS Rating Curve= 0
Exp/Cntr=.3,.1

Type RM Length L Ch R = 1 ,1750.00 ,50,50,50
BEGIN DESCRIPTION:
35
END DESCRIPTION:
#Sta/Elev= 14
   -10.3  206.42     -.3  206.42     -.3   207.2       0  207.02       0  204.22
      .5  204.22      .5  203.82     2.5  203.82     4.2  204.42     7.2  205.12
     8.5  205.12     8.7  207.42      10  207.42      19  212.52
#Mann= 3 , 0 , 0
   -10.3     .03       0       0     .03       0     8.7     .03       0
#XS Ineff= 2 , 0
               0  207.02     8.7          207.42
Permanent Ineff=
       F       F
Bank Sta=0,8.7
XS Rating Curve= 0
Exp/Cntr=.3,.1

Type RM Length L Ch R = 1 ,1700.00 ,24,24,24
BEGIN DESCRIPTION:
34
END DESCRIPTION:
#Sta/Elev= 14
   -10.3  204.58     -.3  204.58     -.3  205.18       0  205.18       0  202.18
      .5  202.18      .5  201.98     2.5  201.98     4.2  202.58     7.2  203.28
     8.5  203.28     8.7  205.58      10  205.58      19  210.68
#Mann= 3 , 0 , 0
   -10.3     .03       0       0     .03       0     8.7     .03       0
#XS Ineff= 2 , 0
               0  205.18     8.7          205.58
Permanent Ineff=
       F       F
Bank Sta=0,8.7
XS Rating Curve= 0
Exp/Cntr=.3,.1

Type RM Length L Ch R = 1 ,1676.00 ,26,26,26
BEGIN DESCRIPTION:
33.026
END DESCRIPTION:
#Sta/Elev= 15
     -10  204.31       0  204.31      .1  201.31      .8  201.11     1.6  201.11
     4.4  202.21     5.6  202.21     8.1  201.11    10.1  201.11    12.6  201.51
    13.8  202.41    16.8  202.81    19.8  203.21    20.3  205.71    30.3  205.71
#Mann= 3 , 0 , 0
     -10     .03       0       0     .03       0    20.3     .03       0
#XS Ineff= 2 , 0
               0  204.31    20.3          205.71
Permanent Ineff=
       F       F
Bank Sta=0,20.3
XS Rating Curve= 0
Exp/Cntr=.3,.1

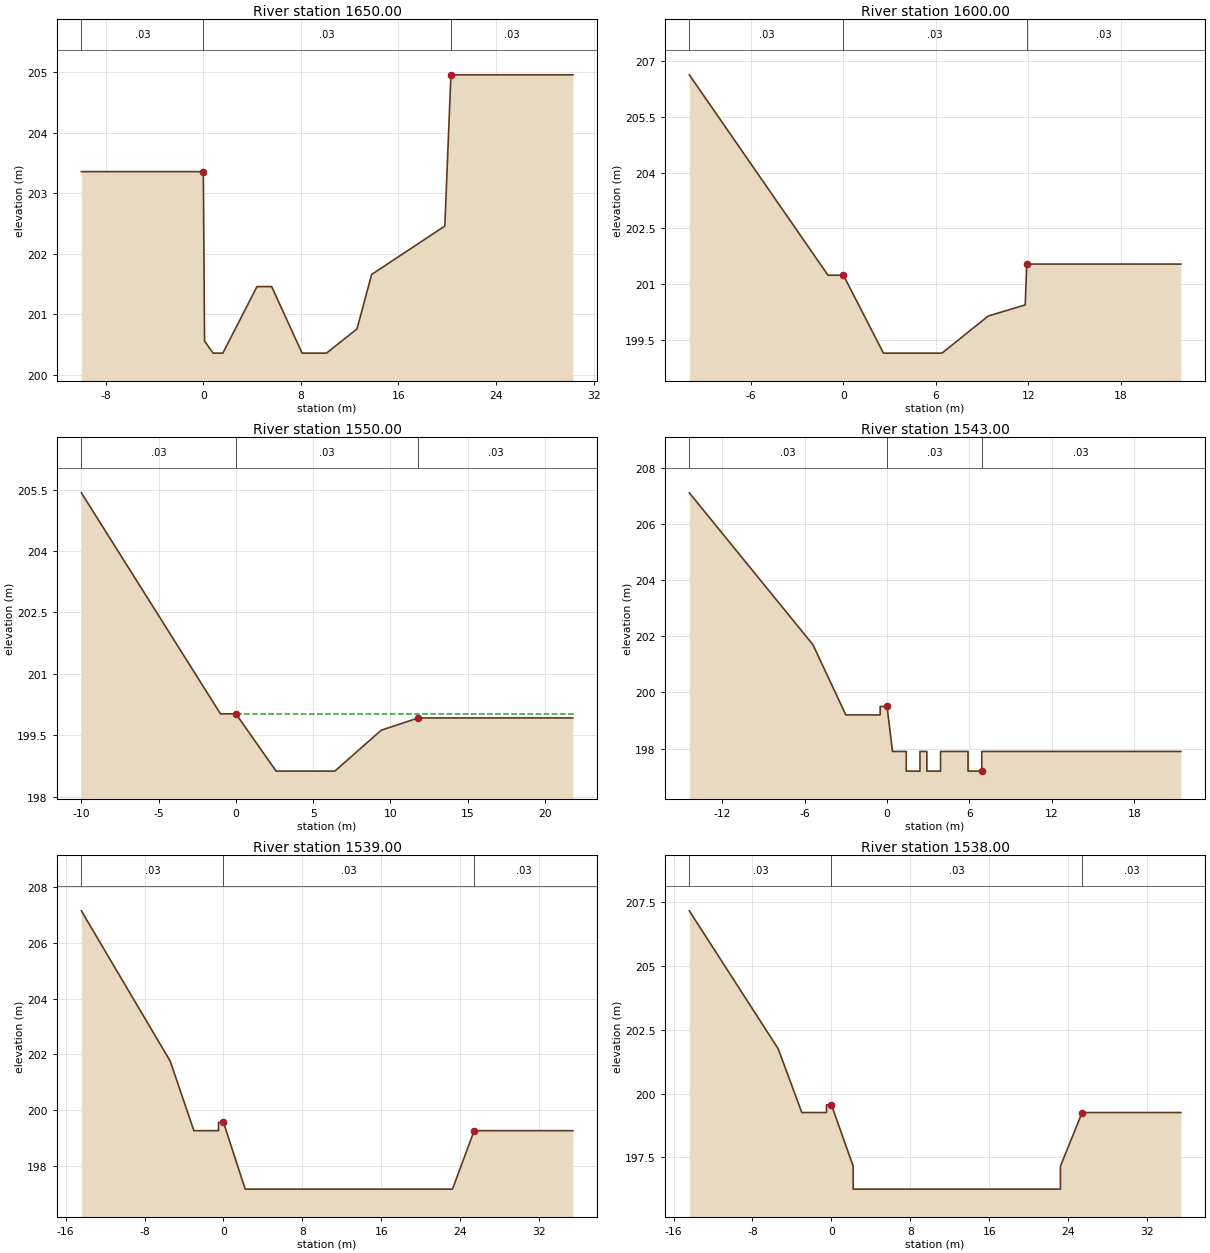
Type RM Length L Ch R = 1 ,1650.00 ,50,50,50
BEGIN DESCRIPTION:
33
END DESCRIPTION:
#Sta/Elev= 15
     -10  203.36       0  203.36      .1  200.56      .8  200.36     1.6  200.36
     4.4  201.46     5.6  201.46     8.1  200.36    10.1  200.36    12.6  200.76
    13.8  201.66    16.8  202.06    19.8  202.46    20.3  204.96    30.3  204.96
#Mann= 3 , 0 , 0
     -10     .03       0       0     .03       0    20.3     .03       0
#XS Ineff= 2 , 0
               0  203.36    20.3          204.96
Permanent Ineff=
       F       F
Bank Sta=0,20.3
XS Rating Curve= 0
Exp/Cntr=.3,.1

Type RM Length L Ch R = 1 ,1600.00 ,50,50,50
BEGIN DESCRIPTION:
32
END DESCRIPTION:
#Sta/Elev= 9
     -10  206.64      -1  201.24       0  201.24     2.6  199.14     6.4  199.14
     9.4  200.14    11.8  200.44    11.9  201.54    21.9  201.54
#Mann= 3 , 0 , 0
     -10     .03       0       0     .03       0    11.9     .03       0
#XS Ineff= 2 , 0
       0       0  201.24    11.9       0  201.54
Permanent Ineff=
       F       F
Bank Sta=0,11.9
XS Rating Curve= 0
Exp/Cntr=.3,.1

Type RM Length L Ch R = 1 ,1550.00 ,7,7,7
BEGIN DESCRIPTION:
31
END DESCRIPTION:
#Sta/Elev= 8
     -10  205.42      -1  200.02       0  200.02     2.6  198.62     6.4  198.62
     9.4  199.62    11.8  199.92    21.8  199.92
#Mann= 3 , 0 , 0
     -10     .03       0       0     .03       0    11.8     .03       0
#XS Ineff= 2 , 0
       0       0  200.02    11.8       0  199.92
Permanent Ineff=
       F       F
Bank Sta=0,11.8
XS Rating Curve= 0
Exp/Cntr=.3,.1

Type RM Length L Ch R = 1 ,1543.00 ,4,4,4
BEGIN DESCRIPTION:
30.043
END DESCRIPTION:
#Sta/Elev= 20
   -14.4   207.1    -5.4   201.7      -3   199.2     -.5   199.2     -.5   199.5
       0   199.5      .4   197.9     1.4   197.9     1.4   197.2     2.4   197.2
     2.4   197.9     2.9   197.9     2.9   197.2     3.9   197.2     3.9   197.9
     5.9   197.9     5.9   197.2     6.9   197.2     6.9   197.9    21.4   197.9
#Mann= 3 , 0 , 0
   -14.4     .03       0       0     .03       0     6.9     .03       0
Bank Sta=0,6.9
XS Rating Curve= 0
Exp/Cntr=.3,.1

Type RM Length L Ch R = 1 ,1539.00 ,1,1,1
BEGIN DESCRIPTION:
30.039
END DESCRIPTION:
#Sta/Elev= 12
   -14.4  207.16   -11.4  205.36    -8.4  203.56    -5.4  201.76      -3  199.26
     -.5  199.26     -.5  199.56       0  199.56     2.2  197.16    23.2  197.16
    25.4  199.26    35.4  199.26
#Mann= 3 , 0 , 0
   -14.4     .03       0       0     .03       0    25.4     .03       0
#XS Ineff= 2 , 0
               0  199.56    25.4          199.26
Permanent Ineff=
       F       F
Bank Sta=0,25.4
XS Rating Curve= 0
Exp/Cntr=.3,.1

Type RM Length L Ch R = 1 ,1538.00 ,38,38,38
BEGIN DESCRIPTION:
30.038
END DESCRIPTION:
#Sta/Elev= 14
   -14.4  207.16   -11.4  205.36    -8.4  203.56    -5.4  201.76      -3  199.26
     -.5  199.26     -.5  199.56       0  199.56     2.2  197.16     2.2  196.26
    23.2  196.26    23.2  197.16    25.4  199.26    35.4  199.26
#Mann= 3 , 0 , 0
   -14.4     .03       0       0     .03       0    25.4     .03       0
#XS Ineff= 2 , 0
               0  199.56    25.4          199.26
Permanent Ineff=
       F       F
Bank Sta=0,25.4
XS Rating Curve= 0
Exp/Cntr=.3,.1

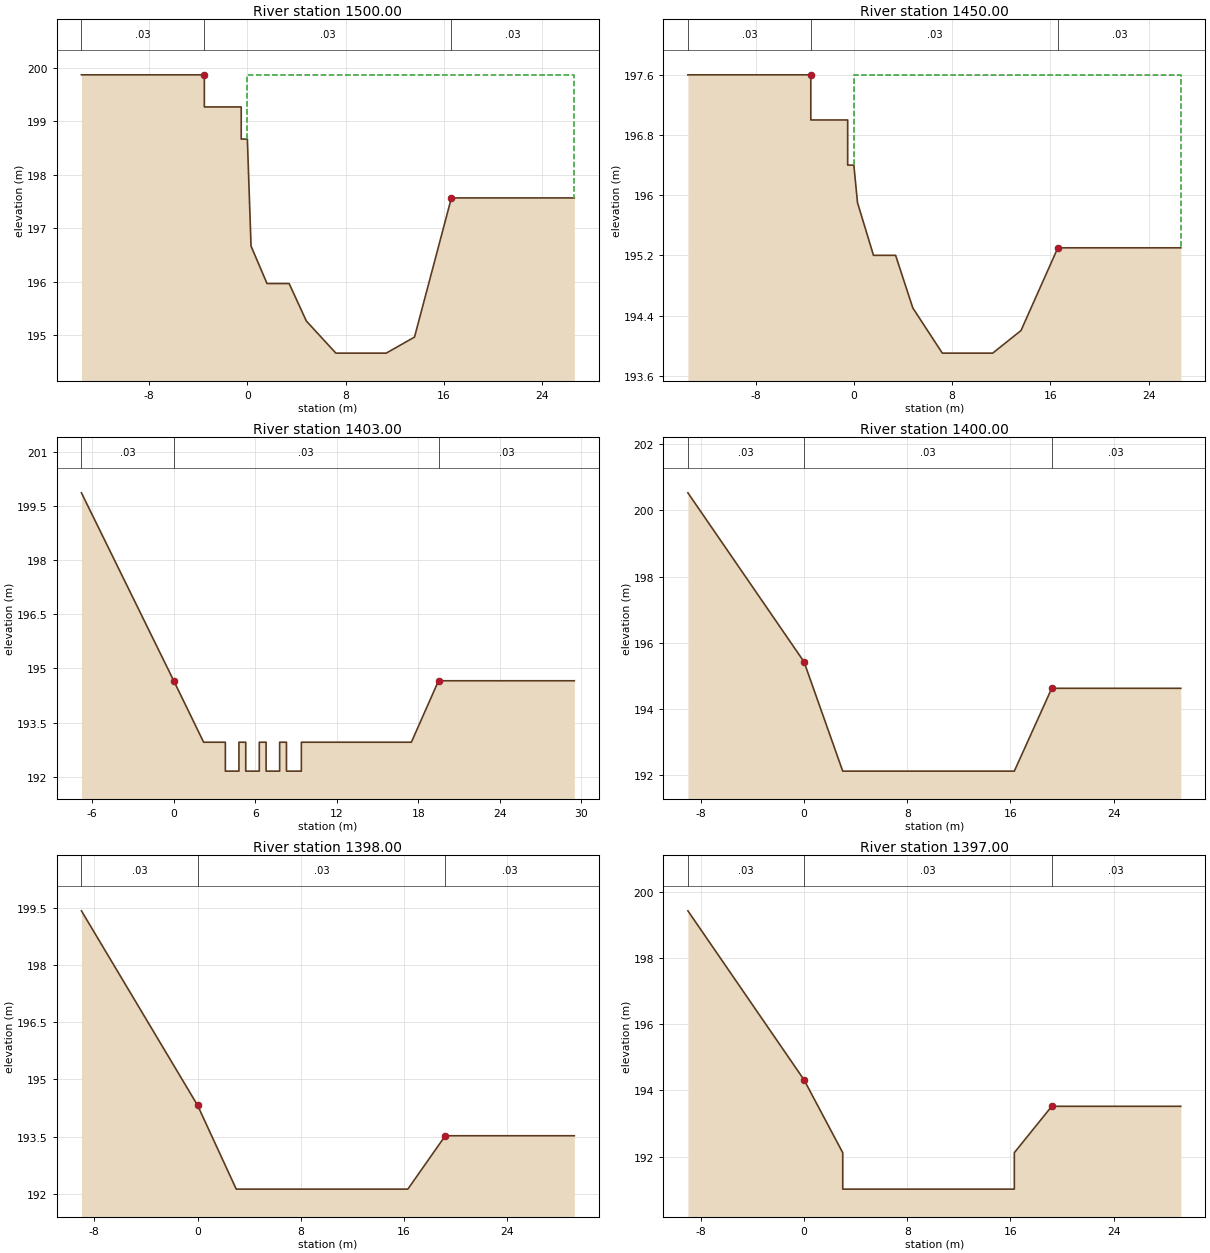
Type RM Length L Ch R = 1 ,1500.00 ,50,50,50
BEGIN DESCRIPTION:
30
END DESCRIPTION:
#Sta/Elev= 15
   -13.5  199.87    -3.5  199.87    -3.5  199.27     -.5  199.27     -.5  198.67
       0  198.67      .3  196.67     1.6  195.97     3.4  195.97     4.8  195.27
     7.2  194.67    11.3  194.67    13.6  194.97    16.6  197.57    26.6  197.57
#Mann= 3 , 0 , 0
   -13.5     .03       0    -3.5     .03       0    16.6     .03       0
#XS Ineff= 2 , 0
       0    -3.5  199.87    16.6       0  197.57
Permanent Ineff=
       F       F
Bank Sta=-3.5,16.6
XS Rating Curve= 0
Exp/Cntr=.3,.1

Type RM Length L Ch R = 1 ,1450.00 ,47,47,47
BEGIN DESCRIPTION:
29
END DESCRIPTION:
#Sta/Elev= 15
   -13.5   197.6    -3.5   197.6    -3.5     197     -.5     197     -.5   196.4
       0   196.4      .3   195.9     1.6   195.2     3.4   195.2     4.8   194.5
     7.2   193.9    11.3   193.9    13.6   194.2    16.6   195.3    26.6   195.3
#Mann= 3 , 0 , 0
   -13.5     .03       0    -3.5     .03       0    16.6     .03       0
#XS Ineff= 2 , 0
       0    -3.5   197.6    16.6       0   195.3
Permanent Ineff=
       F       F
Bank Sta=-3.5,16.6
XS Rating Curve= 0
Exp/Cntr=.3,.1

Type RM Length L Ch R = 1 ,1403.00 ,3,3,3
BEGIN DESCRIPTION:
28.003
END DESCRIPTION:
#Sta/Elev= 22
    -6.8  199.86       0  194.66     2.2  192.96     3.8  192.96     3.8  192.16
     4.8  192.16     4.8  192.96     5.3  192.96     5.3  192.16     6.3  192.16
     6.3  192.96     6.8  192.96     6.8  192.16     7.8  192.16     7.8  192.96
     8.3  192.96     8.3  192.16     9.4  192.16     9.4  192.96    17.5  192.96
    19.5  194.66    29.5  194.66
#Mann= 3 , 0 , 0
    -6.8     .03       0       0     .03       0    19.5     .03       0
#XS Ineff= 2 , 0
               0  194.66    19.5          194.66
Permanent Ineff=
       F       F
Bank Sta=0,19.5
XS Rating Curve= 0
Exp/Cntr=.3,.1

Type RM Length L Ch R = 1 ,1400.00 ,2,2,2
BEGIN DESCRIPTION:
28
END DESCRIPTION:
#Sta/Elev= 6
      -9  200.53       0  195.43       3  192.13    16.3  192.13    19.2  194.63
    29.2  194.63
#Mann= 3 , 0 , 0
      -9     .03       0       0     .03       0    19.2     .03       0
#XS Ineff= 2 , 0
               0  195.43    19.2          194.63
Permanent Ineff=
       F       F
Bank Sta=0,19.2
XS Rating Curve= 0
Exp/Cntr=.3,.1

Type RM Length L Ch R = 1 ,1398.00 ,1,1,1
BEGIN DESCRIPTION:
27.048
END DESCRIPTION:
#Sta/Elev= 8
      -9  199.42      -6  197.72      -3  196.02       0  194.32       3  192.12
    16.3  192.12    19.2  193.52    29.2  193.52
#Mann= 3 , 0 , 0
      -9     .03       0       0     .03       0    19.2     .03       0
#XS Ineff= 2 , 0
               0  194.32    19.2          193.52
Permanent Ineff=
       F       F
Bank Sta=0,19.2
XS Rating Curve= 0
Exp/Cntr=.3,.1

Type RM Length L Ch R = 1 ,1397.00 ,47,47,47
BEGIN DESCRIPTION:
27.047
END DESCRIPTION:
#Sta/Elev= 8
      -9  199.42       0  194.32       3  192.12       3  191.02    16.3  191.02
    16.3  192.12    19.2  193.52    29.2  193.52
#Mann= 3 , 0 , 0
      -9     .03       0       0     .03       0    19.2     .03       0
#XS Ineff= 2 , 0
               0  194.32    19.2          193.52
Permanent Ineff=
       F       F
Bank Sta=0,19.2
XS Rating Curve= 0
Exp/Cntr=.3,.1

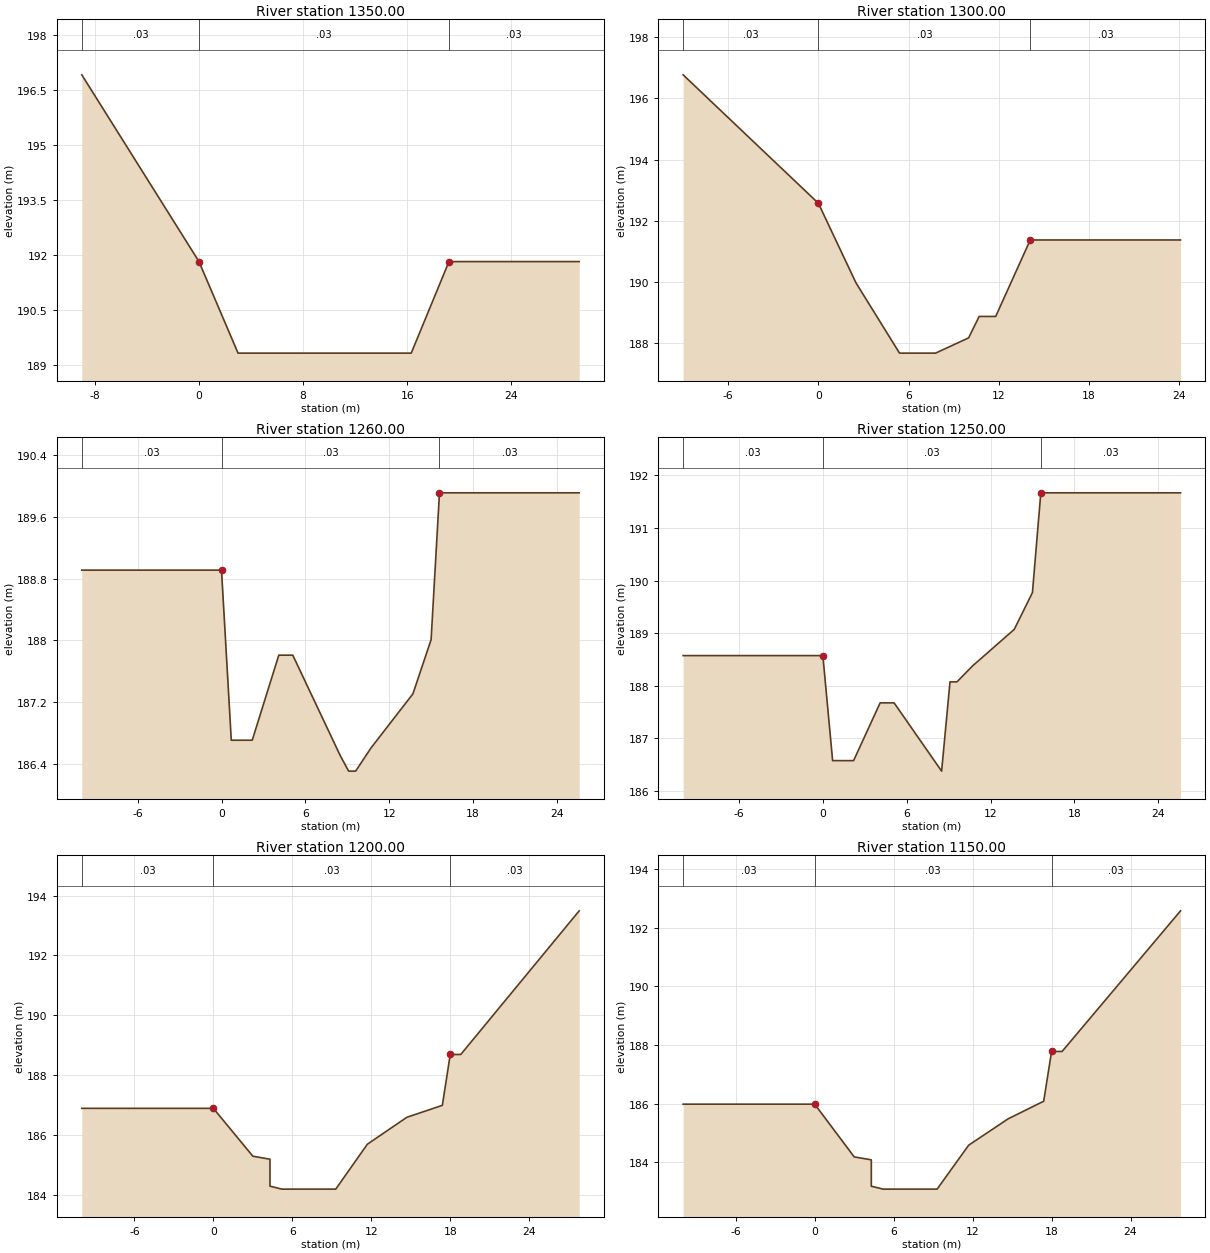
Type RM Length L Ch R = 1 ,1350.00 ,50,50,50
BEGIN DESCRIPTION:
27
END DESCRIPTION:
#Sta/Elev= 6
      -9  196.92       0  191.82       3  189.32    16.3  189.32    19.2  191.82
    29.2  191.82
#Mann= 3 , 0 , 0
      -9     .03       0       0     .03       0    19.2     .03       0
#XS Ineff= 2 , 0
               0  191.82    19.2          191.82
Permanent Ineff=
       F       F
Bank Sta=0,19.2
XS Rating Curve= 0
Exp/Cntr=.3,.1

Type RM Length L Ch R = 1 ,1300.00 ,40,40,40
BEGIN DESCRIPTION:
26
END DESCRIPTION:
#Sta/Elev= 10
      -9  196.77       0  192.57     2.5  189.97     5.4  187.67     7.8  187.67
      10  188.17    10.7  188.87    11.8  188.87    14.1  191.37    24.1  191.37
#Mann= 3 , 0 , 0
      -9     .03       0       0     .03       0    14.1     .03       0
#XS Ineff= 2 , 0
               0  192.57    14.1          191.37
Permanent Ineff=
       F       F
Bank Sta=0,14.1
XS Rating Curve= 0
Exp/Cntr=.3,.1

Type RM Length L Ch R = 1 ,1260.00 ,10,10,10
BEGIN DESCRIPTION:
25.01
END DESCRIPTION:
#Sta/Elev= 14
     -10  188.91       0  188.91      .7  186.71     2.2  186.71     4.1  187.81
     5.1  187.81     8.5  186.51     9.1  186.31     9.6  186.31    10.7  186.61
    13.7  187.31      15  188.01    15.6  189.91    25.6  189.91
#Mann= 3 , 0 , 0
     -10     .03       0       0     .03       0    15.6     .03       0
#XS Ineff= 2 , 0
       0       0  188.91    15.6       0  189.91
Permanent Ineff=
       F       F
Bank Sta=0,15.6
XS Rating Curve= 0
Exp/Cntr=.3,.1

Type RM Length L Ch R = 1 ,1250.00 ,50,50,50
BEGIN DESCRIPTION:
25
END DESCRIPTION:
#Sta/Elev= 14
     -10  188.57       0  188.57      .7  186.57     2.2  186.57     4.1  187.67
     5.1  187.67     8.5  186.37     9.1  188.07     9.6  188.07    10.7  188.37
    13.7  189.07      15  189.77    15.6  191.67    25.6  191.67
#Mann= 3 , 0 , 0
     -10     .03       0       0     .03       0    15.6     .03       0
#XS Ineff= 2 , 0
       0       0  188.57    15.6       0  191.67
Permanent Ineff=
       F       F
Bank Sta=0,15.6
XS Rating Curve= 0
Exp/Cntr=.3,.1

Type RM Length L Ch R = 1 ,1200.00 ,50,50,50
BEGIN DESCRIPTION:
24
END DESCRIPTION:
#Sta/Elev= 13
     -10  186.89       0  186.89       3  185.29     4.3  185.19     4.3  184.29
     5.2  184.19     9.3  184.19    11.7  185.69    14.7  186.59    17.4  186.99
      18  188.69    18.8  188.69    27.8  193.49
#Mann= 3 , 0 , 0
     -10     .03       0       0     .03       0      18     .03       0
#XS Ineff= 2 , 0
       0       0  186.89      18       0  188.69
Permanent Ineff=
       F       F
Bank Sta=0,18
XS Rating Curve= 0
Exp/Cntr=.3,.1

Type RM Length L Ch R = 1 ,1150.00 ,50,50,50
BEGIN DESCRIPTION:
23
END DESCRIPTION:
#Sta/Elev= 13
     -10  185.98       0  185.98       3  184.18     4.3  184.08     4.3  183.18
     5.2  183.08     9.3  183.08    11.7  184.58    14.7  185.48    17.4  186.08
      18  187.78    18.8  187.78    27.8  192.58
#Mann= 3 , 0 , 0
     -10     .03       0       0     .03       0      18     .03       0
#XS Ineff= 2 , 0
               0  185.98      18          187.78
Permanent Ineff=
       F       F
Bank Sta=0,18
XS Rating Curve= 0
Exp/Cntr=.3,.1

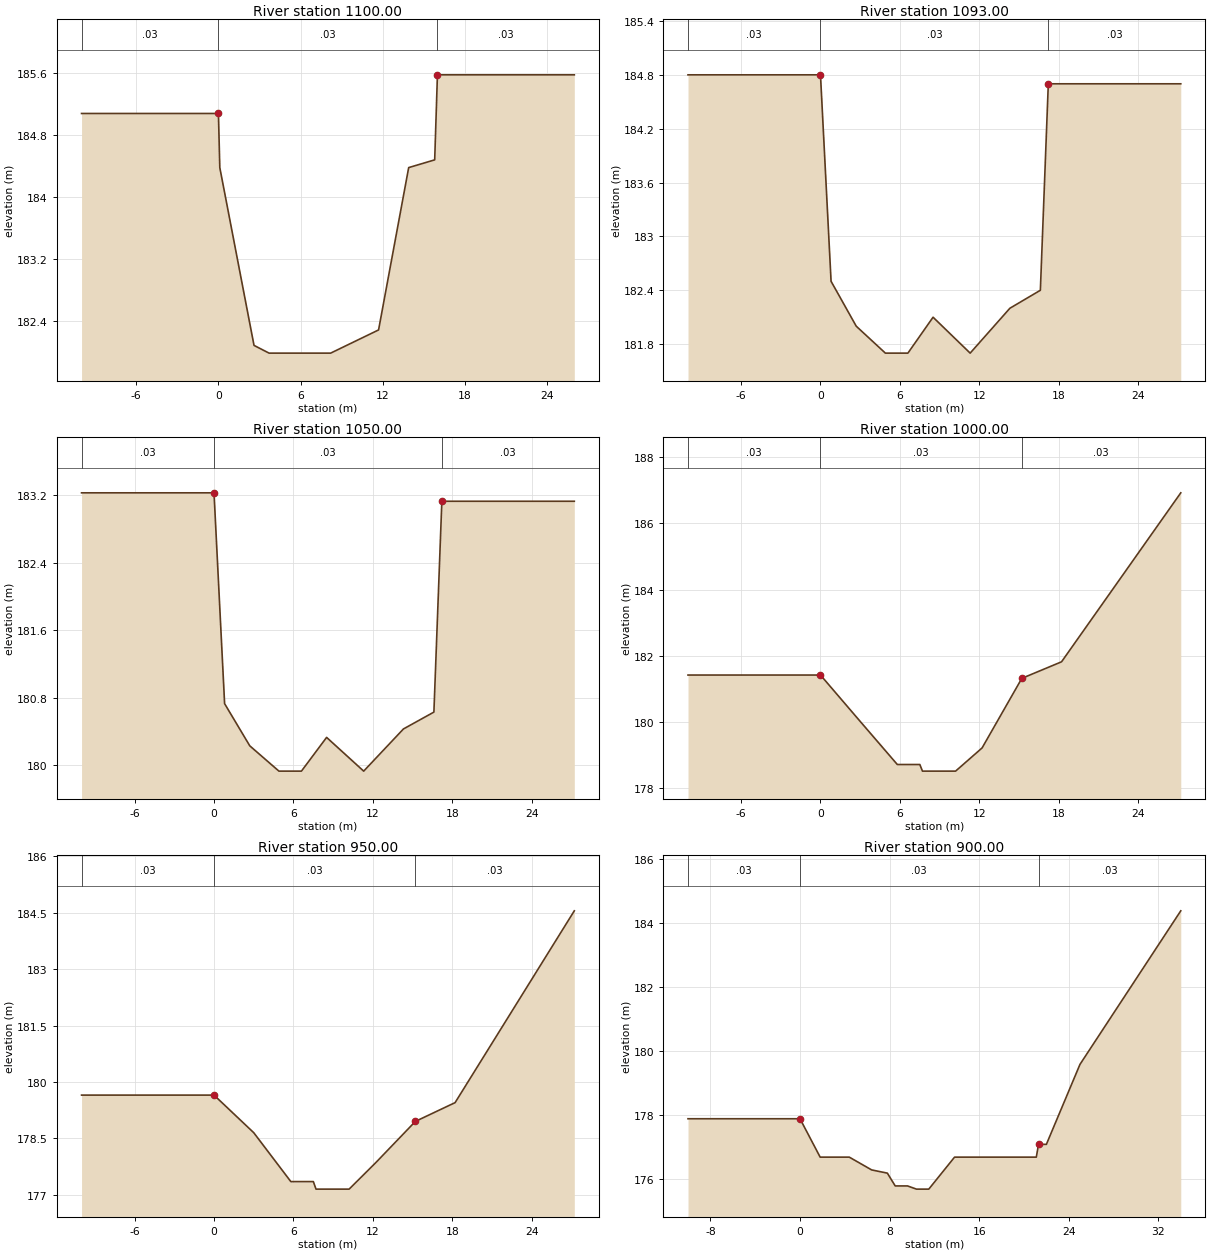
Type RM Length L Ch R = 1 ,1100.00 ,7,7,7
BEGIN DESCRIPTION:
22
END DESCRIPTION:
#Sta/Elev= 11
     -10  185.08       0  185.08      .1  184.38     2.6  182.08     3.7  181.98
     8.2  181.98    11.7  182.28    13.9  184.38    15.8  184.48      16  185.58
      26  185.58
#Mann= 3 , 0 , 0
     -10     .03       0       0     .03       0      16     .03       0
#XS Ineff= 2 , 0
               0  185.08      16          185.58
Permanent Ineff=
       F       F
Bank Sta=0,16
XS Rating Curve= 0
Exp/Cntr=.3,.1

Type RM Length L Ch R = 1 ,1093.00 ,43,43,43
BEGIN DESCRIPTION:
21.043
END DESCRIPTION:
#Sta/Elev= 12
     -10   184.8       0   184.8      .8   182.5     2.7     182     4.9   181.7
     6.6   181.7     8.5   182.1    11.3   181.7    14.3   182.2    16.6   182.4
    17.2   184.7    27.2   184.7
#Mann= 3 , 0 , 0
     -10     .03       0       0     .03       0    17.2     .03       0
#XS Ineff= 2 , 0
               0   184.8    17.2           184.7
Permanent Ineff=
       F       F
Bank Sta=0,17.2
XS Rating Curve= 0
Exp/Cntr=.3,.1

Type RM Length L Ch R = 1 ,1050.00 ,50,50,50
BEGIN DESCRIPTION:
21
END DESCRIPTION:
#Sta/Elev= 12
     -10  183.23       0  183.23      .8  180.73     2.7  180.23     4.9  179.93
     6.6  179.93     8.5  180.33    11.3  179.93    14.3  180.43    16.6  180.63
    17.2  183.13    27.2  183.13
#Mann= 3 , 0 , 0
     -10     .03       0       0     .03       0    17.2     .03       0
#XS Ineff= 2 , 0
               0  183.23    17.2          183.13
Permanent Ineff=
       F       F
Bank Sta=0,17.2
XS Rating Curve= 0
Exp/Cntr=.3,.1

Type RM Length L Ch R = 1 ,1000.00 ,50,50,50
BEGIN DESCRIPTION:
20
END DESCRIPTION:
#Sta/Elev= 11
     -10  181.42       0  181.42       3  180.02     5.8  178.72     7.5  178.72
     7.7  178.52    10.2  178.52    12.2  179.22    15.2  181.32    18.2  181.82
    27.2  186.92
#Mann= 3 , 0 , 0
     -10     .03       0       0     .03       0    15.2     .03       0
#XS Ineff= 2 , 0
               0  181.42    15.2          181.32
Permanent Ineff=
       F       F
Bank Sta=0,15.2
XS Rating Curve= 0
Exp/Cntr=.3,.1

Type RM Length L Ch R = 1 ,950.00  ,50,50,50
BEGIN DESCRIPTION:
19
END DESCRIPTION:
#Sta/Elev= 11
     -10  179.65       0  179.65       3  178.65     5.8  177.35     7.5  177.35
     7.7  177.15    10.2  177.15    12.2  177.85    15.2  178.95    18.2  179.45
    27.2  184.55
#Mann= 3 , 0 , 0
     -10     .03       0       0     .03       0    15.2     .03       0
#XS Ineff= 2 , 0
               0  179.65    15.2          178.95
Permanent Ineff=
       F       F
Bank Sta=0,15.2
XS Rating Curve= 0
Exp/Cntr=.3,.1

Type RM Length L Ch R = 1 ,900.00  ,50,50,50
BEGIN DESCRIPTION:
18
END DESCRIPTION:
#Sta/Elev= 16
     -10  177.88       0  177.88     1.8  176.68     4.4  176.68     6.4  176.28
     7.8  176.18     8.5  175.78     9.6  175.78    10.4  175.68    11.5  175.68
    13.8  176.68    21.1  176.68    21.3  177.08      22  177.08      25  179.58
      34  184.38
#Mann= 3 , 0 , 0
     -10     .03       0       0     .03       0    21.3     .03       0
#XS Ineff= 2 , 0
               0  177.88    21.3          177.08
Permanent Ineff=
       F       F
Bank Sta=0,21.3
XS Rating Curve= 0
Exp/Cntr=.3,.1

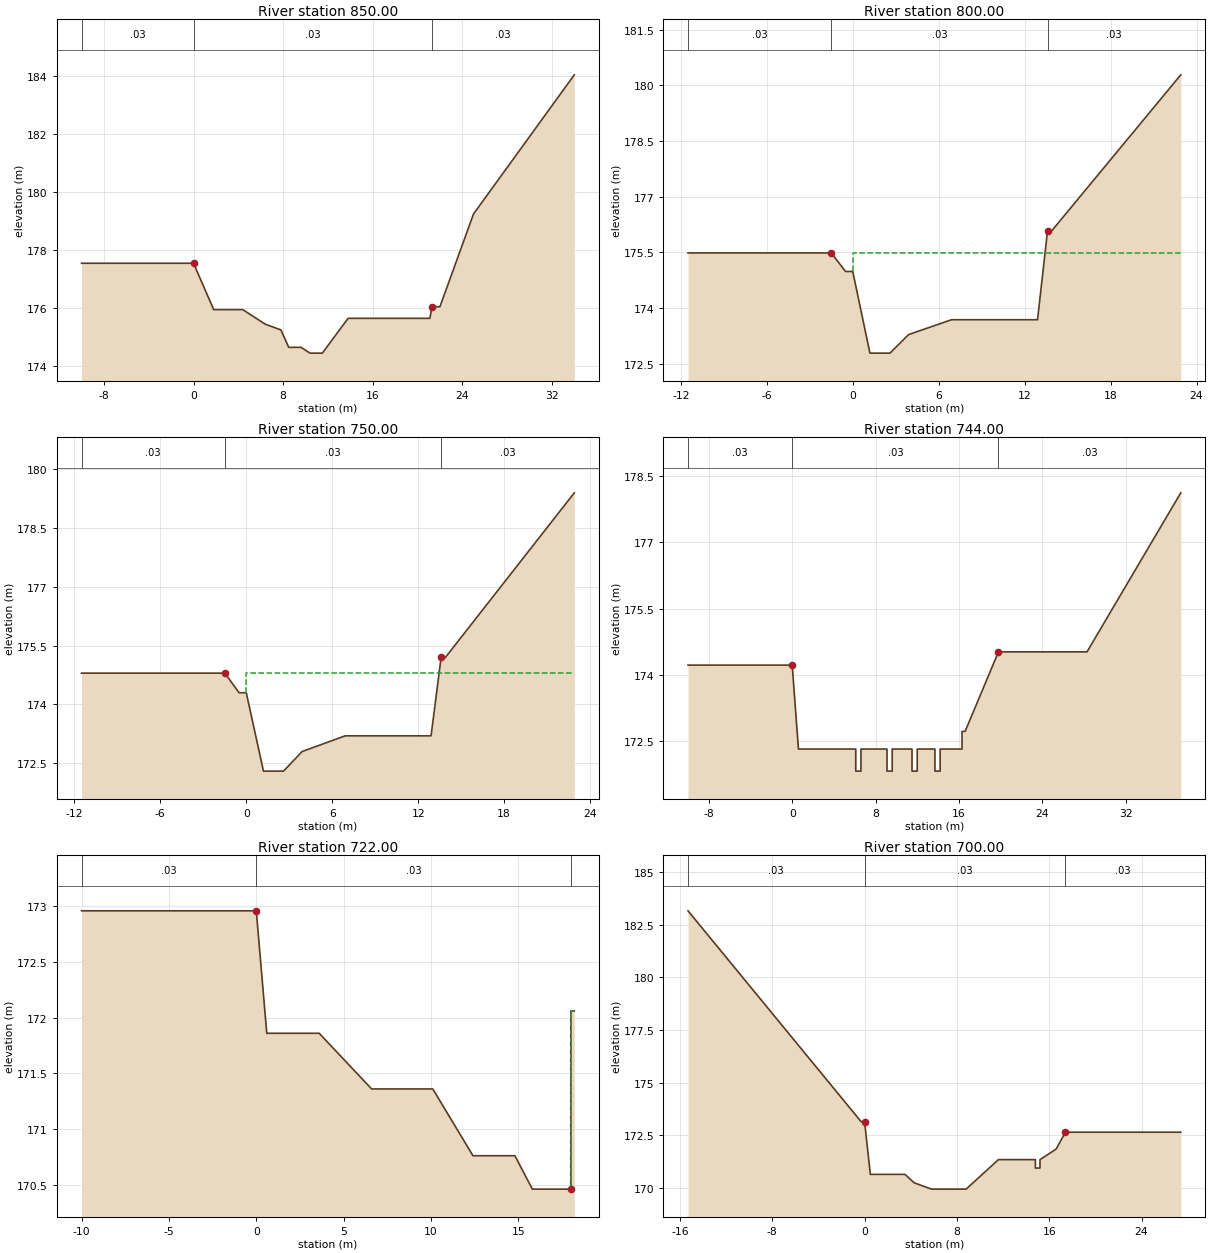
Type RM Length L Ch R = 1 ,850.00  ,50,50,50
BEGIN DESCRIPTION:
17
END DESCRIPTION:
#Sta/Elev= 16
     -10  177.54       0  177.54     1.8  175.94     4.4  175.94     6.4  175.44
     7.8  175.24     8.5  174.64     9.6  174.64    10.4  174.44    11.5  174.44
    13.8  175.64    21.1  175.64    21.3  176.04      22  176.04      25  179.24
      34  184.04
#Mann= 3 , 0 , 0
     -10     .03       0       0     .03       0    21.3     .03       0
#XS Ineff= 2 , 0
               0  177.54    21.3          176.04
Permanent Ineff=
       F       F
Bank Sta=0,21.3
XS Rating Curve= 0
Exp/Cntr=.3,.1

Type RM Length L Ch R = 1 ,800.00  ,50,50,50
BEGIN DESCRIPTION:
16
END DESCRIPTION:
#Sta/Elev= 12
   -11.5  175.48    -1.5  175.48     -.5  174.98       0  174.98     1.2  172.78
     2.6  172.78     3.9  173.28     6.9  173.68    12.9  173.68    13.6  176.08
    13.9  176.08    22.9  180.28
#Mann= 3 , 0 , 0
   -11.5     .03       0    -1.5     .03       0    13.6     .03       0
#XS Ineff= 2 , 0
       0    -1.5  175.48    13.6       0  176.08
Permanent Ineff=
       F       F
Bank Sta=-1.5,13.6
XS Rating Curve= 0
Exp/Cntr=.3,.1

Type RM Length L Ch R = 1 ,750.00  ,6,6,6
BEGIN DESCRIPTION:
15
END DESCRIPTION:
#Sta/Elev= 12
   -11.5   174.8    -1.5   174.8     -.5   174.3       0   174.3     1.2   172.3
     2.6   172.3     3.9   172.8     6.9   173.2    12.9   173.2    13.6   175.2
    13.9   175.2    22.9   179.4
#Mann= 3 , 0 , 0
   -11.5     .03       0    -1.5     .03       0    13.6     .03       0
#XS Ineff= 2 , 0
       0    -1.5   174.8    13.6       0   175.2
Permanent Ineff=
       F       F
Bank Sta=-1.5,13.6
XS Rating Curve= 0
Exp/Cntr=.3,.1

Type RM Length L Ch R = 1 ,744.00  ,22,22,22
BEGIN DESCRIPTION:
14.044
END DESCRIPTION:
#Sta/Elev= 25
     -10  174.22       0  174.22      .6  172.32     6.1  172.32     6.1  171.82
     6.6  171.82     6.6  172.32     9.1  172.32     9.1  171.82     9.6  171.82
     9.6  172.32    11.5  172.32    11.5  171.82      12  171.82      12  172.32
    13.7  172.32    13.7  171.82    14.2  171.82    14.2  172.32    16.3  172.32
    16.3  172.72    16.6  172.72    19.8  174.52    28.3  174.52    37.3  178.12
#Mann= 3 , 0 , 0
     -10     .03       0       0     .03       0    19.8     .03       0
#XS Ineff= 2 , 0
               0  174.22    19.8          174.52
Permanent Ineff=
       F       F
Bank Sta=0,19.8
XS Rating Curve= 0
Exp/Cntr=.3,.1

Type RM Length L Ch R = 1 ,722.00  ,22,22,22
BEGIN DESCRIPTION:
14.022
END DESCRIPTION:
#Sta/Elev= 12
     -10  172.96       0  172.96      .6  171.86     3.6  171.86     6.6  171.36
    10.1  171.36    12.4  170.76    14.8  170.76    15.8  170.46      18  170.46
      18  172.06    18.2  172.06
#Mann= 3 , 0 , 0
     -10     .03       0       0     .03       0      18     .03       0
#XS Ineff= 2 , 0
               0  172.96      18          172.06
Permanent Ineff=
       F       F
Bank Sta=0,18
XS Rating Curve= 0
Exp/Cntr=.3,.1

Type RM Length L Ch R = 1 ,700.00  ,50,50,50
BEGIN DESCRIPTION:
14
END DESCRIPTION:
#Sta/Elev= 18
   -15.3  183.15    -6.3  177.15    -3.3  175.15     -.3  173.15       0  173.15
      .5  170.65     3.5  170.65     4.3  170.25     5.8  169.95     8.8  169.95
    11.6  171.35    14.8  171.35    14.8  170.95    15.2  170.95    15.2  171.35
    16.6  171.85    17.4  172.65    27.4  172.65
#Mann= 3 , 0 , 0
   -15.3     .03       0       0     .03       0    17.4     .03       0
#XS Ineff= 2 , 0
               0  173.15    17.4          172.65
Permanent Ineff=
       F       F
Bank Sta=0,17.4
XS Rating Curve= 0
Exp/Cntr=.3,.1