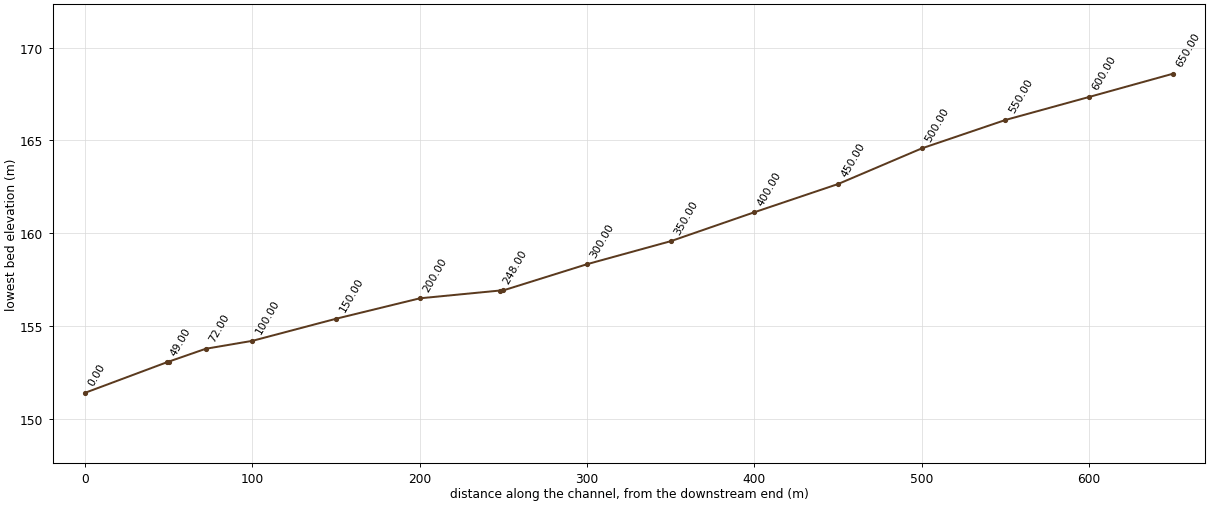
HEC-RAS study MBC.prj: meukbang-ch

--- MBC.g01 (geometry) --- (continued)

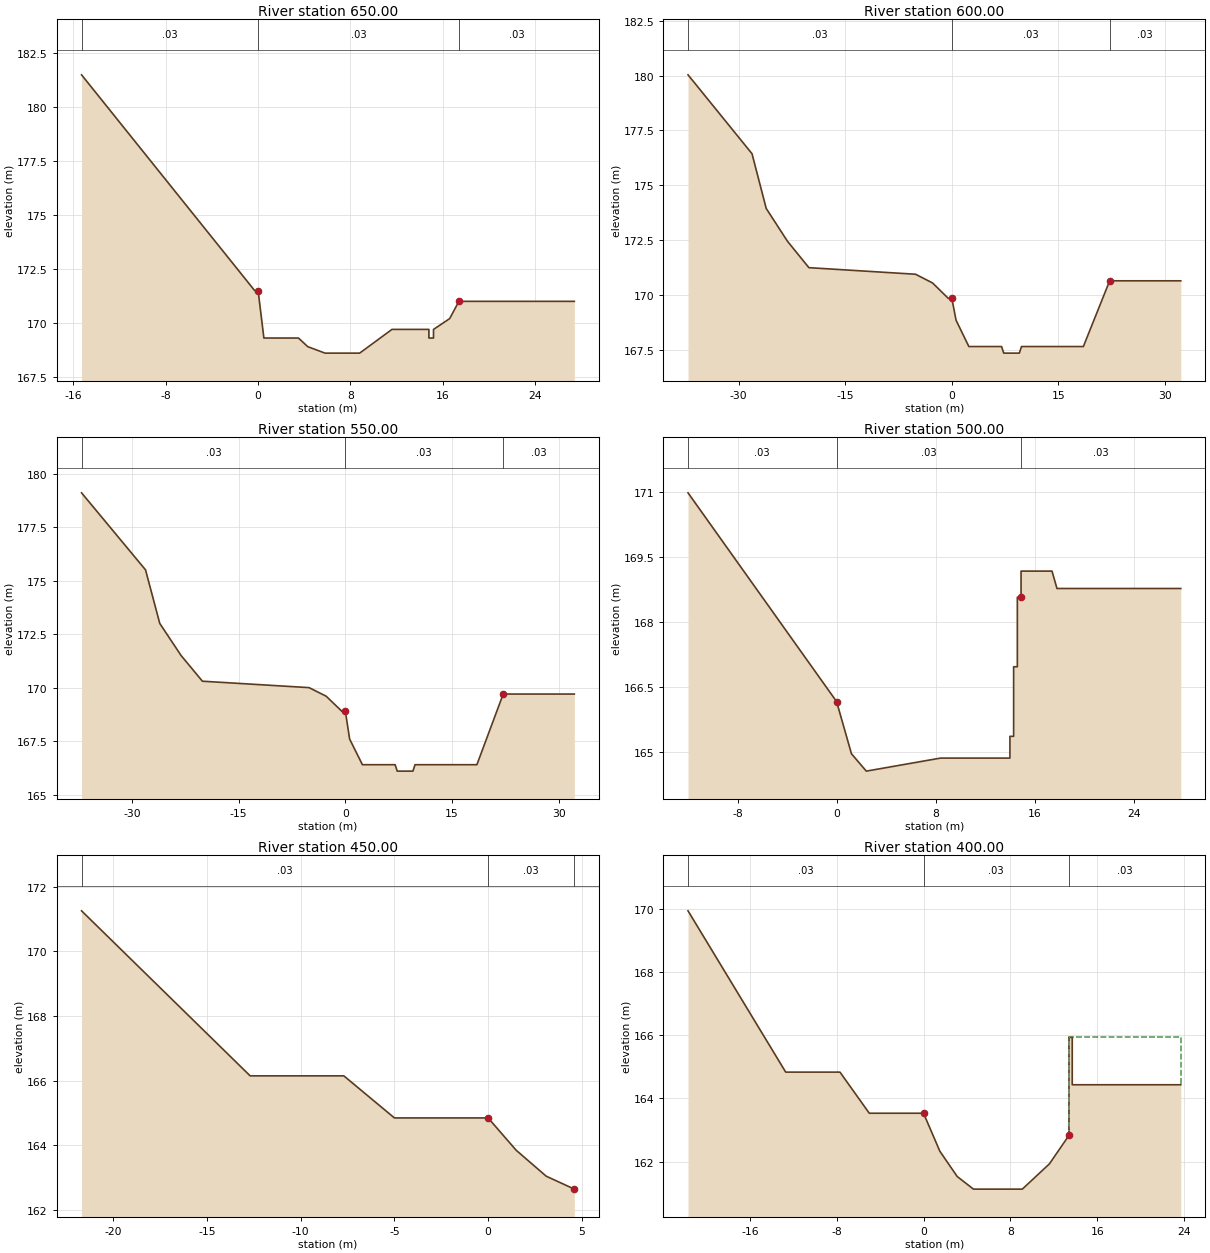
Type RM Length L Ch R = 1 ,650.00  ,50,50,50
BEGIN DESCRIPTION:
13
END DESCRIPTION:
#Sta/Elev= 18
   -15.3  181.49    -6.3  175.49    -3.3  173.49     -.3  171.49       0  171.49
      .5  169.29     3.5  169.29     4.3  168.89     5.8  168.59     8.8  168.59
    11.6  169.69    14.8  169.69    14.8  169.29    15.2  169.29    15.2  169.69
    16.6  170.19    17.4  170.99    27.4  170.99
#Mann= 3 , 0 , 0
   -15.3     .03       0       0     .03       0    17.4     .03       0
#XS Ineff= 2 , 0
               0  171.49    17.4          170.99
Permanent Ineff=
       F       F
Bank Sta=0,17.4
XS Rating Curve= 0
Exp/Cntr=.3,.1

Type RM Length L Ch R = 1 ,600.00  ,50,50,50
BEGIN DESCRIPTION:
12
END DESCRIPTION:
#Sta/Elev= 18
   -37.1  180.04   -28.1  176.44   -26.1  173.94   -23.1  172.44   -20.1  171.24
    -5.1  170.94    -2.7  170.54     -.5  169.84       0  169.84      .6  168.84
     2.4  167.64       7  167.64     7.3  167.34     9.5  167.34     9.8  167.64
    18.5  167.64    22.2  170.64    32.2  170.64
#Mann= 3 , 0 , 0
   -37.1     .03       0       0     .03       0    22.2     .03       0
#XS Ineff= 2 , 0
               0  169.84    22.2          170.64
Permanent Ineff=
       F       F
Bank Sta=0,22.2
XS Rating Curve= 0
Exp/Cntr=.3,.1

Type RM Length L Ch R = 1 ,550.00  ,50,50,50
BEGIN DESCRIPTION:
11
END DESCRIPTION:
#Sta/Elev= 18
   -37.1   179.1   -28.1   175.5   -26.1     173   -23.1   171.5   -20.1   170.3
    -5.1     170    -2.7   169.6     -.5   168.9       0   168.9      .6   167.6
     2.4   166.4       7   166.4     7.3   166.1     9.5   166.1     9.8   166.4
    18.5   166.4    22.2   169.7    32.2   169.7
#Mann= 3 , 0 , 0
   -37.1     .03       0       0     .03       0    22.2     .03       0
#XS Ineff= 2 , 0
               0   168.9    22.2           169.7
Permanent Ineff=
       F       F
Bank Sta=0,22.2
XS Rating Curve= 0
Exp/Cntr=.3,.1

Type RM Length L Ch R = 1 ,500.00  ,50,50,50
BEGIN DESCRIPTION:
10
END DESCRIPTION:
#Sta/Elev= 19
     -12  170.97      -9  169.77      -6  168.57      -3  167.37       0  166.17
     1.2  164.97     2.4  164.57     8.4  164.87      14  164.87      14  165.37
    14.3  165.37    14.3  166.97    14.6  166.97    14.6  168.57    14.9  168.57
    14.9  169.17    17.4  169.17    17.8  168.77    27.8  168.77
#Mann= 3 , 0 , 0
     -12     .03       0       0     .03       0    14.9     .03       0
Bank Sta=0,14.9
XS Rating Curve= 0
Exp/Cntr=.3,.1

Type RM Length L Ch R = 1 ,450.00  ,50,50,50
BEGIN DESCRIPTION:
9
END DESCRIPTION:
#Sta/Elev= 10
   -21.7  171.25   -18.7  169.55   -15.7  167.85   -12.7  166.15    -7.7  166.15
      -5  164.85       0  164.85     1.5  163.85     3.1  163.05     4.6  162.65
#Mann= 3 , 0 , 0
   -21.7     .03       0       0     .03       0     4.6     .03       0
#XS Ineff= 2 , 0
               0  164.85     4.6          162.65
Permanent Ineff=
       F       F
Bank Sta=0,4.6
XS Rating Curve= 0
Exp/Cntr=.3,.1

Type RM Length L Ch R = 1 ,400.00  ,50,50,50
BEGIN DESCRIPTION:
8
END DESCRIPTION:
#Sta/Elev= 15
   -21.7  169.93   -12.7  164.83    -7.7  164.83      -5  163.53       0  163.53
     1.5  162.33     3.1  161.53     4.6  161.13     9.1  161.13    11.6  161.93
    13.4  162.83    13.4  165.93    13.7  165.93    13.7  164.43    23.7  164.43
#Mann= 3 , 0 , 0
   -21.7     .03       0       0     .03       0    13.4     .03       0
#XS Ineff= 2 , 0
               0  163.53    13.4          165.93
Permanent Ineff=
       F       F
Bank Sta=0,13.4
XS Rating Curve= 0
Exp/Cntr=.3,.1

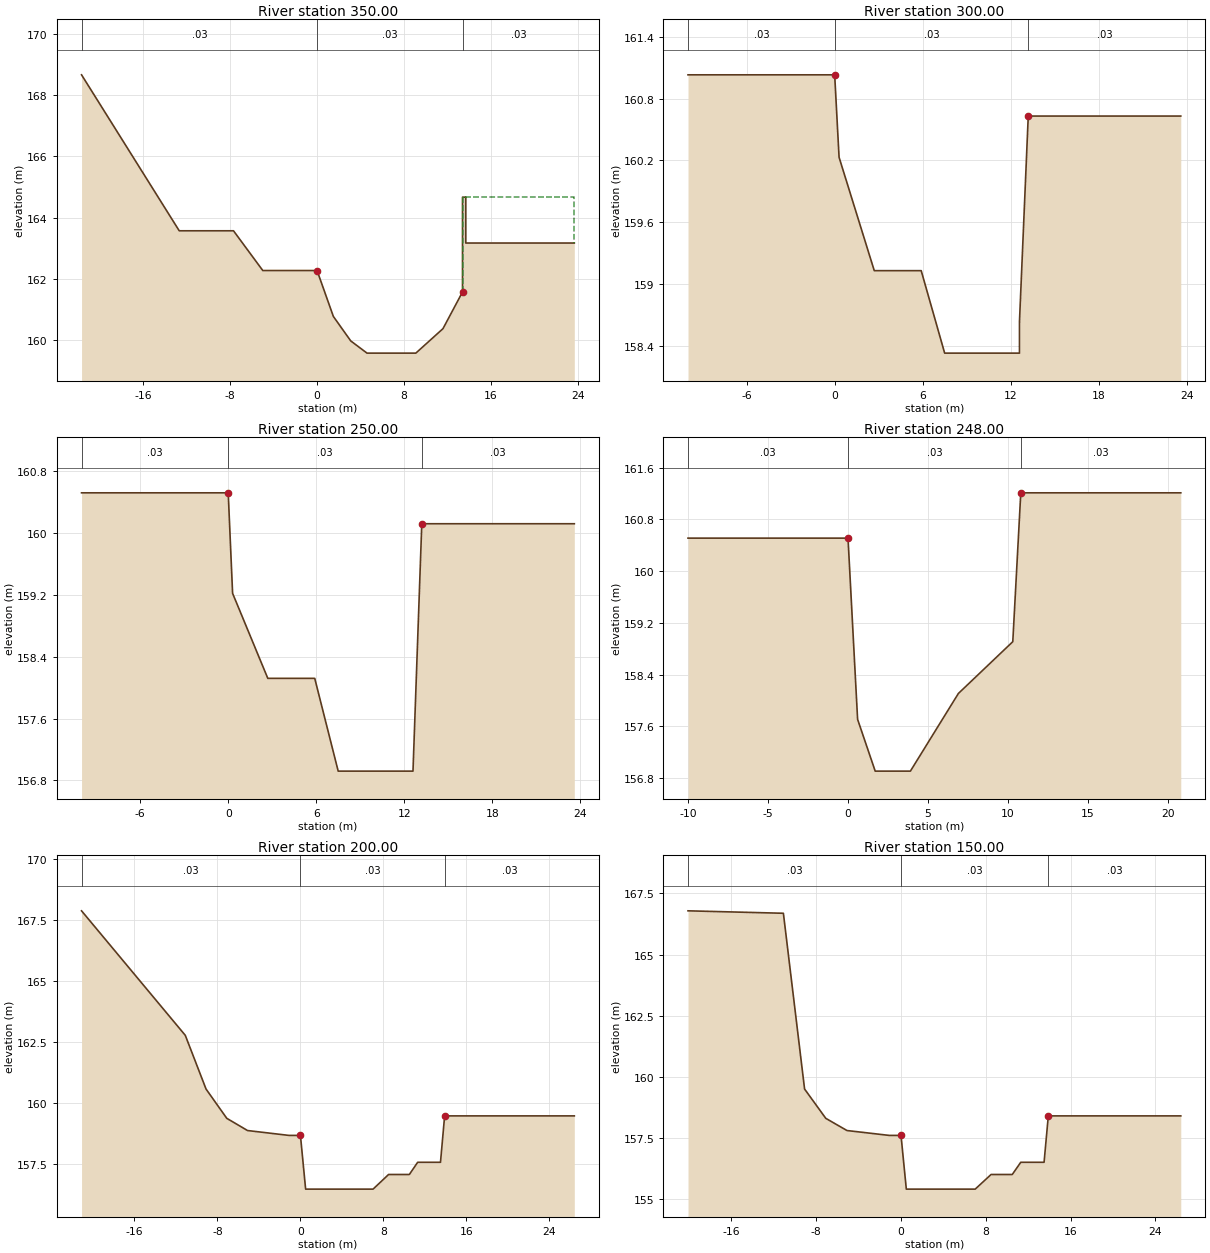
Type RM Length L Ch R = 1 ,350.00  ,50,50,50
BEGIN DESCRIPTION:
7
END DESCRIPTION:
#Sta/Elev= 15
   -21.7  168.67   -12.7  163.57    -7.7  163.57      -5  162.27       0  162.27
     1.5  160.77     3.1  159.97     4.6  159.57     9.1  159.57    11.6  160.37
    13.4  161.57    13.4  164.67    13.7  164.67    13.7  163.17    23.7  163.17
#Mann= 3 , 0 , 0
   -21.7     .03       0       0     .03       0    13.4     .03       0
#XS Ineff= 2 , 0
               0  162.27    13.4          164.67
Permanent Ineff=
       F       F
Bank Sta=0,13.4
XS Rating Curve= 0
Exp/Cntr=.3,.1

Type RM Length L Ch R = 1 ,300.00  ,50,50,50
BEGIN DESCRIPTION:
6
END DESCRIPTION:
#Sta/Elev= 11
     -10  161.03       0  161.03      .3  160.23     2.7  159.13     5.9  159.13
     7.5  158.33    12.6  158.33    12.6  158.63    13.2  160.63    13.6  160.63
    23.6  160.63
#Mann= 3 , 0 , 0
     -10     .03       0       0     .03       0    13.2     .03       0
#XS Ineff= 2 , 0
               0  161.03    13.2          160.63
Permanent Ineff=
       F       F
Bank Sta=0,13.2
XS Rating Curve= 0
Exp/Cntr=.3,.1

Type RM Length L Ch R = 1 ,250.00  ,2,2,2
BEGIN DESCRIPTION:
5
END DESCRIPTION:
#Sta/Elev= 10
     -10  160.52       0  160.52      .3  159.22     2.7  158.12     5.9  158.12
     7.5  156.92    12.6  156.92    13.2  160.12    13.6  160.12    23.6  160.12
#Mann= 3 , 0 , 0
     -10     .03       0       0     .03       0    13.2     .03       0
#XS Ineff= 2 , 0
               0  160.52    13.2          160.12
Permanent Ineff=
       F       F
Bank Sta=0,13.2
XS Rating Curve= 0
Exp/Cntr=.3,.1

Type RM Length L Ch R = 1 ,248.00  ,48,48,48
BEGIN DESCRIPTION:
4.048
END DESCRIPTION:
#Sta/Elev= 9
     -10  160.51       0  160.51      .6  157.71     1.7  156.91     3.9  156.91
     6.9  158.11    10.3  158.91    10.8  161.21    20.8  161.21
#Mann= 3 , 0 , 0
     -10     .03       0       0     .03       0    10.8     .03       0
#XS Ineff= 2 , 0
               0  160.51    10.8          161.21
Permanent Ineff=
       F       F
Bank Sta=0,10.8
XS Rating Curve= 0
Exp/Cntr=.3,.1

Type RM Length L Ch R = 1 ,200.00  ,50,50,50
BEGIN DESCRIPTION:
4
END DESCRIPTION:
#Sta/Elev= 16
   -21.1  167.89   -11.1  162.79    -9.1  160.59    -7.1  159.39    -5.1  158.89
    -1.1  158.69       0  158.69      .5  156.49       7  156.49     8.5  157.09
    10.5  157.09    11.3  157.59    13.5  157.59    13.9  159.49    16.4  159.49
    26.4  159.49
#Mann= 3 , 0 , 0
   -21.1     .03       0       0     .03       0    13.9     .03       0
#XS Ineff= 2 , 0
               0  158.69    13.9          159.49
Permanent Ineff=
       F       F
Bank Sta=0,13.9
XS Rating Curve= 0
Exp/Cntr=.3,.1

Type RM Length L Ch R = 1 ,150.00  ,50,50,50
BEGIN DESCRIPTION:
3
END DESCRIPTION:
#Sta/Elev= 16
   -20.1  166.79   -11.1  166.69    -9.1  159.49    -7.1  158.29    -5.1  157.79
    -1.1  157.59       0  157.59      .5  155.39       7  155.39     8.5  155.99
    10.5  155.99    11.3  156.49    13.5  156.49    13.9  158.39    16.4  158.39
    26.4  158.39
#Mann= 3 , 0 , 0
   -20.1     .03       0       0     .03       0    13.9     .03       0
#XS Ineff= 2 , 0
               0  157.59    13.9          158.39
Permanent Ineff=
       F       F
Bank Sta=0,13.9
XS Rating Curve= 0
Exp/Cntr=.3,.1

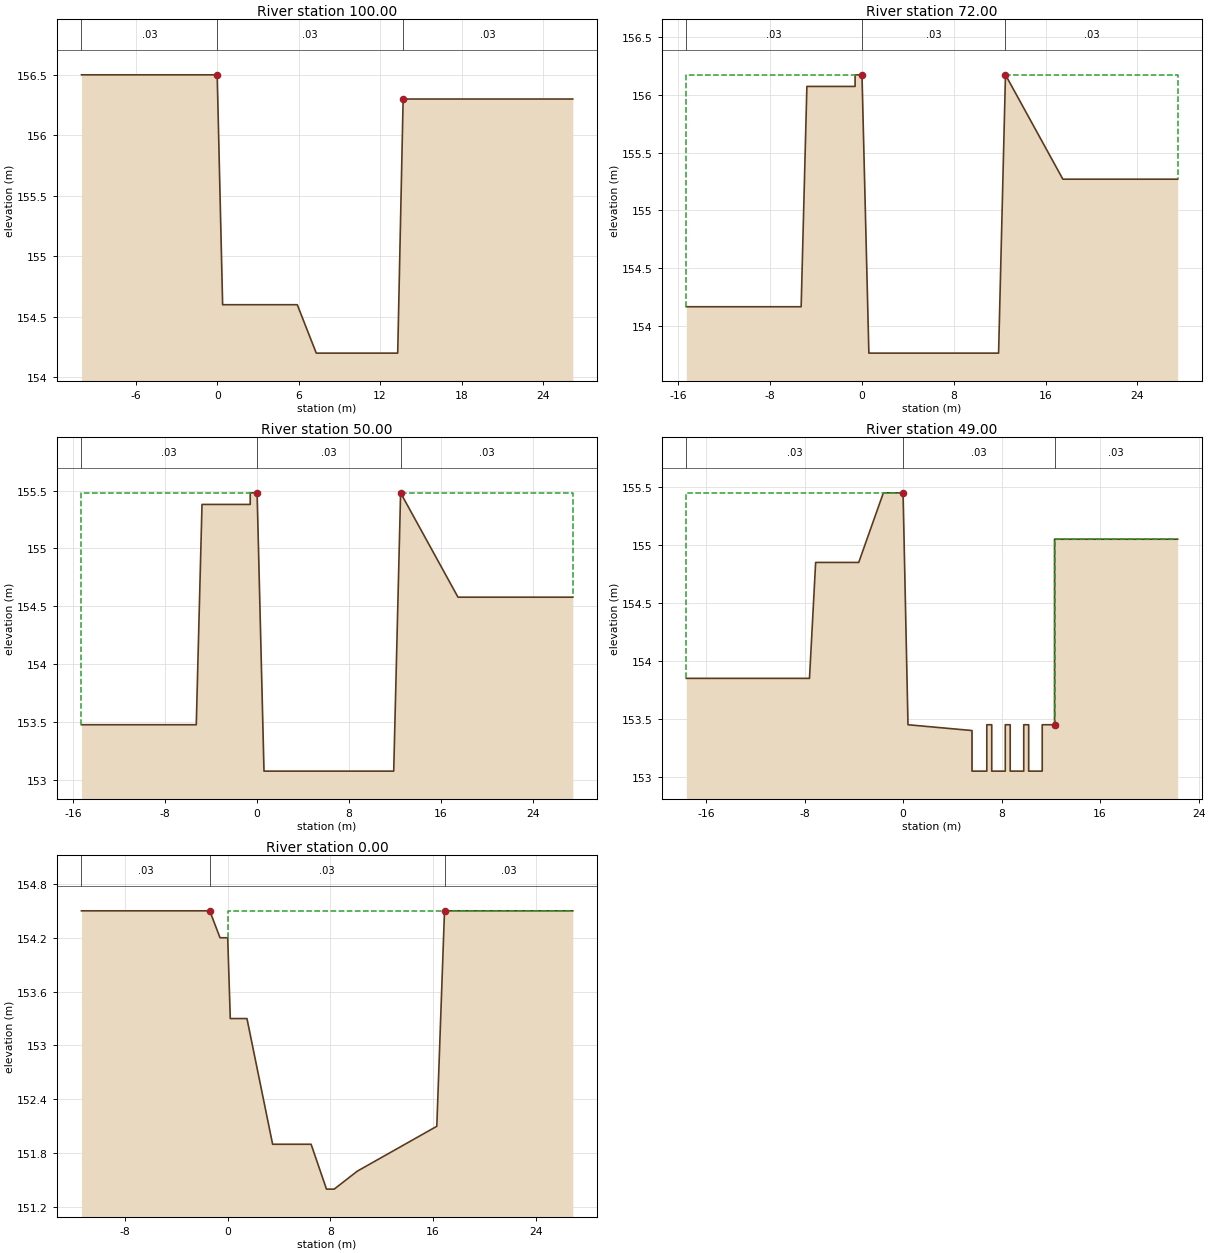
Type RM Length L Ch R = 1 ,100.00  ,28,28,28
BEGIN DESCRIPTION:
2
END DESCRIPTION:
#Sta/Elev= 9
     -10   156.5       0   156.5      .4   154.6     5.9   154.6     7.3   154.2
    13.3   154.2    13.7   156.3    16.2   156.3    26.2   156.3
#Mann= 3 , 0 , 0
     -10     .03       0       0     .03       0    13.7     .03       0
#XS Ineff= 2 , 0
               0   156.5    13.7           156.3
Permanent Ineff=
       F       F
Bank Sta=0,13.7
XS Rating Curve= 0
Exp/Cntr=.3,.1

Type RM Length L Ch R = 1 ,72.00   ,22,22,22
BEGIN DESCRIPTION:
1.022
END DESCRIPTION:
#Sta/Elev= 11
   -15.3  154.17    -5.3  154.17    -4.8  156.07     -.6  156.07     -.6  156.17
       0  156.17      .6  153.77    11.9  153.77    12.5  156.17    17.5  155.27
    27.5  155.27
#Mann= 3 , 0 , 0
   -15.3     .03       0       0     .03       0    12.5     .03       0
#XS Ineff= 2 , 0
               0  156.17    12.5          156.17
Permanent Ineff=
       F       F
Bank Sta=0,12.5
XS Rating Curve= 0
Exp/Cntr=.3,.1

Type RM Length L Ch R = 1 ,50.00   ,1,1,1
BEGIN DESCRIPTION:
1
END DESCRIPTION:
#Sta/Elev= 11
   -15.3  153.48    -5.3  153.48    -4.8  155.38     -.6  155.38     -.6  155.48
       0  155.48      .6  153.08    11.9  153.08    12.5  155.48    17.5  154.58
    27.5  154.58
#Mann= 3 , 0 , 0
   -15.3     .03       0       0     .03       0    12.5     .03       0
#XS Ineff= 2 , 0
               0  155.48    12.5          155.48
Permanent Ineff=
       F       F
Bank Sta=0,12.5
XS Rating Curve= 0
Exp/Cntr=.3,.1

Type RM Length L Ch R = 1 ,49.00   ,49,49,49
BEGIN DESCRIPTION:
0.049
END DESCRIPTION:
#Sta/Elev= 26
   -17.6  153.85    -7.6  153.85    -7.1  154.85    -3.6  154.85    -1.6  155.45
       0  155.45      .4  153.45     5.6   153.4     5.6  153.05     6.8  153.05
     6.8  153.45     7.2  153.45     7.2  153.05     8.3  153.05     8.3  153.45
     8.7  153.45     8.7  153.05     9.8  153.05     9.8  153.45    10.2  153.45
    10.2  153.05    11.3  153.05    11.3  153.45    12.3  153.45    12.3  155.05
    22.3  155.05
#Mann= 3 , 0 , 0
   -17.6     .03       0       0     .03       0    12.3     .03       0
#XS Ineff= 2 , 0
               0  155.45    12.3          155.05
Permanent Ineff=
       F       F
Bank Sta=0,12.3
XS Rating Curve= 0
Exp/Cntr=.3,.1

Type RM Length L Ch R = 1 ,0.00    ,0,0,0
BEGIN DESCRIPTION:
0
END DESCRIPTION:
#Sta/Elev= 14
   -11.4   154.5    -1.4   154.5     -.6   154.2       0   154.2      .2   153.3
     1.5   153.3     3.5   151.9     6.5   151.9     7.7   151.4     8.3   151.4
    10.1   151.6    16.3   152.1    16.9   154.5    26.9   154.5
#Mann= 3 , 0 , 0
   -11.4     .03       0    -1.4     .03       0    16.9     .03       0
#XS Ineff= 2 , 0
       0    -1.4   154.5    16.9       0   154.5
Permanent Ineff=
       F       F
Bank Sta=-1.4,16.9
XS Rating Curve= 0
Exp/Cntr=.3,.1

Chan Stop Cuts=-1