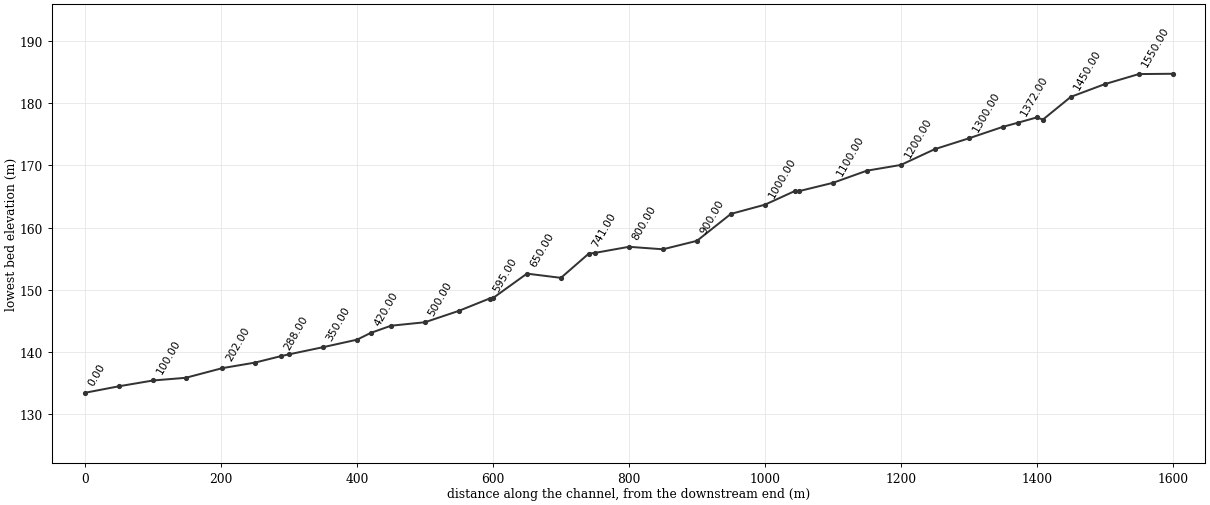
--- WJC.prj (project) ---

Proj Title=wangza-ch
Current Plan=p01
Default Exp/Contr=.3,.1
SI Units
Geom File=g01
Flow File=f01
Plan File=p01
Y Axis Title=Elevation
X Axis Title(PF)=Main Channel Distance
X Axis Title(XS)=Station
BEGIN DESCRIPTION:
           BACK WATER COMPUTATION
      APPLICATION OF HEC-2 BY Samju Construction Engineering
      wangza-ch: 10,20,30,50,80 yr
END DESCRIPTION:
DSS Export Rating Curves= 0
DSS Export Rating Curve Sorted= 0
DSS Export Volume Flow Curves= 0
DXF OffsetX= 0
DXF OffsetY= 0
DXF ScaleX= 1
DXF ScaleY= 10

--- WJC.p01 (plan) ---

Plan Title=Imported Plan 01
Version=Version 3.0.1  Mar 2001
Short Identifier=Imported Pla
Geom File=g01
Flow File=f01
Subcritical Flow
K Sum by GR= 0
Std Step Tol= 0.003
Critical Tol= 0.003
Num of Std Step Trials= 20
Max Error Tol= 0.1
Flow Tol Ratio= 0.001
Split Flow NTrial= 30
Split Flow Tol= 0.02
Split Flow Ratio= 0.02
Log Output Level= 0
Friction Slope Method= 1
Unsteady Friction Slope Method= 2
Parabolic Critical Depth
Global Vel Dist= 0 , 0 , 0
Global Log Level= 0
CheckData=True
Encroach Param=-1 ,0,0, 0
Computation Interval=1HOUR
Output Interval=1HOUR
Run HTab= 0
Run UNet= 0
Run PostProcess= 0
UNET Theta= 1
UNET ZTol= 0.02
UNET ZSATol= 0.1
UNET MxIter= 20
UNET MaxInSteps= 20
UNET DtIC= 0
UNET DtMin= 0
UNET MaxCRTS= 20
UNET WFStab= 2
UNET SFStab= 1
UNET WFX= 1
UNET SFX= 1
UNET Convert EG Bridges=-1
UNET Use Existing IB Tables=-1
Instantaneous Interval=1HOUR
Write IC File= 0
Write Velocity= 0
Write Detailed= 0

--- WJC.f01 (steady flow) ---

Flow Title=Imported Flow 01
Version=Version 3.0.1  Mar 2001
Number of Profiles= 5
Profile Names=10YR,20YR,30YR,50YR,80YR
River Rch & RM=RIVER-1,Reach-1         ,1600.00
    14.6   16.08   16.95   18.04   19.05
River Rch & RM=RIVER-1,Reach-1         ,1400.00
   23.88   26.32   27.75   29.55    31.2
Boundary for River Rch & Prof#=RIVER-1,Reach-1         , 1
Up Type= 0
Dn Type= 3
Dn Slope=.038
Boundary for River Rch & Prof#=RIVER-1,Reach-1         , 2
Up Type= 0
Dn Type= 3
Dn Slope=.038
Boundary for River Rch & Prof#=RIVER-1,Reach-1         , 3
Up Type= 0
Dn Type= 3
Dn Slope=.038
Boundary for River Rch & Prof#=RIVER-1,Reach-1         , 4
Up Type= 0
Dn Type= 3
Dn Slope=.038
Boundary for River Rch & Prof#=RIVER-1,Reach-1         , 5
Up Type= 0
Dn Type= 3
Dn Slope=.038
DSS Import GetInterval= 0
DSS Import GetPeak= 0
DSS Import FillOption= 0

--- WJC.g01 (geometry) ---

Geom Title=Imported Geom 01
Version=Version 3.0.1  Mar 2001

River Reach=RIVER-1         ,Reach-1
Reach XY= 2
              .5             .95              .5             .05

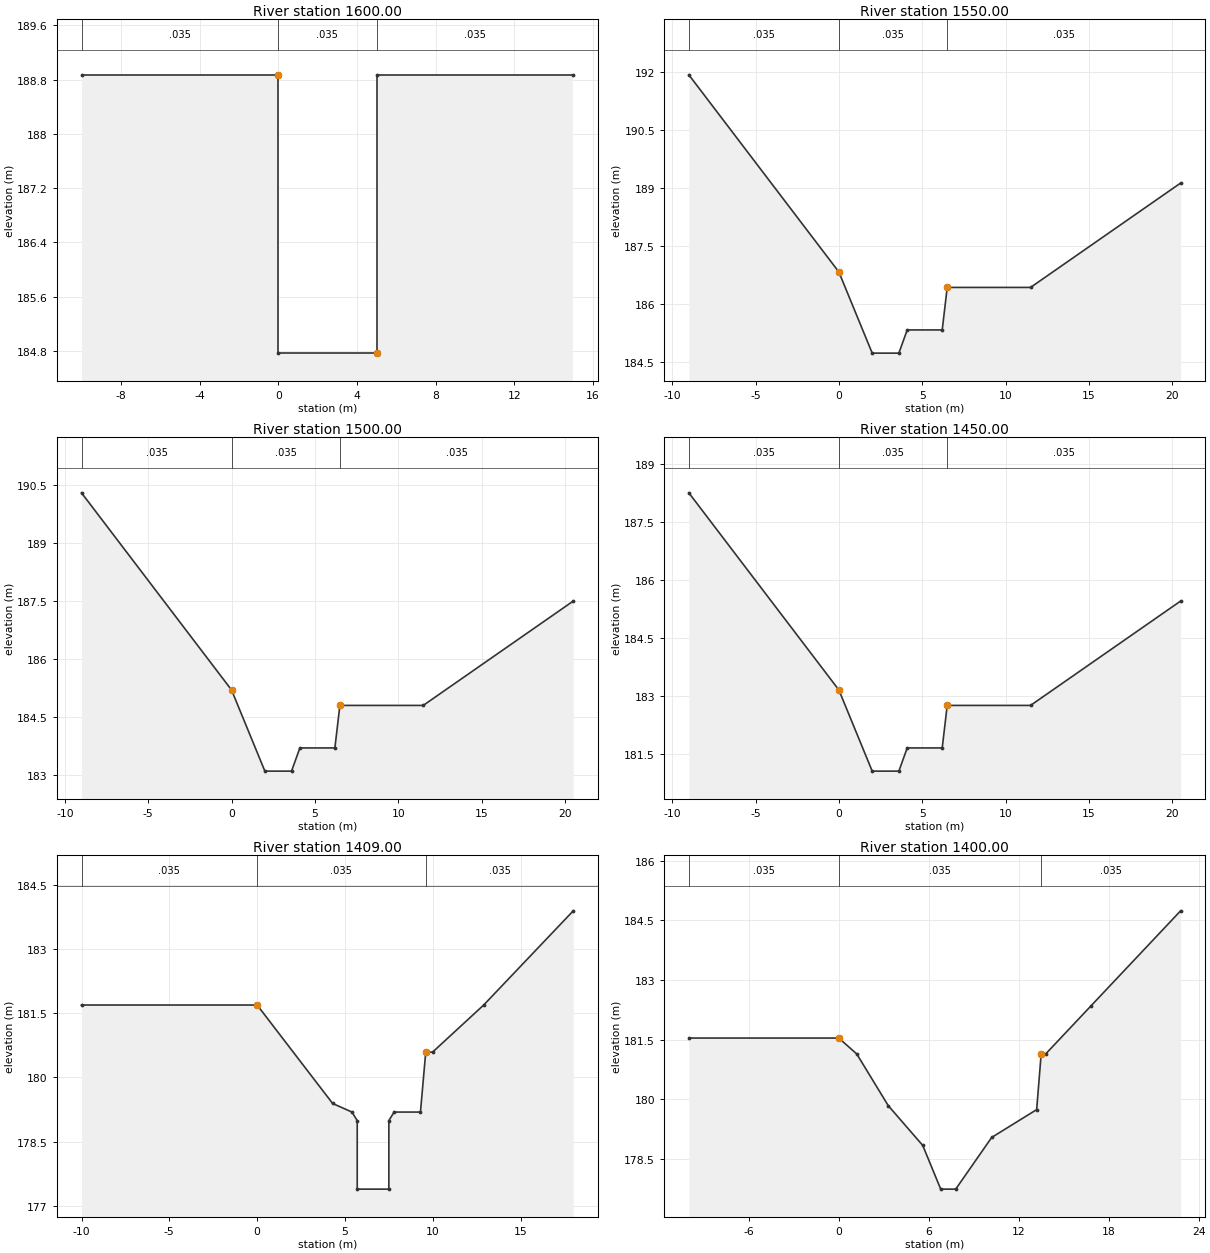
Type RM Length L Ch R = 1 ,1600.00 ,50,50,50
BEGIN DESCRIPTION:
31.017
END DESCRIPTION:
#Sta/Elev= 6
     -10  188.87       0  188.87       0  184.77       5  184.77       5  188.87
      15  188.87
#Mann= 3 , 0 , 0
     -10    .035       0       0    .035       0       5    .035       0
#XS Ineff= 2 , 0
       0       0  188.87       5       0  184.77
Permanent Ineff=
       F       F
Bank Sta=0,5
XS Rating Curve= 0
Exp/Cntr=.3,.1

Type RM Length L Ch R = 1 ,1550.00 ,50,50,50
BEGIN DESCRIPTION:
31
END DESCRIPTION:
#Sta/Elev= 9
      -9  191.92       0  186.82       2  184.72     3.6  184.72     4.1  185.32
     6.2  185.32     6.5  186.42    11.5  186.42    20.5  189.12
#Mann= 3 , 0 , 0
      -9    .035       0       0    .035       0     6.5    .035       0
#XS Ineff= 2 , 0
               0  186.82     6.5          186.42
Permanent Ineff=
       F       F
Bank Sta=0,6.5
XS Rating Curve= 0
Exp/Cntr=.3,.1

Type RM Length L Ch R = 1 ,1500.00 ,50,50,50
BEGIN DESCRIPTION:
30
END DESCRIPTION:
#Sta/Elev= 9
      -9   190.3       0   185.2       2   183.1     3.6   183.1     4.1   183.7
     6.2   183.7     6.5   184.8    11.5   184.8    20.5   187.5
#Mann= 3 , 0 , 0
      -9    .035       0       0    .035       0     6.5    .035       0
#XS Ineff= 2 , 0
       0       0   185.2     6.5       0   184.8
Permanent Ineff=
       F       F
Bank Sta=0,6.5
XS Rating Curve= 0
Exp/Cntr=.3,.1

Type RM Length L Ch R = 1 ,1450.00 ,41,41,41
BEGIN DESCRIPTION:
29
END DESCRIPTION:
#Sta/Elev= 9
      -9  188.25       0  183.15       2  181.05     3.6  181.05     4.1  181.65
     6.2  181.65     6.5  182.75    11.5  182.75    20.5  185.45
#Mann= 3 , 0 , 0
      -9    .035       0       0    .035       0     6.5    .035       0
#XS Ineff= 2 , 0
       0       0  183.15     6.5       0  182.75
Permanent Ineff=
       F       F
Bank Sta=0,6.5
XS Rating Curve= 0
Exp/Cntr=.3,.1

Type RM Length L Ch R = 1 ,1409.00 ,9,9,9
BEGIN DESCRIPTION:
28.009
END DESCRIPTION:
#Sta/Elev= 14
     -10  181.69       0  181.69     4.3  179.39     5.4  179.19     5.7  178.99
     5.7  177.39     7.5  177.39     7.5  178.99     7.8  179.19     9.3  179.19
     9.6  180.59    9.99  180.59    12.9  181.69      18  183.89
#Mann= 3 , 0 , 0
     -10    .035       0       0    .035       0     9.6    .035       0
#XS Ineff= 2 , 0
       0       0  181.69     9.6       0  180.59
Permanent Ineff=
       F       F
Bank Sta=0,9.6
XS Rating Curve= 0
Exp/Cntr=.3,.1

Type RM Length L Ch R = 1 ,1400.00 ,28,28,28
BEGIN DESCRIPTION:
28
END DESCRIPTION:
#Sta/Elev= 13
     -10  181.54       0  181.54     1.2  181.14     3.3  179.84     5.6  178.84
     6.8  177.74     7.8  177.74    10.2  179.04    13.2  179.74    13.5  181.14
    13.8  181.14    16.8  182.34    22.8  184.74
#Mann= 3 , 0 , 0
     -10    .035       0       0    .035       0    13.5    .035       0
#XS Ineff= 2 , 0
               0  181.54    13.5          181.14
Permanent Ineff=
       F       F
Bank Sta=0,13.5
XS Rating Curve= 0
Exp/Cntr=.3,.1

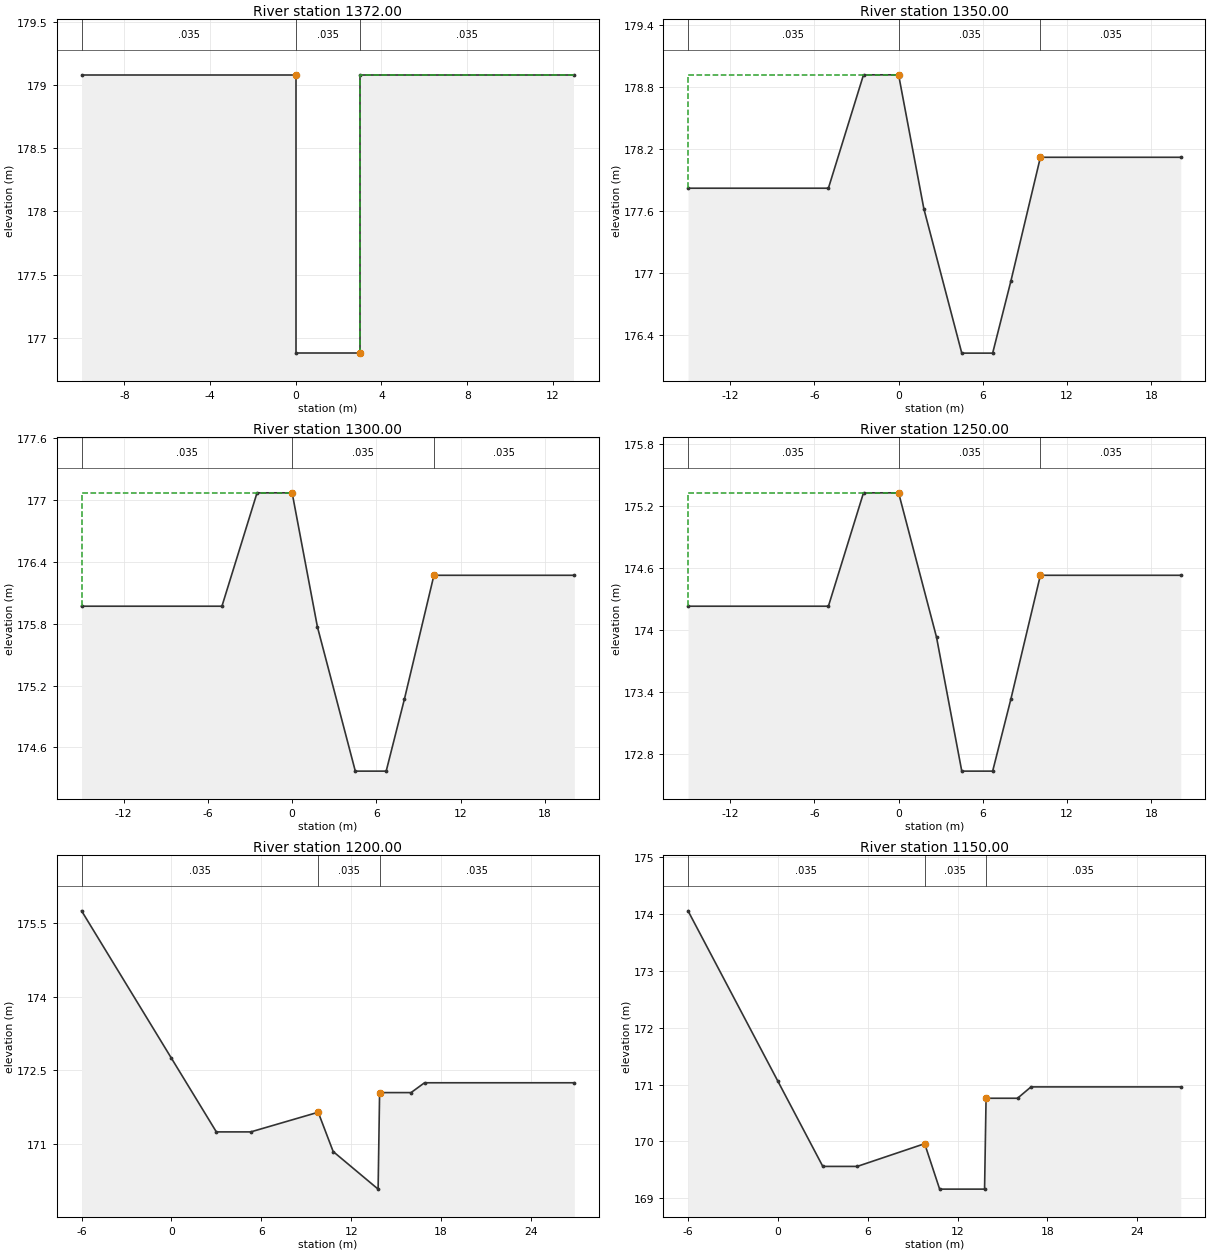
Type RM Length L Ch R = 1 ,1372.00 ,22,22,22
BEGIN DESCRIPTION:
27.022
END DESCRIPTION:
#Sta/Elev= 6
     -10  179.08       0  179.08       0  176.88       3  176.88       3  179.08
      13  179.08
#Mann= 3 , 0 , 0
     -10    .035       0       0    .035       0       3    .035       0
#XS Ineff= 2 , 0
               0  179.08       3          179.08
Permanent Ineff=
       F       F
Bank Sta=0,3
XS Rating Curve= 0
Exp/Cntr=.3,.1

Type RM Length L Ch R = 1 ,1350.00 ,50,50,50
BEGIN DESCRIPTION:
27
END DESCRIPTION:
#Sta/Elev= 10
     -15  177.82      -5  177.82    -2.5  178.92       0  178.92     1.8  177.62
     4.5  176.22     6.7  176.22       8  176.92    10.1  178.12    20.1  178.12
#Mann= 3 , 0 , 0
     -15    .035       0       0    .035       0    10.1    .035       0
#XS Ineff= 2 , 0
               0  178.92    10.1          178.12
Permanent Ineff=
       F       F
Bank Sta=0,10.1
XS Rating Curve= 0
Exp/Cntr=.3,.1

Type RM Length L Ch R = 1 ,1300.00 ,50,50,50
BEGIN DESCRIPTION:
26
END DESCRIPTION:
#Sta/Elev= 10
     -15  175.97      -5  175.97    -2.5  177.07       0  177.07     1.8  175.77
     4.5  174.37     6.7  174.37       8  175.07    10.1  176.27    20.1  176.27
#Mann= 3 , 0 , 0
     -15    .035       0       0    .035       0    10.1    .035       0
#XS Ineff= 2 , 0
               0  177.07    10.1          176.27
Permanent Ineff=
       F       F
Bank Sta=0,10.1
XS Rating Curve= 0
Exp/Cntr=.3,.1

Type RM Length L Ch R = 1 ,1250.00 ,50,50,50
BEGIN DESCRIPTION:
25
END DESCRIPTION:
#Sta/Elev= 10
     -15  174.23      -5  174.23    -2.5  175.33       0  175.33     2.7  173.93
     4.5  172.63     6.7  172.63       8  173.33    10.1  174.53    20.1  174.53
#Mann= 3 , 0 , 0
     -15    .035       0       0    .035       0    10.1    .035       0
#XS Ineff= 2 , 0
               0  175.33    10.1          174.53
Permanent Ineff=
       F       F
Bank Sta=0,10.1
XS Rating Curve= 0
Exp/Cntr=.3,.1

Type RM Length L Ch R = 1 ,1200.00 ,50,50,50
BEGIN DESCRIPTION:
24
END DESCRIPTION:
#Sta/Elev= 11
      -6  175.75       0  172.75       3  171.25     5.3  171.25     9.8  171.65
    10.8  170.85    13.8 170.085    13.9  172.05      16  172.05    16.9  172.25
    26.9  172.25
#Mann= 3 , 0 , 0
      -6    .035       0     9.8    .035       0    13.9    .035       0
#XS Ineff= 2 , 0
       0     9.8  171.65    13.9       0  172.05
Permanent Ineff=
       F       F
Bank Sta=9.8,13.9
XS Rating Curve= 0
Exp/Cntr=.3,.1

Type RM Length L Ch R = 1 ,1150.00 ,50,50,50
BEGIN DESCRIPTION:
23
END DESCRIPTION:
#Sta/Elev= 11
      -6  174.06       0  171.06       3  169.56     5.3  169.56     9.8  169.96
    10.8  169.16    13.8  169.16    13.9  170.76      16  170.76    16.9  170.96
    26.9  170.96
#Mann= 3 , 0 , 0
      -6    .035       0     9.8    .035       0    13.9    .035       0
#XS Ineff= 2 , 0
       0     9.8  169.96    13.9       0  170.76
Permanent Ineff=
       F       F
Bank Sta=9.8,13.9
XS Rating Curve= 0
Exp/Cntr=.3,.1

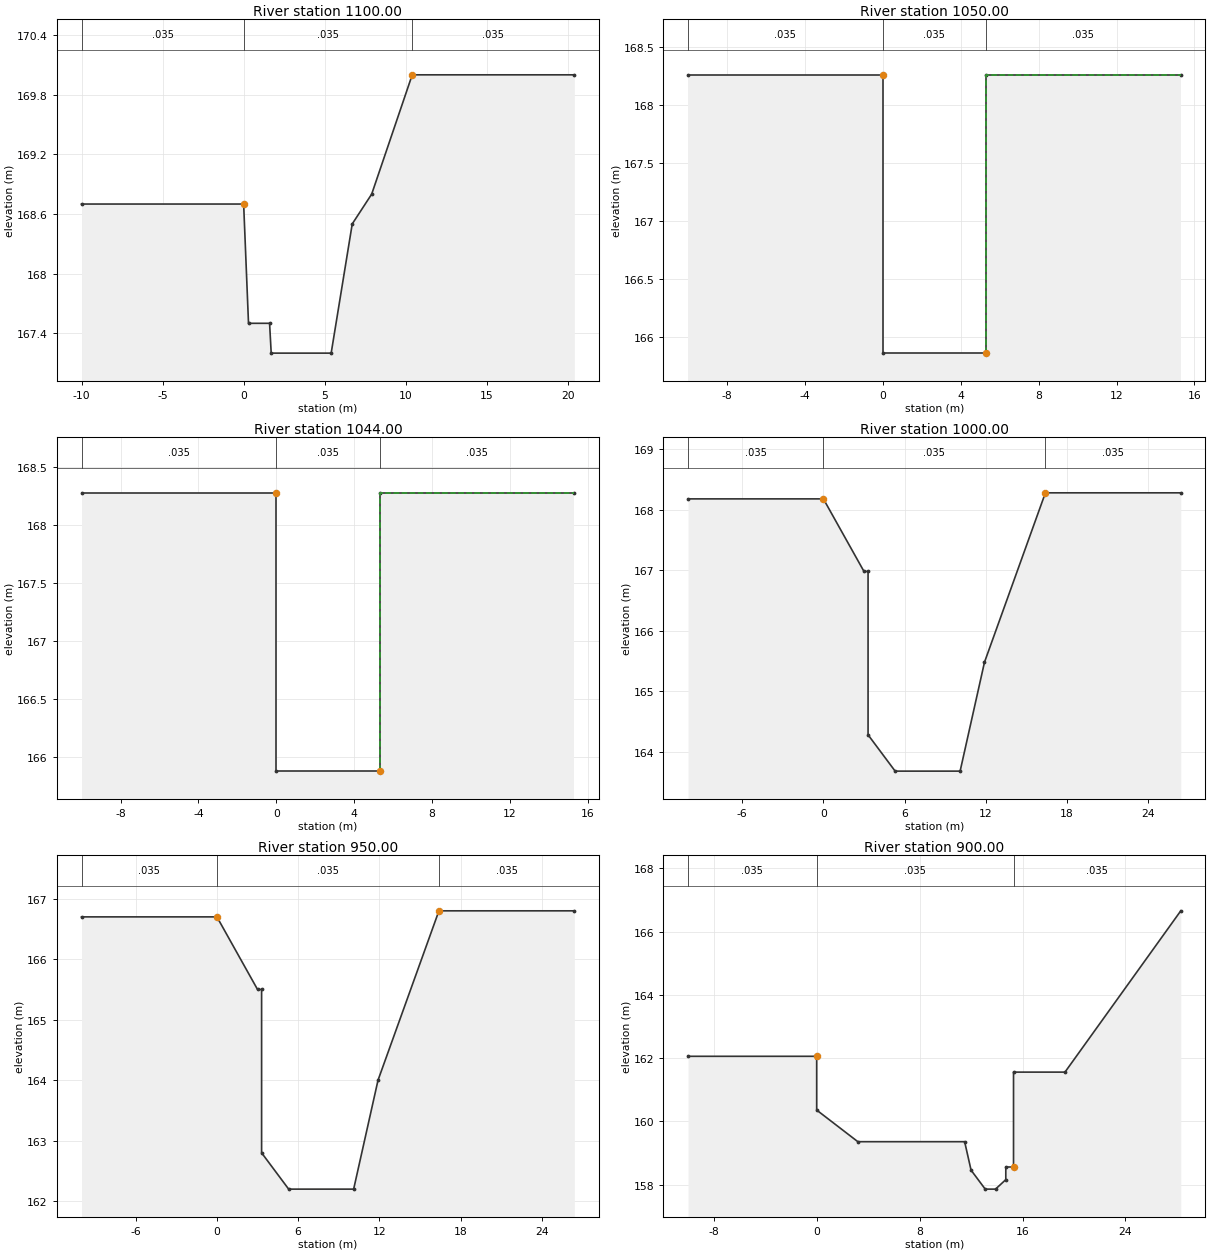
Type RM Length L Ch R = 1 ,1100.00 ,50,50,50
BEGIN DESCRIPTION:
22
END DESCRIPTION:
#Sta/Elev= 10
     -10   168.7       0   168.7      .3   167.5     1.6   167.5     1.7   167.2
     5.4   167.2     6.7   168.5     7.9   168.8    10.4     170    20.4     170
#Mann= 3 , 0 , 0
     -10    .035       0       0    .035       0    10.4    .035       0
#XS Ineff= 2 , 0
       0       0   168.7    10.4       0     170
Permanent Ineff=
       F       F
Bank Sta=0,10.4
XS Rating Curve= 0
Exp/Cntr=.3,.1

Type RM Length L Ch R = 1 ,1050.00 ,6,6,6
BEGIN DESCRIPTION:
21
END DESCRIPTION:
#Sta/Elev= 6
     -10  168.26       0  168.26       0  165.86     5.3  165.86     5.3  168.26
    15.3  168.26
#Mann= 3 , 0 , 0
     -10    .035       0       0    .035       0     5.3    .035       0
#XS Ineff= 2 , 0
               0  168.26     5.3          168.26
Permanent Ineff=
       F       F
Bank Sta=0,5.3
XS Rating Curve= 0
Exp/Cntr=.3,.1

Type RM Length L Ch R = 1 ,1044.00 ,44,44,44
BEGIN DESCRIPTION:
20.044
END DESCRIPTION:
#Sta/Elev= 6
     -10  168.28       0  168.28       0  165.88     5.3  165.88     5.3  168.28
    15.3  168.28
#Mann= 3 , 0 , 0
     -10    .035       0       0    .035       0     5.3    .035       0
#XS Ineff= 2 , 0
               0  168.28     5.3          168.28
Permanent Ineff=
       F       F
Bank Sta=0,5.3
XS Rating Curve= 0
Exp/Cntr=.3,.1

Type RM Length L Ch R = 1 ,1000.00 ,50,50,50
BEGIN DESCRIPTION:
20
END DESCRIPTION:
#Sta/Elev= 10
     -10  168.18       0  168.18       3  166.98     3.3  166.98     3.3  164.28
     5.3  163.68    10.1  163.68    11.9  165.48    16.4  168.28    26.4  168.28
#Mann= 3 , 0 , 0
     -10    .035       0       0    .035       0    16.4    .035       0
#XS Ineff= 2 , 0
               0  168.18    16.4          168.28
Permanent Ineff=
       F       F
Bank Sta=0,16.4
XS Rating Curve= 0
Exp/Cntr=.3,.1

Type RM Length L Ch R = 1 ,950.00  ,50,50,50
BEGIN DESCRIPTION:
19
END DESCRIPTION:
#Sta/Elev= 10
     -10   166.7       0   166.7       3   165.5     3.3   165.5     3.3   162.8
     5.3   162.2    10.1   162.2    11.9     164    16.4   166.8    26.4   166.8
#Mann= 3 , 0 , 0
     -10    .035       0       0    .035       0    16.4    .035       0
#XS Ineff= 2 , 0
               0   166.7    16.4           166.8
Permanent Ineff=
       F       F
Bank Sta=0,16.4
XS Rating Curve= 0
Exp/Cntr=.3,.1

Type RM Length L Ch R = 1 ,900.00  ,50,50,50
BEGIN DESCRIPTION:
18
END DESCRIPTION:
#Sta/Elev= 14
     -10  162.06       0  162.06       0  160.36     3.2  159.36    11.5  159.36
      12  158.46    13.1  157.86    13.9  157.86    14.7  158.16    14.7  158.56
    15.3  158.56    15.3  161.56    19.3  161.56    28.3  166.66
#Mann= 3 , 0 , 0
     -10    .035       0       0    .035       0    15.3    .035       0
Bank Sta=0,15.3
XS Rating Curve= 0
Exp/Cntr=.3,.1

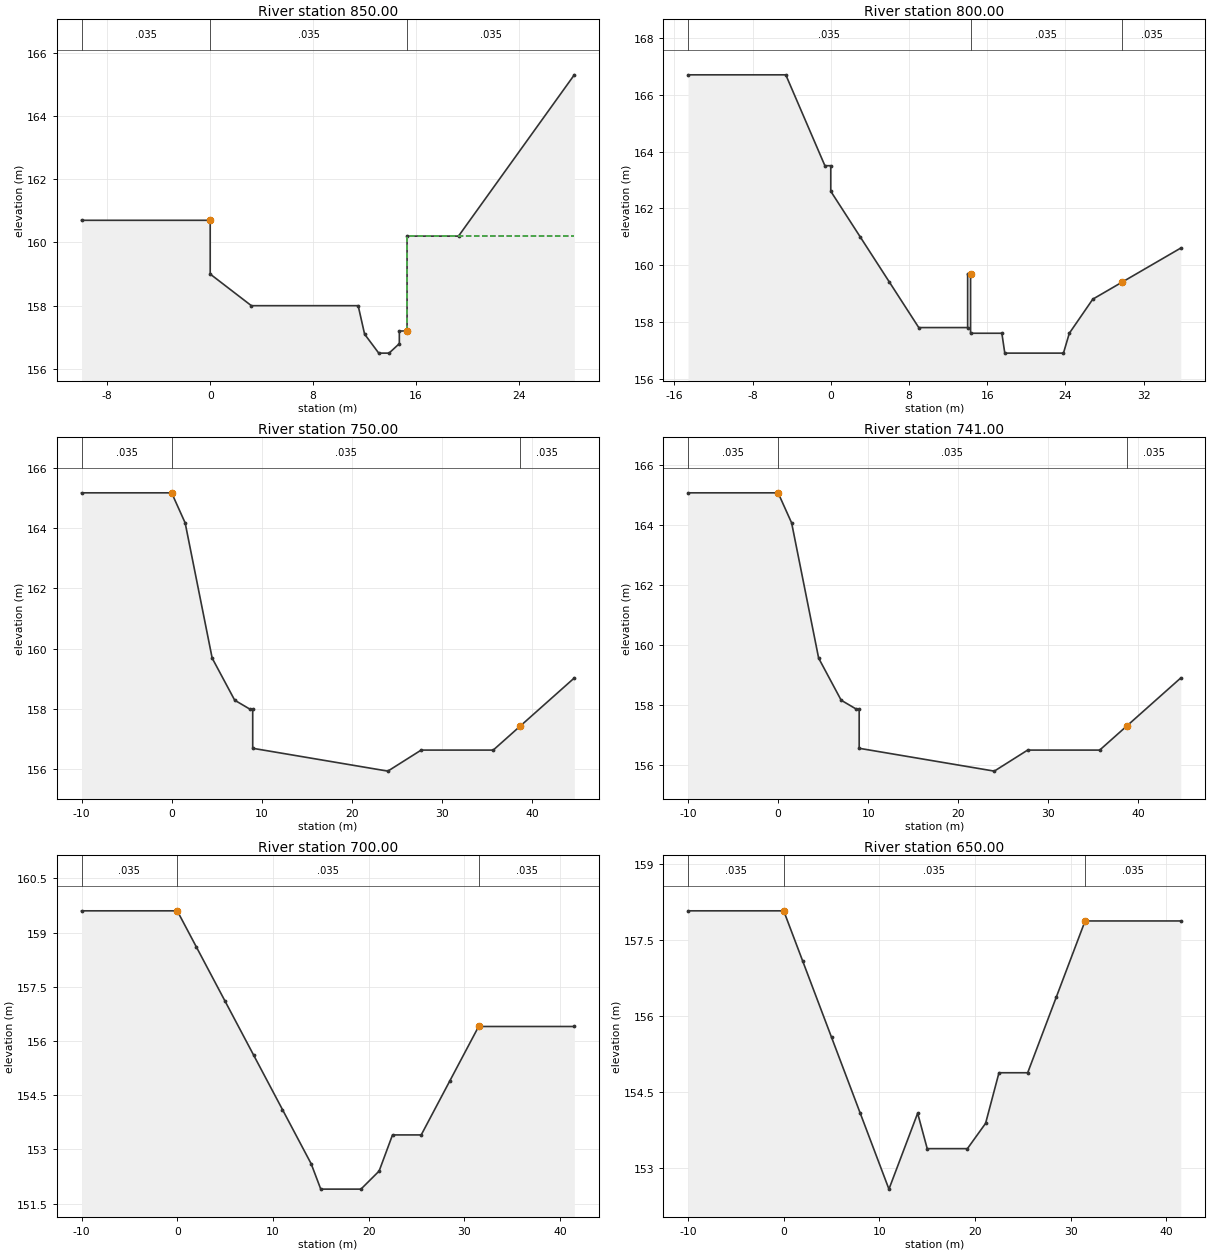
Type RM Length L Ch R = 1 ,850.00  ,50,50,50
BEGIN DESCRIPTION:
17
END DESCRIPTION:
#Sta/Elev= 14
     -10   160.7       0   160.7       0     159     3.2     158    11.5     158
      12   157.1    13.1   156.5    13.9   156.5    14.7   156.8    14.7   157.2
    15.3   157.2    15.3   160.2    19.3   160.2    28.3   165.3
#Mann= 3 , 0 , 0
     -10    .035       0       0    .035       0    15.3    .035       0
#XS Ineff= 2 , 0
               0   160.7    15.3           160.2
Permanent Ineff=
       F       F
Bank Sta=0,15.3
XS Rating Curve= 0
Exp/Cntr=.3,.1

Type RM Length L Ch R = 1 ,800.00  ,50,50,50
BEGIN DESCRIPTION:
16
END DESCRIPTION:
#Sta/Elev= 19
   -14.6   166.7    -4.6   166.7     -.6   163.5       0   163.5       0   162.6
       3     161       6   159.4       9   157.8      14   157.8      14   159.7
    14.3   159.7    14.3   157.6    17.5   157.6    17.8   156.9    23.8   156.9
    24.4   157.6    26.8   158.8    29.8   159.4    35.8   160.6
#Mann= 3 , 0 , 0
   -14.6    .035       0    14.3    .035       0    29.8    .035       0
#XS Ineff= 2 , 0
       0    14.3   159.7    29.8       0   159.4
Permanent Ineff=
       F       F
Bank Sta=14.3,29.8
XS Rating Curve= 0
Exp/Cntr=.3,.1

Type RM Length L Ch R = 1 ,750.00  ,9,9,9
BEGIN DESCRIPTION:
15
END DESCRIPTION:
#Sta/Elev= 13
     -10  165.18       0  165.18     1.5  164.18     4.5  159.68       7  158.28
     8.7  157.98       9  157.98       9  156.68      24  155.92    27.7  156.62
    35.7  156.62    38.7  157.42    44.7  159.02
#Mann= 3 , 0 , 0
     -10    .035       0       0    .035       0    38.7    .035       0
#XS Ineff= 2 , 0
               0  165.18    38.7          157.42
Permanent Ineff=
       F       F
Bank Sta=0,38.7
XS Rating Curve= 0
Exp/Cntr=.3,.1

Type RM Length L Ch R = 1 ,741.00  ,41,41,41
BEGIN DESCRIPTION:
14.041
END DESCRIPTION:
#Sta/Elev= 13
     -10  165.07       0  165.07     1.5  164.07     4.5  159.57       7  158.17
     8.7  157.87       9  157.87       9  156.57      24  155.81    27.7  156.51
    35.7  156.51    38.7  157.31    44.7  158.91
#Mann= 3 , 0 , 0
     -10    .035       0       0    .035       0    38.7    .035       0
#XS Ineff= 2 , 0
               0  165.07    38.7          157.31
Permanent Ineff=
       F       F
Bank Sta=0,38.7
XS Rating Curve= 0
Exp/Cntr=.3,.1

Type RM Length L Ch R = 1 ,700.00  ,50,50,50
BEGIN DESCRIPTION:
14
END DESCRIPTION:
#Sta/Elev= 15
     -10   159.6       0   159.6       2   158.6       5   157.1       8   155.6
      11   154.1      14   152.6      15   151.9    19.2   151.9    21.1   152.4
    22.5   153.4    25.5   153.4    28.5   154.9    31.5   156.4    41.5   156.4
#Mann= 3 , 0 , 0
     -10    .035       0       0    .035       0    31.5    .035       0
#XS Ineff= 2 , 0
               0   159.6    31.5           156.4
Permanent Ineff=
       F       F
Bank Sta=0,31.5
XS Rating Curve= 0
Exp/Cntr=.3,.1

Type RM Length L Ch R = 1 ,650.00  ,50,50,50
BEGIN DESCRIPTION:
13
END DESCRIPTION:
#Sta/Elev= 15
     -10  158.08       0  158.08       2  157.08       5  155.58       8  154.08
      11  152.58      14  154.08      15  153.38    19.2  153.38    21.1  153.88
    22.5  154.88    25.5  154.88    28.5  156.38    31.5  157.88    41.5  157.88
#Mann= 3 , 0 , 0
     -10    .035       0       0    .035       0    31.5    .035       0
#XS Ineff= 2 , 0
               0  158.08    31.5          157.88
Permanent Ineff=
       F       F
Bank Sta=0,31.5
XS Rating Curve= 0
Exp/Cntr=.3,.1

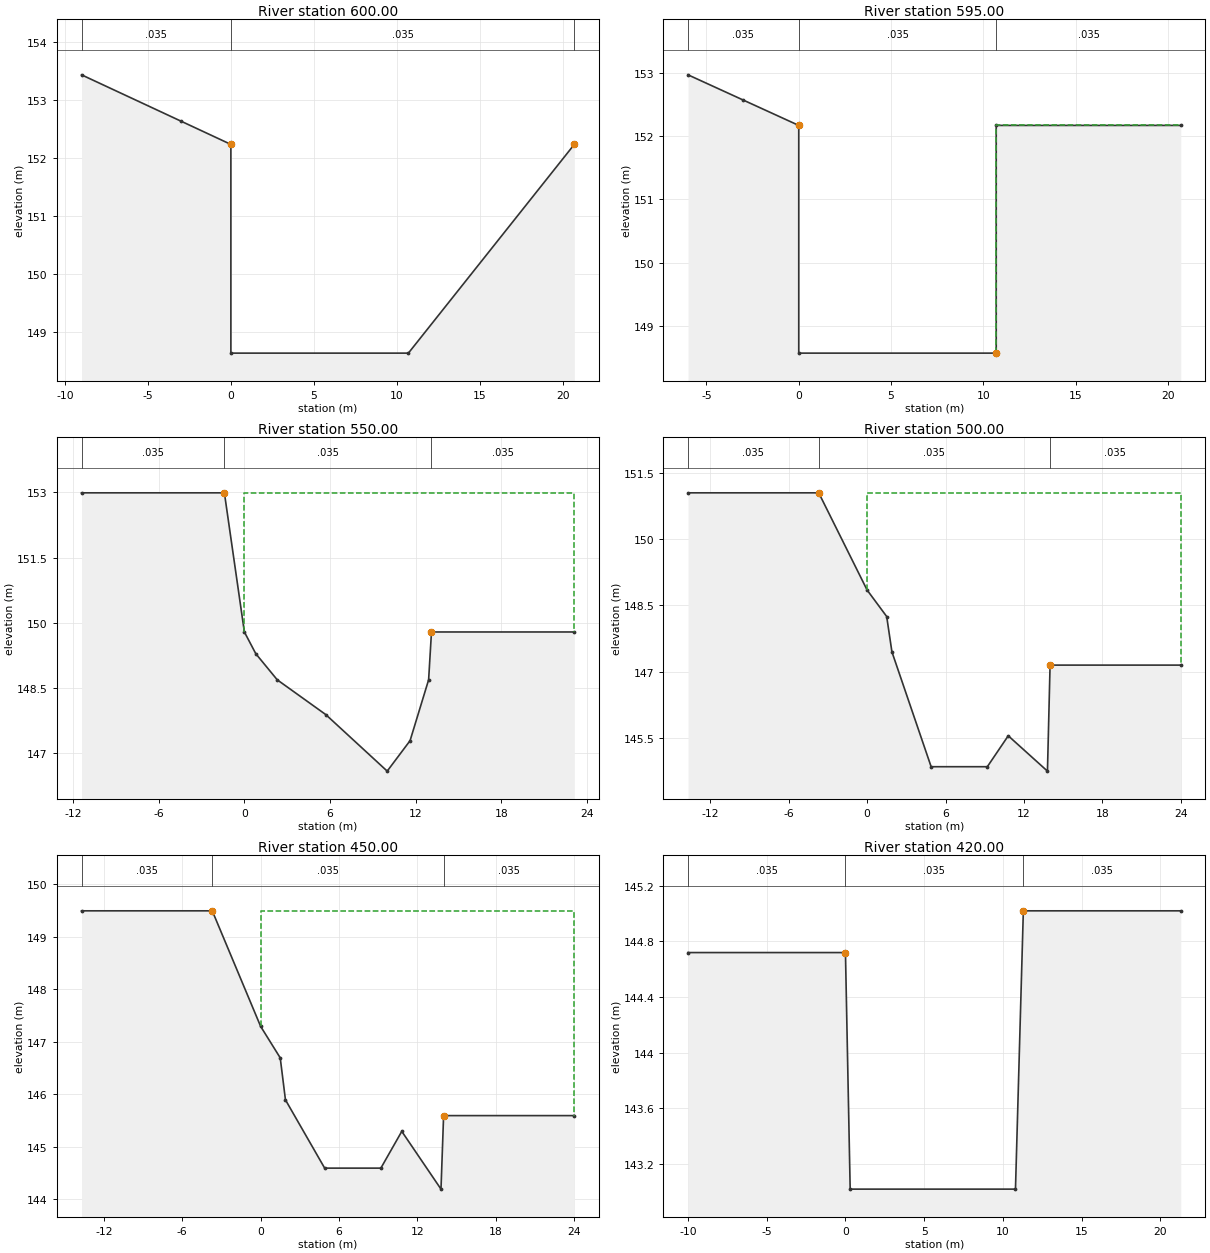
Type RM Length L Ch R = 1 ,600.00  ,5,5,5
BEGIN DESCRIPTION:
12
END DESCRIPTION:
#Sta/Elev= 6
      -9  153.44      -3  152.64       0  152.24       0  148.64    10.7  148.64
    20.7  152.24
#Mann= 3 , 0 , 0
      -9    .035       0       0    .035       0    20.7    .035       0
#XS Ineff= 2 , 0
       0       0  152.24    20.7       0  152.24
Permanent Ineff=
       F       F
Bank Sta=0,20.7
XS Rating Curve= 0
Exp/Cntr=.3,.1

Type RM Length L Ch R = 1 ,595.00  ,45,45,45
BEGIN DESCRIPTION:
11.045
END DESCRIPTION:
#Sta/Elev= 7
      -6  152.97      -3  152.57       0  152.17       0  148.57    10.7  148.57
    10.7  152.17    20.7  152.17
#Mann= 3 , 0 , 0
      -6    .035       0       0    .035       0    10.7    .035       0
#XS Ineff= 2 , 0
               0  152.17    10.7          152.17
Permanent Ineff=
       F       F
Bank Sta=0,10.7
XS Rating Curve= 0
Exp/Cntr=.3,.1

Type RM Length L Ch R = 1 ,550.00  ,50,50,50
BEGIN DESCRIPTION:
11
END DESCRIPTION:
#Sta/Elev= 11
   -11.4  152.99    -1.4  152.99       0  149.79      .8  149.29     2.3  148.69
     5.7  147.89      10  146.59    11.6  147.29    12.9  148.69    13.1  149.79
    23.1  149.79
#Mann= 3 , 0 , 0
   -11.4    .035       0    -1.4    .035       0    13.1    .035       0
#XS Ineff= 2 , 0
       0    -1.4  152.99    13.1       0  149.79
Permanent Ineff=
       F       F
Bank Sta=-1.4,13.1
XS Rating Curve= 0
Exp/Cntr=.3,.1

Type RM Length L Ch R = 1 ,500.00  ,50,50,50
BEGIN DESCRIPTION:
10
END DESCRIPTION:
#Sta/Elev= 11
   -13.7  151.05    -3.7  151.05       0  148.85     1.5  148.25     1.9  147.45
     4.9  144.85     9.2  144.85    10.8  145.55    13.8  144.75      14  147.15
      24  147.15
#Mann= 3 , 0 , 0
   -13.7    .035       0    -3.7    .035       0      14    .035       0
#XS Ineff= 2 , 0
       0    -3.7  151.05      14       0  147.15
Permanent Ineff=
       F       F
Bank Sta=-3.7,14
XS Rating Curve= 0
Exp/Cntr=.3,.1

Type RM Length L Ch R = 1 ,450.00  ,30,30,30
BEGIN DESCRIPTION:
9
END DESCRIPTION:
#Sta/Elev= 11
   -13.7  149.49    -3.7  149.49       0  147.29     1.5  146.69     1.9  145.89
     4.9  144.59     9.2  144.59    10.8  145.29    13.8  144.19      14  145.59
      24  145.59
#Mann= 3 , 0 , 0
   -13.7    .035       0    -3.7    .035       0      14    .035       0
#XS Ineff= 2 , 0
       0    -3.7  149.49      14       0  145.59
Permanent Ineff=
       F       F
Bank Sta=-3.7,14
XS Rating Curve= 0
Exp/Cntr=.3,.1

Type RM Length L Ch R = 1 ,420.00  ,20,20,20
BEGIN DESCRIPTION:
8.02
END DESCRIPTION:
#Sta/Elev= 6
     -10  144.72       0  144.72      .3  143.02    10.8  143.02    11.3  145.02
    21.3  145.02
#Mann= 3 , 0 , 0
     -10    .035       0       0    .035       0    11.3    .035       0
#XS Ineff= 2 , 0
               0  144.72    11.3          145.02
Permanent Ineff=
       F       F
Bank Sta=0,11.3
XS Rating Curve= 0
Exp/Cntr=.3,.1

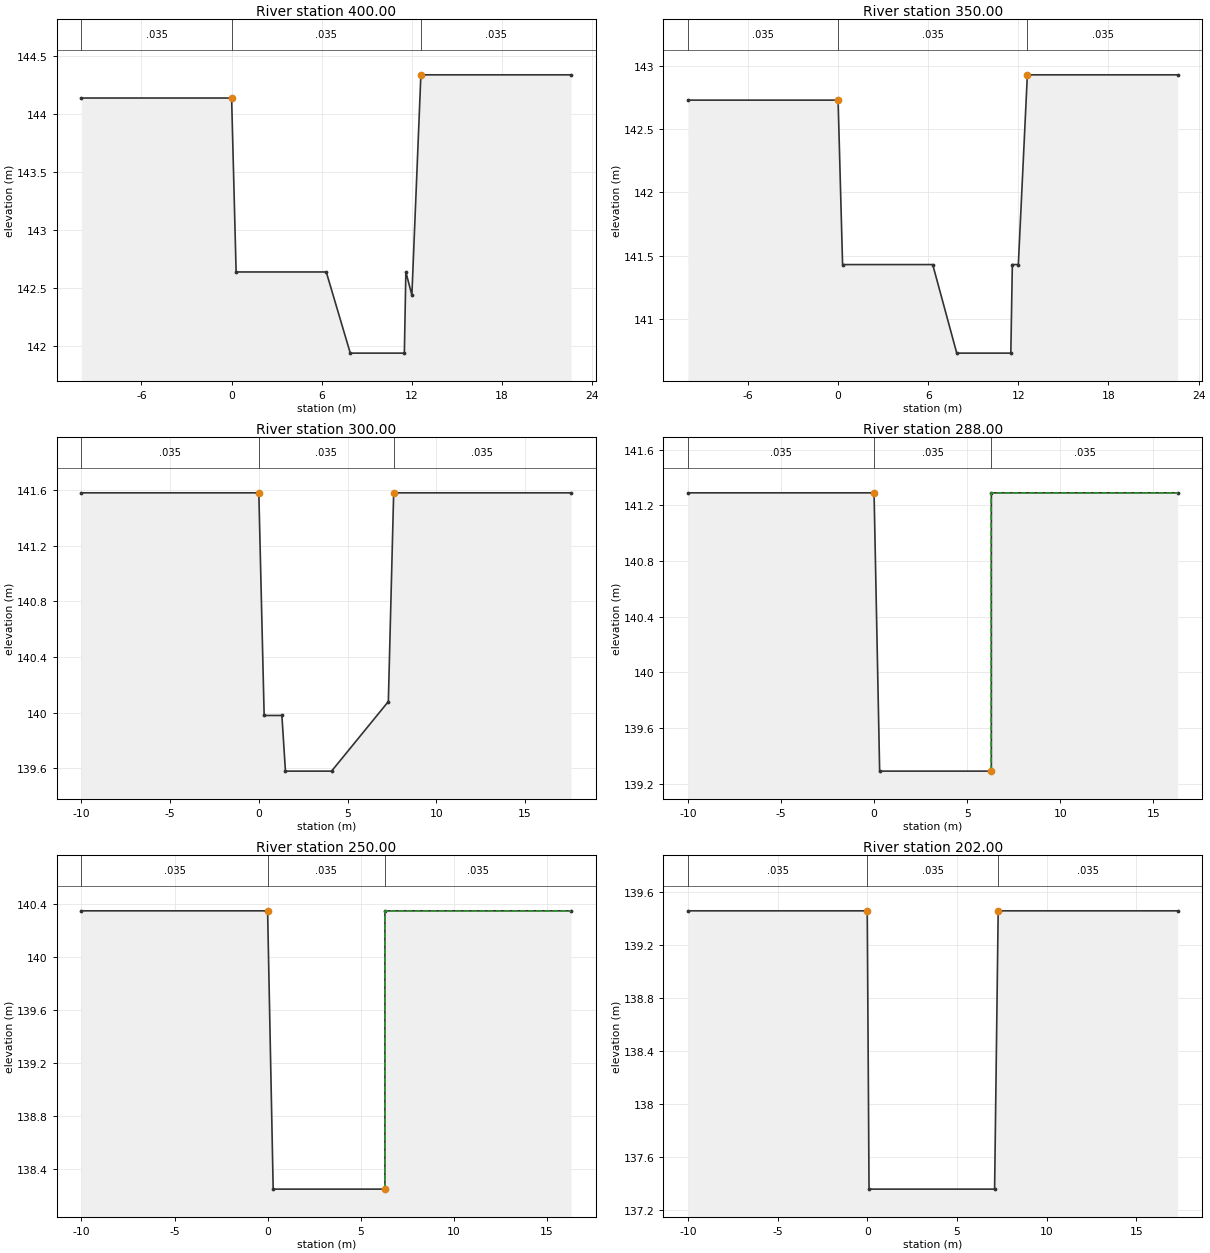
Type RM Length L Ch R = 1 ,400.00  ,50,50,50
BEGIN DESCRIPTION:
8
END DESCRIPTION:
#Sta/Elev= 10
     -10  144.14       0  144.14      .3  142.64     6.3  142.64     7.9  141.94
    11.5  141.94    11.6  142.64      12  142.44    12.6  144.34    22.6  144.34
#Mann= 3 , 0 , 0
     -10    .035       0       0    .035       0    12.6    .035       0
#XS Ineff= 2 , 0
               0  144.14    12.6          144.34
Permanent Ineff=
       F       F
Bank Sta=0,12.6
XS Rating Curve= 0
Exp/Cntr=.3,.1

Type RM Length L Ch R = 1 ,350.00  ,50,50,50
BEGIN DESCRIPTION:
7
END DESCRIPTION:
#Sta/Elev= 10
     -10  142.73       0  142.73      .3  141.43     6.3  141.43     7.9  140.73
    11.5  140.73    11.6  141.43      12  141.43    12.6  142.93    22.6  142.93
#Mann= 3 , 0 , 0
     -10    .035       0       0    .035       0    12.6    .035       0
#XS Ineff= 2 , 0
               0  142.73    12.6          142.93
Permanent Ineff=
       F       F
Bank Sta=0,12.6
XS Rating Curve= 0
Exp/Cntr=.3,.1

Type RM Length L Ch R = 1 ,300.00  ,12,12,12
BEGIN DESCRIPTION:
6
END DESCRIPTION:
#Sta/Elev= 9
     -10  141.58       0  141.58      .3  139.98     1.3  139.98     1.5  139.58
     4.1  139.58     7.3  140.08     7.6  141.58    17.6  141.58
#Mann= 3 , 0 , 0
     -10    .035       0       0    .035       0     7.6    .035       0
#XS Ineff= 2 , 0
               0  141.58     7.6          141.58
Permanent Ineff=
       F       F
Bank Sta=0,7.6
XS Rating Curve= 0
Exp/Cntr=.3,.1

Type RM Length L Ch R = 1 ,288.00  ,38,38,38
BEGIN DESCRIPTION:
5.038
END DESCRIPTION:
#Sta/Elev= 6
     -10  141.29       0  141.29      .3  139.29     6.3  139.29     6.3  141.29
    16.3  141.29
#Mann= 3 , 0 , 0
     -10    .035       0       0    .035       0     6.3    .035       0
#XS Ineff= 2 , 0
               0  141.29     6.3          141.29
Permanent Ineff=
       F       F
Bank Sta=0,6.3
XS Rating Curve= 0
Exp/Cntr=.3,.1

Type RM Length L Ch R = 1 ,250.00  ,48,48,48
BEGIN DESCRIPTION:
5
END DESCRIPTION:
#Sta/Elev= 6
     -10  140.35       0  140.35      .3  138.25     6.3  138.25     6.3  140.35
    16.3  140.35
#Mann= 3 , 0 , 0
     -10    .035       0       0    .035       0     6.3    .035       0
#XS Ineff= 2 , 0
               0  140.35     6.3          140.35
Permanent Ineff=
       F       F
Bank Sta=0,6.3
XS Rating Curve= 0
Exp/Cntr=.3,.1

Type RM Length L Ch R = 1 ,202.00  ,54,54,54
BEGIN DESCRIPTION:
4.002
END DESCRIPTION:
#Sta/Elev= 6
     -10  139.46       0  139.46      .1  137.36     7.1  137.36     7.3  139.46
    17.3  139.46
#Mann= 3 , 0 , 0
     -10    .035       0       0    .035       0     7.3    .035       0
#XS Ineff= 2 , 0
               0  139.46     7.3          139.46
Permanent Ineff=
       F       F
Bank Sta=0,7.3
XS Rating Curve= 0
Exp/Cntr=.3,.1

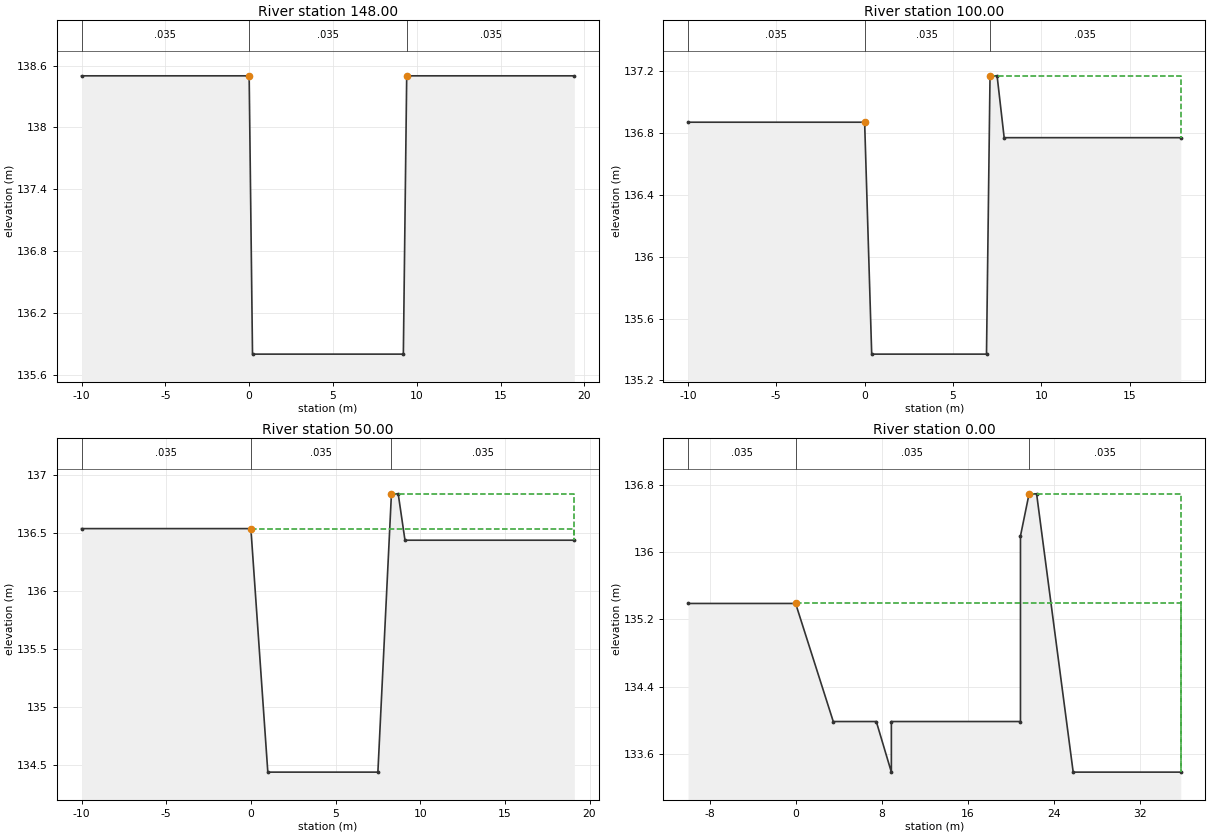
Type RM Length L Ch R = 1 ,148.00  ,48,48,48
BEGIN DESCRIPTION:
2.048
END DESCRIPTION:
#Sta/Elev= 6
     -10   138.5       0   138.5      .2   135.8     9.2   135.8     9.4   138.5
    19.4   138.5
#Mann= 3 , 0 , 0
     -10    .035       0       0    .035       0     9.4    .035       0
#XS Ineff= 2 , 0
               0   138.5     9.4           138.5
Permanent Ineff=
       F       F
Bank Sta=0,9.4
XS Rating Curve= 0
Exp/Cntr=.3,.1

Type RM Length L Ch R = 1 ,100.00  ,50,50,50
BEGIN DESCRIPTION:
2
END DESCRIPTION:
#Sta/Elev= 8
     -10  136.87       0  136.87      .4  135.37     6.9  135.37     7.1  137.17
     7.5  137.17     7.9  136.77    17.9  136.77
#Mann= 3 , 0 , 0
     -10    .035       0       0    .035       0     7.1    .035       0
#XS Ineff= 2 , 0
               0  136.87     7.1          137.17
Permanent Ineff=
       F       F
Bank Sta=0,7.1
XS Rating Curve= 0
Exp/Cntr=.3,.1

Type RM Length L Ch R = 1 ,50.00   ,50,50,50
BEGIN DESCRIPTION:
1
END DESCRIPTION:
#Sta/Elev= 8
     -10  136.54       0  136.54       1  134.44     7.5  134.44     8.3  136.84
     8.7  136.84     9.1  136.44    19.1  136.44
#Mann= 3 , 0 , 0
     -10    .035       0       0    .035       0     8.3    .035       0
#XS Ineff= 2 , 0
       0       0  136.54     8.3       0  136.84
Permanent Ineff=
       F       F
Bank Sta=0,8.3
XS Rating Curve= 0
Exp/Cntr=.3,.1

Type RM Length L Ch R = 1 ,0.00    ,0,0,0
BEGIN DESCRIPTION:
0
END DESCRIPTION:
#Sta/Elev= 12
     -10  135.39       0  135.39     3.5  133.99     7.5  133.99     8.9  133.39
     8.9  133.99    20.9  133.99    20.9  136.19    21.7  136.69    22.4  136.69
    25.8  133.39    35.8  133.39
#Mann= 3 , 0 , 0
     -10    .035       0       0    .035       0    21.7    .035       0
#XS Ineff= 2 , 0
       0       0  135.39    21.7       0  136.69
Permanent Ineff=
       F       F
Bank Sta=0,21.7
XS Rating Curve= 0
Exp/Cntr=.3,.1

Chan Stop Cuts=-1