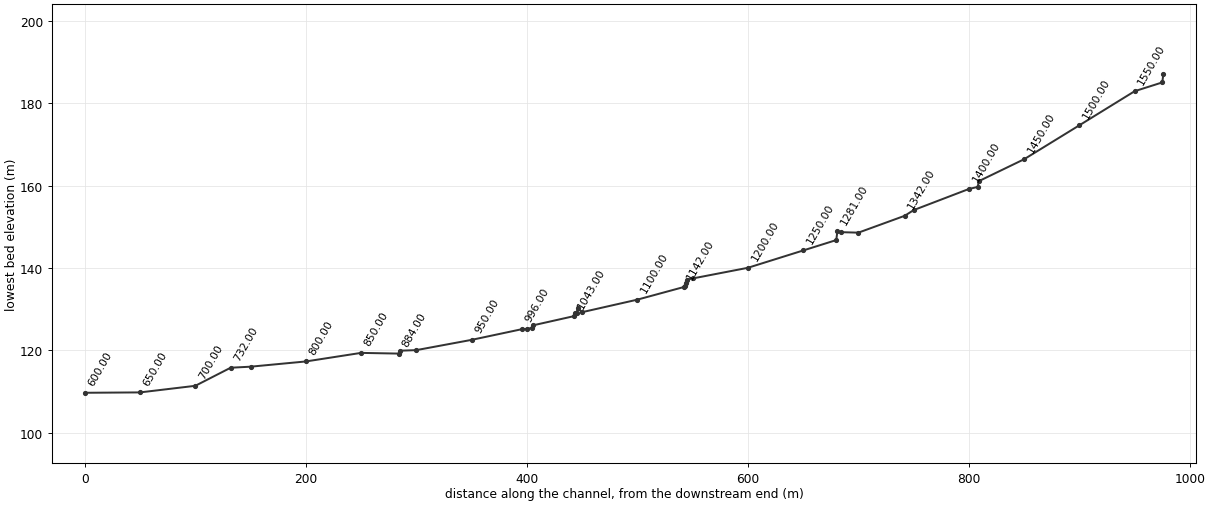
--- DHC.prj (project) ---

Proj Title=daehan-ch
Current Plan=p01
Default Exp/Contr=.3,.1
SI Units
Geom File=g01
Flow File=f01
Plan File=p01
Y Axis Title=Elevation
X Axis Title(PF)=Main Channel Distance
X Axis Title(XS)=Station
BEGIN DESCRIPTION:
           BACK WATER COMPUTATION
      APPLICATION OF HEC-2 BY Samju Construction Engineering
      deahan-ch: 10,20,30,50,80 yr
END DESCRIPTION:
DSS Export Rating Curves= 0
DSS Export Rating Curve Sorted= 0
DSS Export Volume Flow Curves= 0
DXF OffsetX= 0
DXF OffsetY= 0
DXF ScaleX= 1
DXF ScaleY= 10

--- DHC.p01 (plan) ---

Plan Title=Imported Plan 01
Version=Version 3.0.1  Mar 2001
Short Identifier=Imported Pla
Geom File=g01
Flow File=f01
Subcritical Flow
K Sum by GR= 0
Std Step Tol= 0.003
Critical Tol= 0.003
Num of Std Step Trials= 20
Max Error Tol= 0.1
Flow Tol Ratio= 0.001
Split Flow NTrial= 30
Split Flow Tol= 0.02
Split Flow Ratio= 0.02
Log Output Level= 0
Friction Slope Method= 1
Unsteady Friction Slope Method= 2
Parabolic Critical Depth
Global Vel Dist= 0 , 0 , 0
Global Log Level= 0
CheckData=True
Encroach Param=-1 ,0,0, 0
Computation Interval=1HOUR
Output Interval=1HOUR
Run HTab= 0
Run UNet= 0
Run PostProcess= 0
UNET Theta= 1
UNET ZTol= 0.02
UNET ZSATol= 0.1
UNET MxIter= 20
UNET MaxInSteps= 20
UNET DtIC= 0
UNET DtMin= 0
UNET MaxCRTS= 20
UNET WFStab= 2
UNET SFStab= 1
UNET WFX= 1
UNET SFX= 1
UNET Convert EG Bridges=-1
UNET Use Existing IB Tables=-1
Instantaneous Interval=1HOUR
Write IC File= 0
Write Velocity= 0
Write Detailed= 0

--- DHC.f01 (steady flow) ---

Flow Title=Imported Flow 01
Version=Version 3.0.1  Mar 2001
Number of Profiles= 5
Profile Names=10YR,20YR,30YR,50YR,80YR
River Rch & RM=RIVER-1,Reach-1         ,1576.00
   14.53   16.01   16.87   17.96   18.96
River Rch & RM=RIVER-1,Reach-1         ,850.00
   20.26   22.32   23.53   25.05   26.45
Boundary for River Rch & Prof#=RIVER-1,Reach-1         , 1
Up Type= 0
Dn Type= 3
Dn Slope=.044
Boundary for River Rch & Prof#=RIVER-1,Reach-1         , 2
Up Type= 0
Dn Type= 3
Dn Slope=.044
Boundary for River Rch & Prof#=RIVER-1,Reach-1         , 3
Up Type= 0
Dn Type= 3
Dn Slope=.044
Boundary for River Rch & Prof#=RIVER-1,Reach-1         , 4
Up Type= 0
Dn Type= 3
Dn Slope=.044
Boundary for River Rch & Prof#=RIVER-1,Reach-1         , 5
Up Type= 0
Dn Type= 3
Dn Slope=.044
DSS Import GetInterval= 0
DSS Import GetPeak= 0
DSS Import FillOption= 0

--- DHC.g01 (geometry) ---

Geom Title=Imported Geom 01
Version=Version 3.0.1  Mar 2001

River Reach=RIVER-1         ,Reach-1
Reach XY= 2
              .5             .95              .5             .05

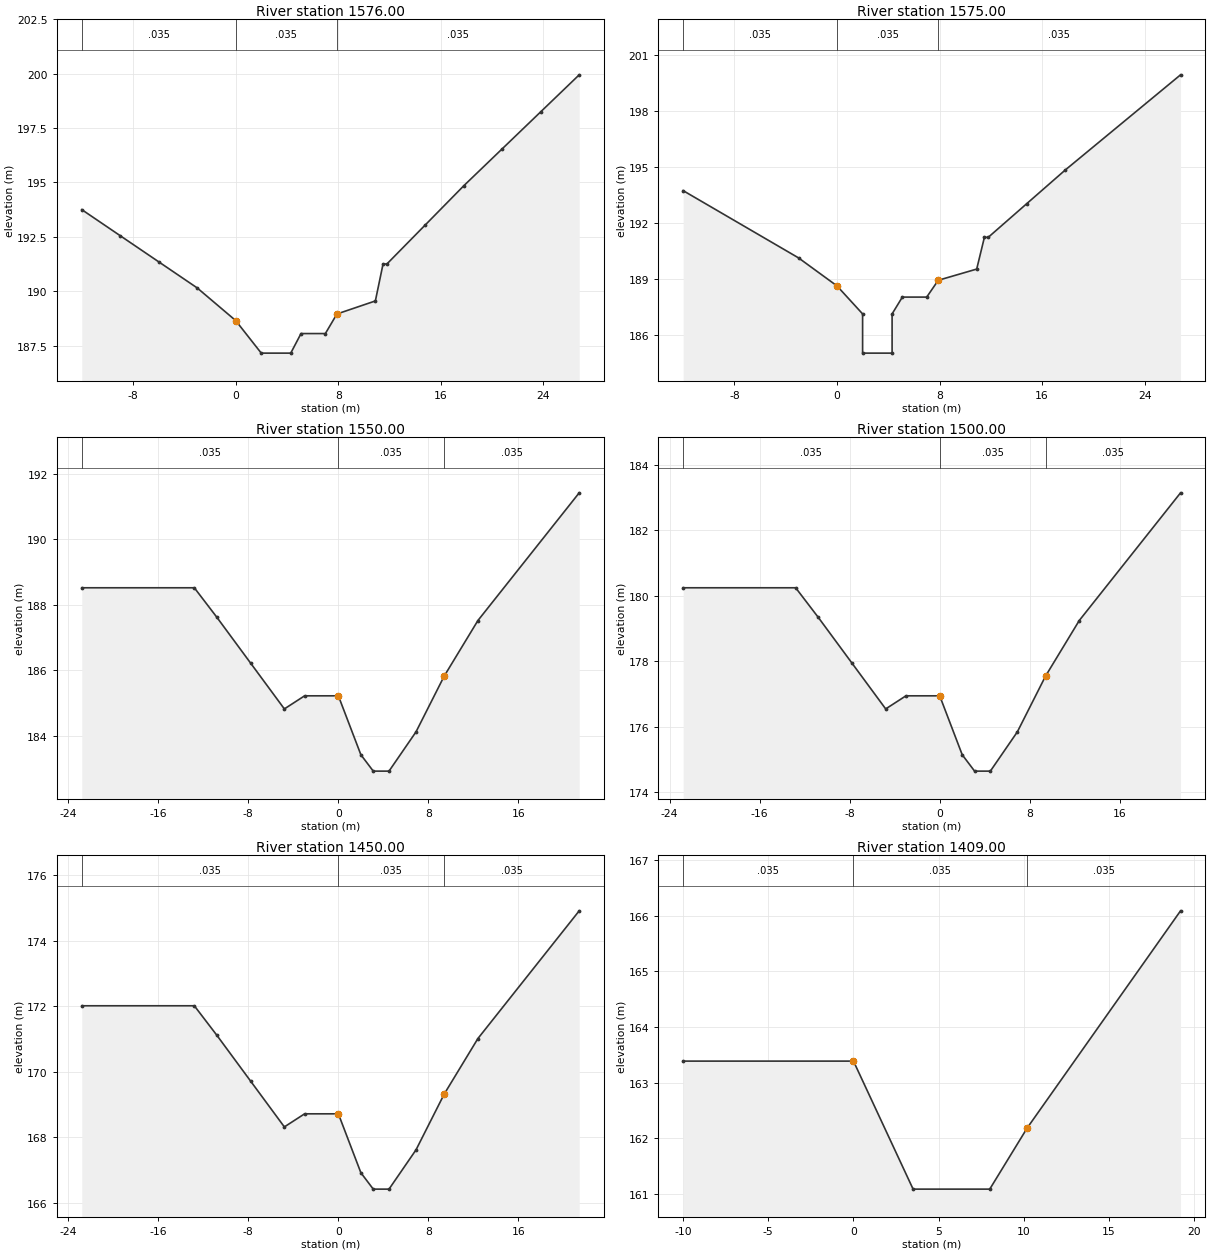
Type RM Length L Ch R = 1 ,1576.00 ,1,1,1
BEGIN DESCRIPTION:
31.026
END DESCRIPTION:
#Sta/Elev= 18
     -12  193.75      -9  192.55      -6  191.35      -3  190.15       0  188.65
       2  187.15     4.3  187.15     5.1  188.05       7  188.05     7.9  188.95
    10.9  189.55    11.5  191.25    11.8  191.25    14.8  193.05    17.8  194.85
    20.8  196.55    23.8  198.25    26.8  199.95
#Mann= 3 , 0 , 0
     -12    .035       0       0    .035       0     7.9    .035       0
#XS Ineff= 2 , 0
               0  188.65     7.9          188.95
Permanent Ineff=
       F       F
Bank Sta=0,7.9
XS Rating Curve= 0
Exp/Cntr=.3,.1

Type RM Length L Ch R = 1 ,1575.00 ,25,25,25
BEGIN DESCRIPTION:
31.025
END DESCRIPTION:
#Sta/Elev= 16
     -12  193.75      -3  190.15       0  188.65       2  187.15       2  185.05
     4.3  185.05     4.3  187.15     5.1  188.05       7  188.05     7.9  188.95
    10.9  189.55    11.5  191.25    11.8  191.25    14.8  193.05    17.8  194.85
    26.8  199.95
#Mann= 3 , 0 , 0
     -12    .035       0       0    .035       0     7.9    .035       0
#XS Ineff= 2 , 0
               0  188.65     7.9          188.95
Permanent Ineff=
       F       F
Bank Sta=0,7.9
XS Rating Curve= 0
Exp/Cntr=.3,.1

Type RM Length L Ch R = 1 ,1550.00 ,50,50,50
BEGIN DESCRIPTION:
31
END DESCRIPTION:
#Sta/Elev= 14
   -22.8  188.52   -12.8  188.52   -10.8  187.62    -7.8  186.22    -4.8  184.82
      -3  185.22       0  185.22       2  183.42     3.1  182.92     4.5  182.92
     6.9  184.12     9.4  185.82    12.4  187.52    21.4  191.42
#Mann= 3 , 0 , 0
   -22.8    .035       0       0    .035       0     9.4    .035       0
#XS Ineff= 2 , 0
               0  185.22     9.4          185.82
Permanent Ineff=
       F       F
Bank Sta=0,9.4
XS Rating Curve= 0
Exp/Cntr=.3,.1

Type RM Length L Ch R = 1 ,1500.00 ,50,50,50
BEGIN DESCRIPTION:
30
END DESCRIPTION:
#Sta/Elev= 14
   -22.8  180.25   -12.8  180.25   -10.8  179.35    -7.8  177.95    -4.8  176.55
      -3  176.95       0  176.95       2  175.15     3.1  174.65     4.5  174.65
     6.9  175.85     9.4  177.55    12.4  179.25    21.4  183.15
#Mann= 3 , 0 , 0
   -22.8    .035       0       0    .035       0     9.4    .035       0
#XS Ineff= 2 , 0
               0  176.95     9.4          177.55
Permanent Ineff=
       F       F
Bank Sta=0,9.4
XS Rating Curve= 0
Exp/Cntr=.3,.1

Type RM Length L Ch R = 1 ,1450.00 ,41,41,41
BEGIN DESCRIPTION:
29
END DESCRIPTION:
#Sta/Elev= 14
   -22.8  172.01   -12.8  172.01   -10.8  171.11    -7.8  169.71    -4.8  168.31
      -3  168.71       0  168.71       2  166.91     3.1  166.41     4.5  166.41
     6.9  167.61     9.4  169.31    12.4  171.01    21.4  174.91
#Mann= 3 , 0 , 0
   -22.8    .035       0       0    .035       0     9.4    .035       0
#XS Ineff= 2 , 0
               0  168.71     9.4          169.31
Permanent Ineff=
       F       F
Bank Sta=0,9.4
XS Rating Curve= 0
Exp/Cntr=.3,.1

Type RM Length L Ch R = 1 ,1409.00 ,1,1,1
BEGIN DESCRIPTION:
28.009
END DESCRIPTION:
#Sta/Elev= 6
     -10  163.39       0  163.39     3.5  161.09       8  161.09    10.2  162.19
    19.2  166.09
#Mann= 3 , 0 , 0
     -10    .035       0       0    .035       0    10.2    .035       0
#XS Ineff= 2 , 0
               0  163.39    10.2          162.19
Permanent Ineff=
       F       F
Bank Sta=0,10.2
XS Rating Curve= 0
Exp/Cntr=.3,.1

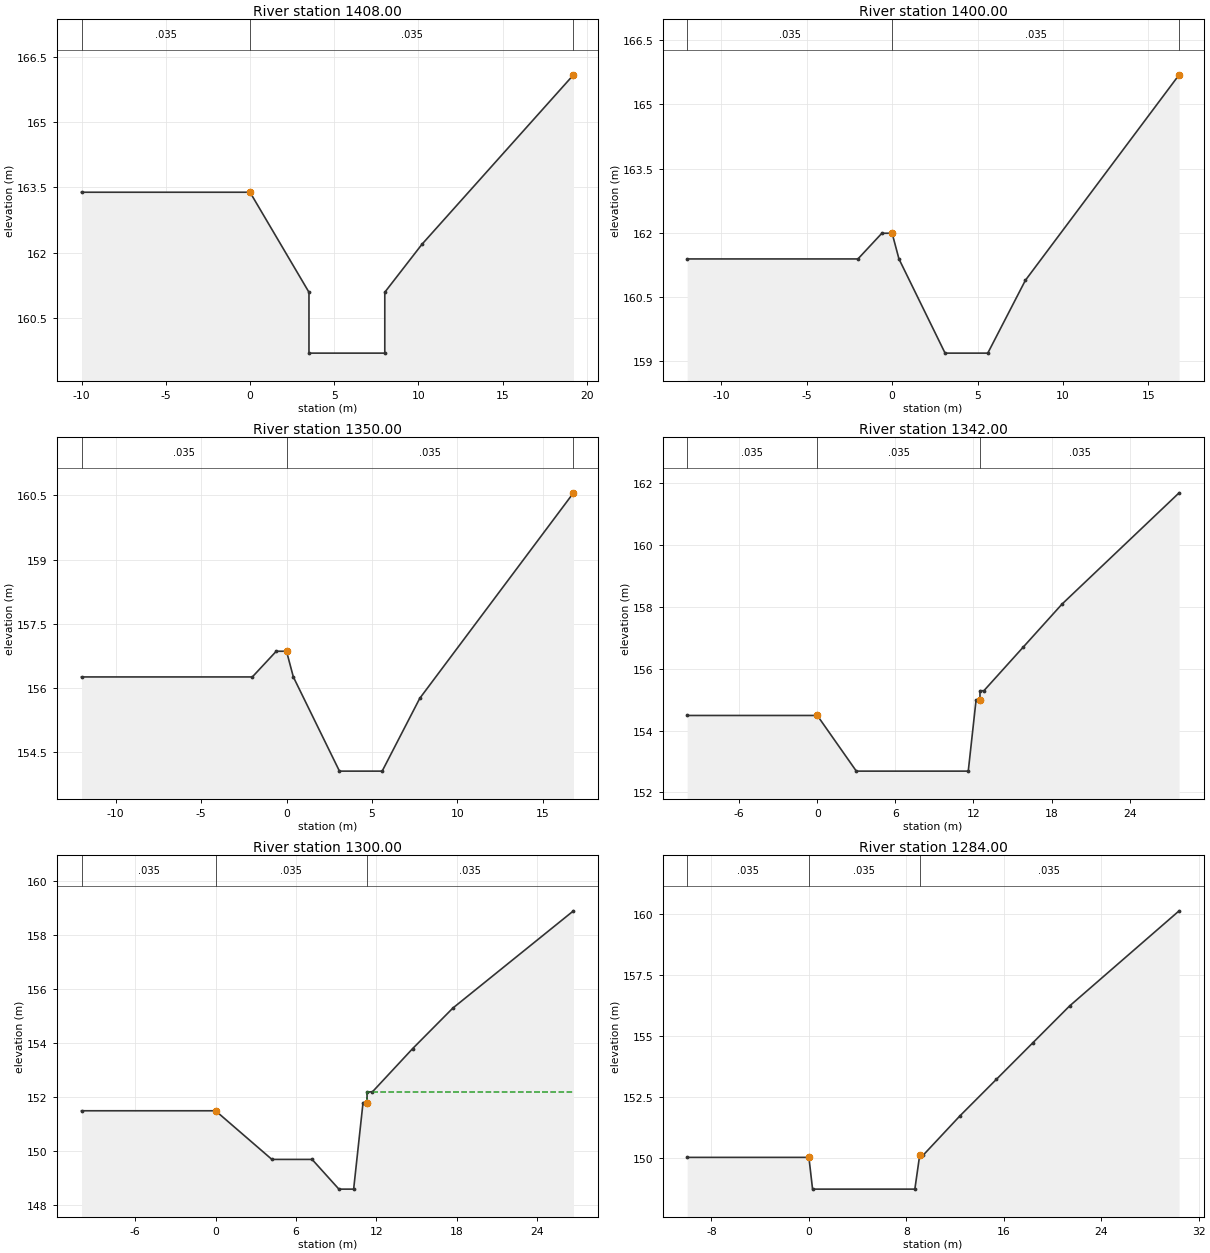
Type RM Length L Ch R = 1 ,1408.00 ,8,8,8
BEGIN DESCRIPTION:
28.008
END DESCRIPTION:
#Sta/Elev= 8
     -10  163.39       0  163.39     3.5  161.09     3.5  159.69       8  159.69
       8  161.09    10.2  162.19    19.2  166.09
#Mann= 3 , 0 , 0
     -10    .035       0       0    .035       0    19.2    .035       0
#XS Ineff= 2 , 0
       0       0  163.39    19.2       0  166.09
Permanent Ineff=
       F       F
Bank Sta=0,19.2
XS Rating Curve= 0
Exp/Cntr=.3,.1

Type RM Length L Ch R = 1 ,1400.00 ,50,50,50
BEGIN DESCRIPTION:
28
END DESCRIPTION:
#Sta/Elev= 9
     -12  161.39      -2  161.39     -.6  161.99       0  161.99      .4  161.39
     3.1  159.19     5.6  159.19     7.8  160.89    16.8  165.69
#Mann= 3 , 0 , 0
     -12    .035       0       0    .035       0    16.8    .035       0
#XS Ineff= 2 , 0
       0       0  161.99    16.8       0  165.69
Permanent Ineff=
       F       F
Bank Sta=0,16.8
XS Rating Curve= 0
Exp/Cntr=.3,.1

Type RM Length L Ch R = 1 ,1350.00 ,8,8,8
BEGIN DESCRIPTION:
27
END DESCRIPTION:
#Sta/Elev= 9
     -12  156.26      -2  156.26     -.6  156.86       0  156.86      .4  156.26
     3.1  154.06     5.6  154.06     7.8  155.76    16.8  160.56
#Mann= 3 , 0 , 0
     -12    .035       0       0    .035       0    16.8    .035       0
#XS Ineff= 2 , 0
       0       0  156.86    16.8       0  160.56
Permanent Ineff=
       F       F
Bank Sta=0,16.8
XS Rating Curve= 0
Exp/Cntr=.3,.1

Type RM Length L Ch R = 1 ,1342.00 ,42,42,42
BEGIN DESCRIPTION:
26.042
END DESCRIPTION:
#Sta/Elev= 11
     -10  154.49       0  154.49       3  152.69    11.6  152.69    12.2  154.99
    12.5  154.99    12.5  155.29    12.8  155.29    15.8  156.69    18.8  158.09
    27.8  161.69
#Mann= 3 , 0 , 0
     -10    .035       0       0    .035       0    12.5    .035       0
Bank Sta=0,12.5
XS Rating Curve= 0
Exp/Cntr=.3,.1

Type RM Length L Ch R = 1 ,1300.00 ,16,16,16
BEGIN DESCRIPTION:
26
END DESCRIPTION:
#Sta/Elev= 13
     -10  151.49       0  151.49     4.2  149.69     7.2  149.69     9.2  148.59
    10.3  148.59      11  151.79    11.3  151.79    11.3  152.19    11.7  152.19
    14.7  153.79    17.7  155.29    26.7  158.89
#Mann= 3 , 0 , 0
     -10    .035       0       0    .035       0    11.3    .035       0
#XS Ineff= 2 , 0
               0  151.49    11.3          152.19
Permanent Ineff=
       F       F
Bank Sta=0,11.3
XS Rating Curve= 0
Exp/Cntr=.3,.1

Type RM Length L Ch R = 1 ,1284.00 ,3,3,3
BEGIN DESCRIPTION:
25.034
END DESCRIPTION:
#Sta/Elev= 11
     -10  150.01       0  150.01      .3  148.71     8.7  148.71     9.1  150.11
     9.4  150.11    12.4  151.71    15.4  153.21    18.4  154.71    21.4  156.21
    30.4  160.11
#Mann= 3 , 0 , 0
     -10    .035       0       0    .035       0     9.1    .035       0
#XS Ineff= 2 , 0
               0  150.01     9.1          150.11
Permanent Ineff=
       F       F
Bank Sta=0,9.1
XS Rating Curve= 0
Exp/Cntr=.3,.1

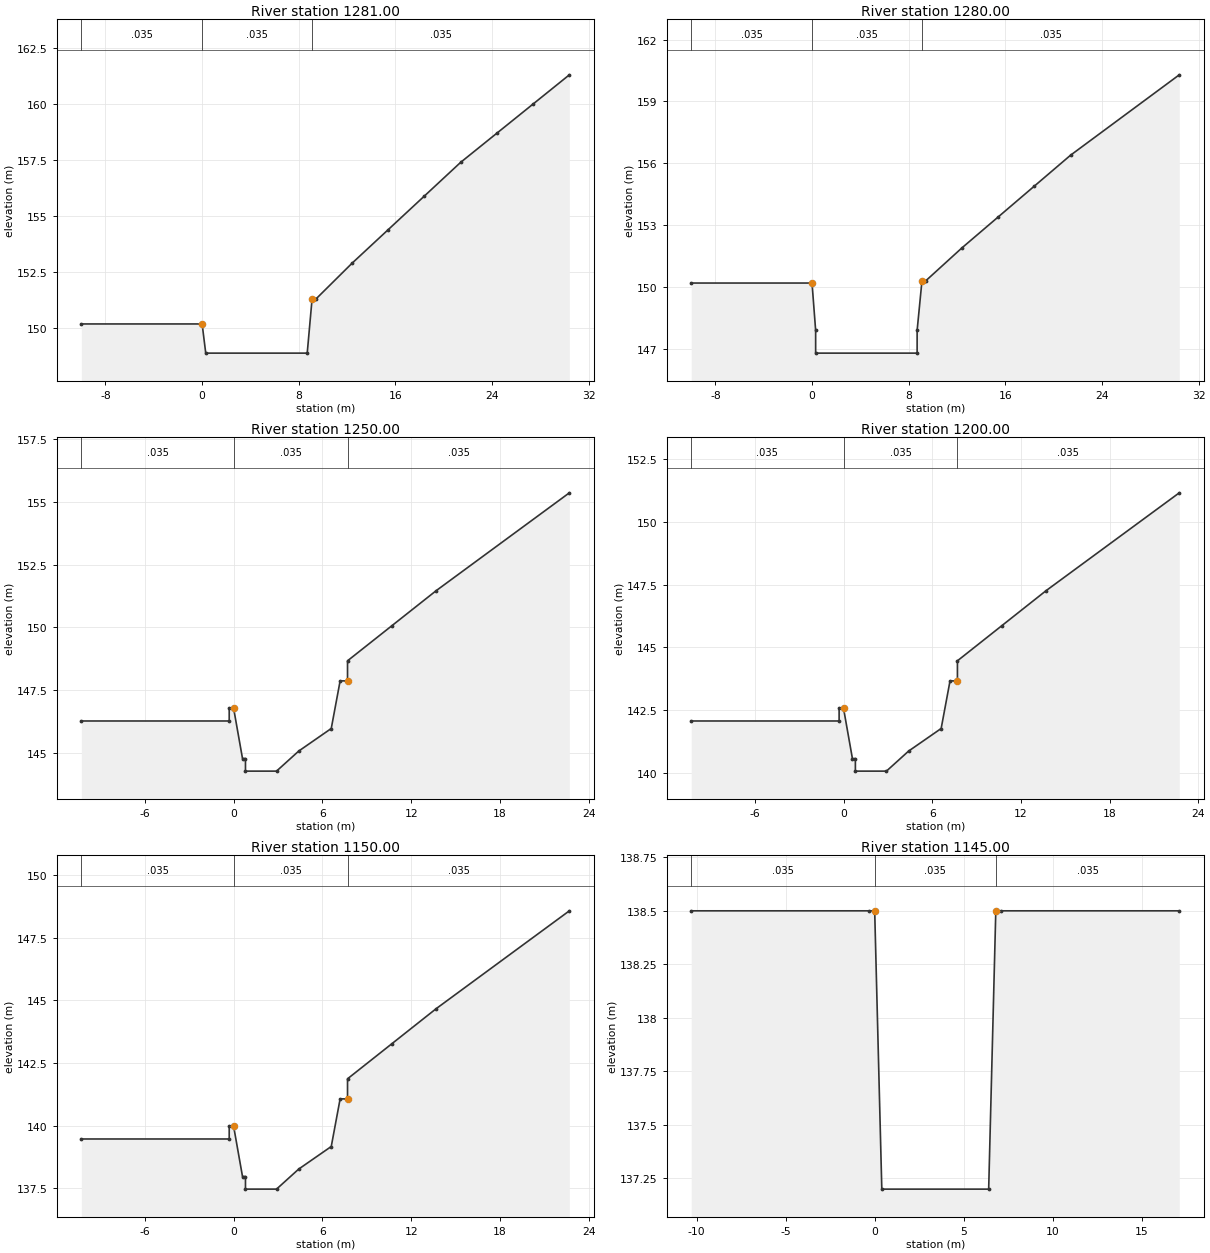
Type RM Length L Ch R = 1 ,1281.00 ,1,1,1
BEGIN DESCRIPTION:
25.031
END DESCRIPTION:
#Sta/Elev= 13
     -10  150.19       0  150.19      .3  148.89     8.7  148.89     9.1  151.29
     9.4  151.29    12.4  152.89    15.4  154.39    18.4  155.89    21.4  157.39
    24.4  158.69    27.4  159.99    30.4  161.29
#Mann= 3 , 0 , 0
     -10    .035       0       0    .035       0     9.1    .035       0
#XS Ineff= 2 , 0
               0  150.19     9.1          151.29
Permanent Ineff=
       F       F
Bank Sta=0,9.1
XS Rating Curve= 0
Exp/Cntr=.3,.1

Type RM Length L Ch R = 1 ,1280.00 ,30,30,30
BEGIN DESCRIPTION:
25.03
END DESCRIPTION:
#Sta/Elev= 13
     -10  150.19       0  150.19      .3  147.89      .3  146.79     8.7  146.79
     8.7  147.89     9.1  150.29     9.4  150.29    12.4  151.89    15.4  153.39
    18.4  154.89    21.4  156.39    30.4  160.29
#Mann= 3 , 0 , 0
     -10    .035       0       0    .035       0     9.1    .035       0
#XS Ineff= 2 , 0
               0  150.19     9.1          150.29
Permanent Ineff=
       F       F
Bank Sta=0,9.1
XS Rating Curve= 0
Exp/Cntr=.3,.1

Type RM Length L Ch R = 1 ,1250.00 ,50,50,50
BEGIN DESCRIPTION:
25
END DESCRIPTION:
#Sta/Elev= 16
   -10.3  146.26     -.3  146.26     -.3  146.76       0  146.76      .6  144.76
      .8  144.76      .8  144.26     2.9  144.26     4.4  145.06     6.6  145.96
     7.2  147.86     7.7  147.86     7.7  148.66    10.7  150.06    13.7  151.46
    22.7  155.36
#Mann= 3 , 0 , 0
   -10.3    .035       0       0    .035       0     7.7    .035       0
Bank Sta=0,7.7
XS Rating Curve= 0
Exp/Cntr=.3,.1

Type RM Length L Ch R = 1 ,1200.00 ,50,50,50
BEGIN DESCRIPTION:
24
END DESCRIPTION:
#Sta/Elev= 16
   -10.3  142.06     -.3  142.06     -.3  142.56       0  142.56      .6  140.56
      .8  140.56      .8  140.06     2.9  140.06     4.4  140.86     6.6  141.76
     7.2  143.66     7.7  143.66     7.7  144.46    10.7  145.86    13.7  147.26
    22.7  151.16
#Mann= 3 , 0 , 0
   -10.3    .035       0       0    .035       0     7.7    .035       0
Bank Sta=0,7.7
XS Rating Curve= 0
Exp/Cntr=.3,.1

Type RM Length L Ch R = 1 ,1150.00 ,5,5,5
BEGIN DESCRIPTION:
23
END DESCRIPTION:
#Sta/Elev= 16
   -10.3  139.47     -.3  139.47     -.3  139.97       0  139.97      .6  137.97
      .8  137.97      .8  137.47     2.9  137.47     4.4  138.27     6.6  139.17
     7.2  141.07     7.7  141.07     7.7  141.87    10.7  143.27    13.7  144.67
    22.7  148.57
#Mann= 3 , 0 , 0
   -10.3    .035       0       0    .035       0     7.7    .035       0
Bank Sta=0,7.7
XS Rating Curve= 0
Exp/Cntr=.3,.1

Type RM Length L Ch R = 1 ,1145.00 ,1,1,1
BEGIN DESCRIPTION:
22.045
END DESCRIPTION:
#Sta/Elev= 8
   -10.3   138.5     -.3   138.5       0   138.5      .4   137.2     6.4   137.2
     6.8   138.5     7.1   138.5    17.1   138.5
#Mann= 3 , 0 , 0
   -10.3    .035       0       0    .035       0     6.8    .035       0
#XS Ineff= 2 , 0
               0   138.5     6.8           138.5
Permanent Ineff=
       F       F
Bank Sta=0,6.8
XS Rating Curve= 0
Exp/Cntr=.3,.1

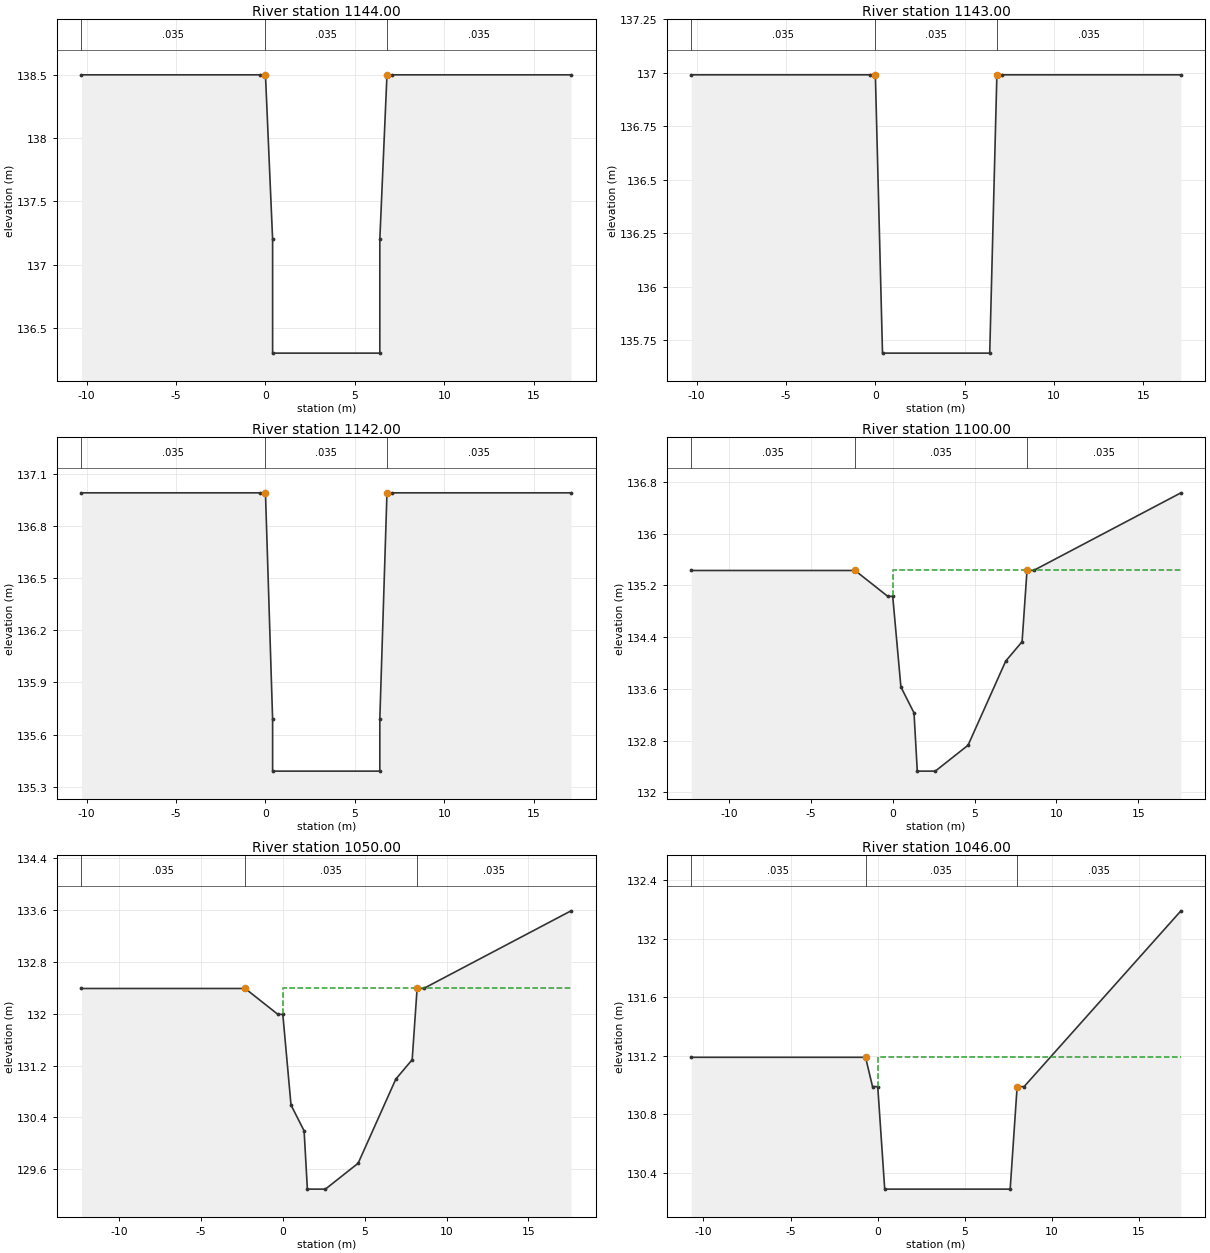
Type RM Length L Ch R = 1 ,1144.00 ,1,1,1
BEGIN DESCRIPTION:
22.044
END DESCRIPTION:
#Sta/Elev= 10
   -10.3   138.5     -.3   138.5       0   138.5      .4   137.2      .4   136.3
     6.4   136.3     6.4   137.2     6.8   138.5     7.1   138.5    17.1   138.5
#Mann= 3 , 0 , 0
   -10.3    .035       0       0    .035       0     6.8    .035       0
#XS Ineff= 2 , 0
               0   138.5     6.8           138.5
Permanent Ineff=
       F       F
Bank Sta=0,6.8
XS Rating Curve= 0
Exp/Cntr=.3,.1

Type RM Length L Ch R = 1 ,1143.00 ,1,1,1
BEGIN DESCRIPTION:
22.043
END DESCRIPTION:
#Sta/Elev= 8
   -10.3  136.99     -.3  136.99       0  136.99      .4  135.69     6.4  135.69
     6.8  136.99     7.1  136.99    17.1  136.99
#Mann= 3 , 0 , 0
   -10.3    .035       0       0    .035       0     6.8    .035       0
#XS Ineff= 2 , 0
               0  136.99     6.8          136.99
Permanent Ineff=
       F       F
Bank Sta=0,6.8
XS Rating Curve= 0
Exp/Cntr=.3,.1

Type RM Length L Ch R = 1 ,1142.00 ,42,42,42
BEGIN DESCRIPTION:
22.042
END DESCRIPTION:
#Sta/Elev= 10
   -10.3  136.99     -.3  136.99       0  136.99      .4  135.69      .4  135.39
     6.4  135.39     6.4  135.69     6.8  136.99     7.1  136.99    17.1  136.99
#Mann= 3 , 0 , 0
   -10.3    .035       0       0    .035       0     6.8    .035       0
#XS Ineff= 2 , 0
               0  136.99     6.8          136.99
Permanent Ineff=
       F       F
Bank Sta=0,6.8
XS Rating Curve= 0
Exp/Cntr=.3,.1

Type RM Length L Ch R = 1 ,1100.00 ,50,50,50
BEGIN DESCRIPTION:
22
END DESCRIPTION:
#Sta/Elev= 14
   -12.3  135.43    -2.3  135.43     -.3  135.03       0  135.03      .5  133.63
     1.3  133.23     1.5  132.33     2.6  132.33     4.6  132.73     6.9  134.03
     7.9  134.33     8.2  135.43     8.6  135.43    17.6  136.63
#Mann= 3 , 0 , 0
   -12.3    .035       0    -2.3    .035       0     8.2    .035       0
#XS Ineff= 2 , 0
       0    -2.3  135.43     8.2       0  135.43
Permanent Ineff=
       F       F
Bank Sta=-2.3,8.2
XS Rating Curve= 0
Exp/Cntr=.3,.1

Type RM Length L Ch R = 1 ,1050.00 ,4,4,4
BEGIN DESCRIPTION:
21
END DESCRIPTION:
#Sta/Elev= 14
   -12.3  132.39    -2.3  132.39     -.3  131.99       0  131.99      .5  130.59
     1.3  130.19     1.5  129.29     2.6  129.29     4.6  129.69     6.9  130.99
     7.9  131.29     8.2  132.39     8.6  132.39    17.6  133.59
#Mann= 3 , 0 , 0
   -12.3    .035       0    -2.3    .035       0     8.2    .035       0
#XS Ineff= 2 , 0
       0    -2.3  132.39     8.2       0  132.39
Permanent Ineff=
       F       F
Bank Sta=-2.3,8.2
XS Rating Curve= 0
Exp/Cntr=.3,.1

Type RM Length L Ch R = 1 ,1046.00 ,1,1,1
BEGIN DESCRIPTION:
20.046
END DESCRIPTION:
#Sta/Elev= 9
   -10.7  131.19     -.7  131.19     -.3  130.99       0  130.99      .4  130.29
     7.6  130.29       8  130.99     8.4  130.99    17.4  132.19
#Mann= 3 , 0 , 0
   -10.7    .035       0     -.7    .035       0       8    .035       0
#XS Ineff= 2 , 0
       0     -.7  131.19       8       0  130.99
Permanent Ineff=
       F       F
Bank Sta=-.7,8
XS Rating Curve= 0
Exp/Cntr=.3,.1

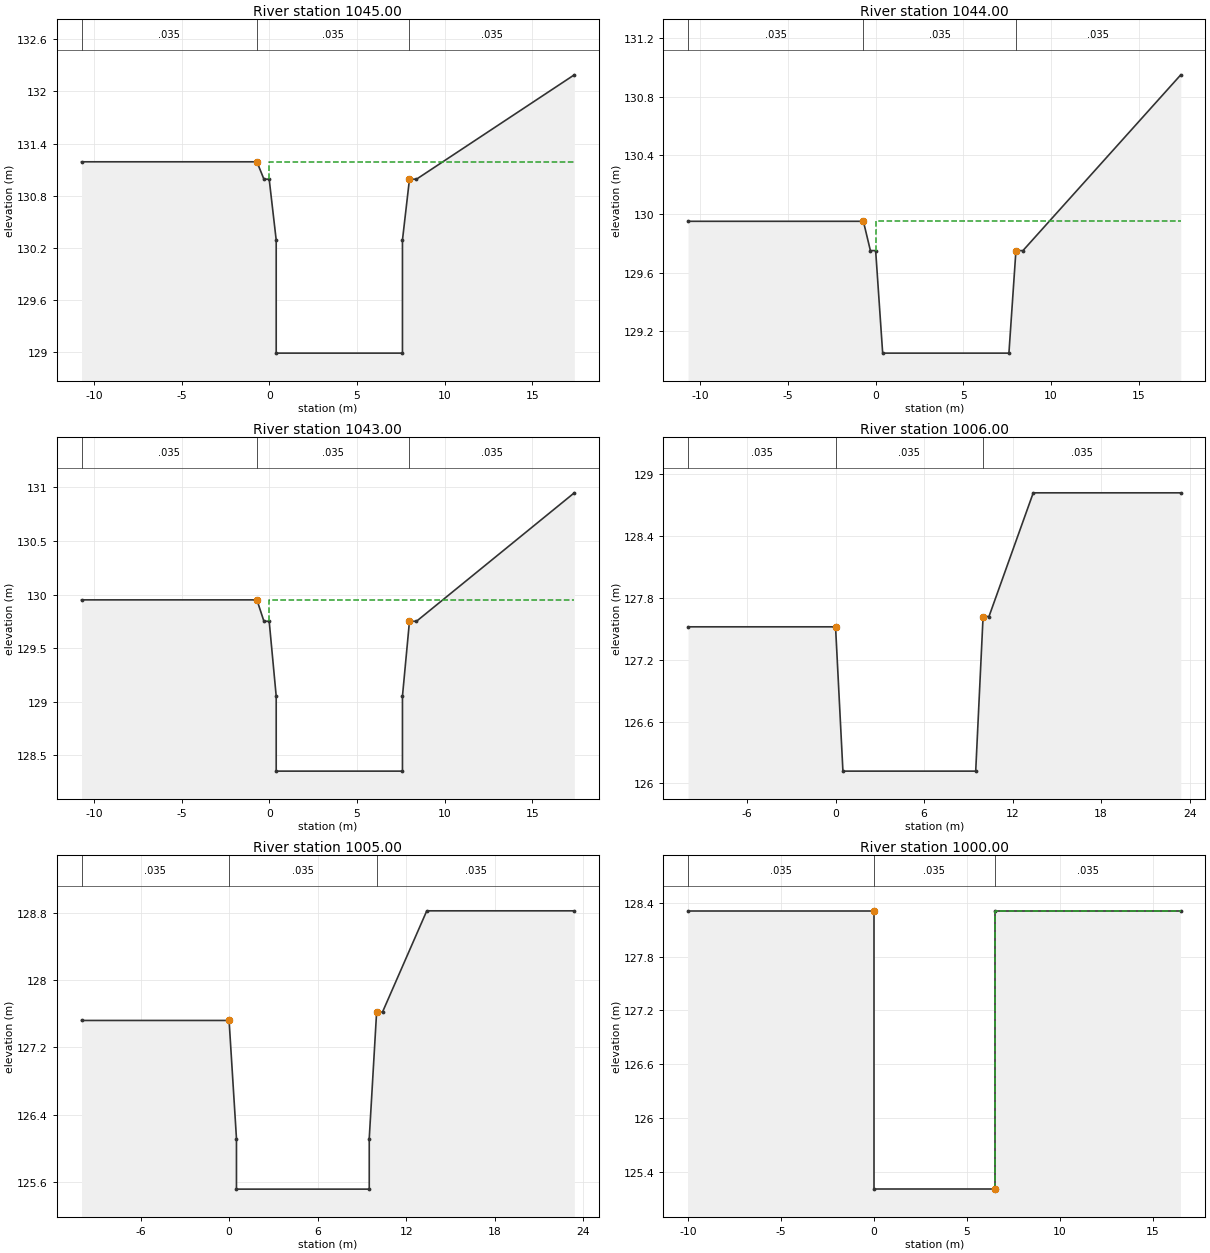
Type RM Length L Ch R = 1 ,1045.00 ,1,1,1
BEGIN DESCRIPTION:
20.045
END DESCRIPTION:
#Sta/Elev= 11
   -10.7  131.19     -.7  131.19     -.3  130.99       0  130.99      .4  130.29
      .4  128.99     7.6  128.99     7.6  130.29       8  130.99     8.4  130.99
    17.4  132.19
#Mann= 3 , 0 , 0
   -10.7    .035       0     -.7    .035       0       8    .035       0
#XS Ineff= 2 , 0
       0     -.7  131.19       8       0  130.99
Permanent Ineff=
       F       F
Bank Sta=-.7,8
XS Rating Curve= 0
Exp/Cntr=.3,.1

Type RM Length L Ch R = 1 ,1044.00 ,1,1,1
BEGIN DESCRIPTION:
20.044
END DESCRIPTION:
#Sta/Elev= 9
   -10.7  129.95     -.7  129.95     -.3  129.75       0  129.75      .4  129.05
     7.6  129.05       8  129.75     8.4  129.75    17.4  130.95
#Mann= 3 , 0 , 0
   -10.7    .035       0     -.7    .035       0       8    .035       0
#XS Ineff= 2 , 0
       0     -.7  129.95       8       0  129.75
Permanent Ineff=
       F       F
Bank Sta=-.7,8
XS Rating Curve= 0
Exp/Cntr=.3,.1

Type RM Length L Ch R = 1 ,1043.00 ,37,37,37
BEGIN DESCRIPTION:
20.043
END DESCRIPTION:
#Sta/Elev= 11
   -10.7  129.95     -.7  129.95     -.3  129.75       0  129.75      .4  129.05
      .4  128.35     7.6  128.35     7.6  129.05       8  129.75     8.4  129.75
    17.4  130.95
#Mann= 3 , 0 , 0
   -10.7    .035       0     -.7    .035       0       8    .035       0
#XS Ineff= 2 , 0
       0     -.7  129.95       8       0  129.75
Permanent Ineff=
       F       F
Bank Sta=-.7,8
XS Rating Curve= 0
Exp/Cntr=.3,.1

Type RM Length L Ch R = 1 ,1006.00 ,1,1,1
BEGIN DESCRIPTION:
20.006
END DESCRIPTION:
#Sta/Elev= 8
     -10  127.52       0  127.52      .5  126.12     9.5  126.12      10  127.62
    10.4  127.62    13.4  128.82    23.4  128.82
#Mann= 3 , 0 , 0
     -10    .035       0       0    .035       0      10    .035       0
#XS Ineff= 2 , 0
       0       0  127.52      10       0  127.62
Permanent Ineff=
       F       F
Bank Sta=0,10
XS Rating Curve= 0
Exp/Cntr=.3,.1

Type RM Length L Ch R = 1 ,1005.00 ,5,5,5
BEGIN DESCRIPTION:
20.005
END DESCRIPTION:
#Sta/Elev= 10
     -10  127.52       0  127.52      .5  126.12      .5  125.52     9.5  125.52
     9.5  126.12      10  127.62    10.4  127.62    13.4  128.82    23.4  128.82
#Mann= 3 , 0 , 0
     -10    .035       0       0    .035       0      10    .035       0
#XS Ineff= 2 , 0
               0  127.52      10          127.62
Permanent Ineff=
       F       F
Bank Sta=0,10
XS Rating Curve= 0
Exp/Cntr=.3,.1

Type RM Length L Ch R = 1 ,1000.00 ,4,4,4
BEGIN DESCRIPTION:
20
END DESCRIPTION:
#Sta/Elev= 6
     -10  128.31       0  128.31       0  125.21     6.5  125.21     6.5  128.31
    16.5  128.31
#Mann= 3 , 0 , 0
     -10    .035       0       0    .035       0     6.5    .035       0
#XS Ineff= 2 , 0
               0  128.31     6.5          128.31
Permanent Ineff=
       F       F
Bank Sta=0,6.5
XS Rating Curve= 0
Exp/Cntr=.3,.1

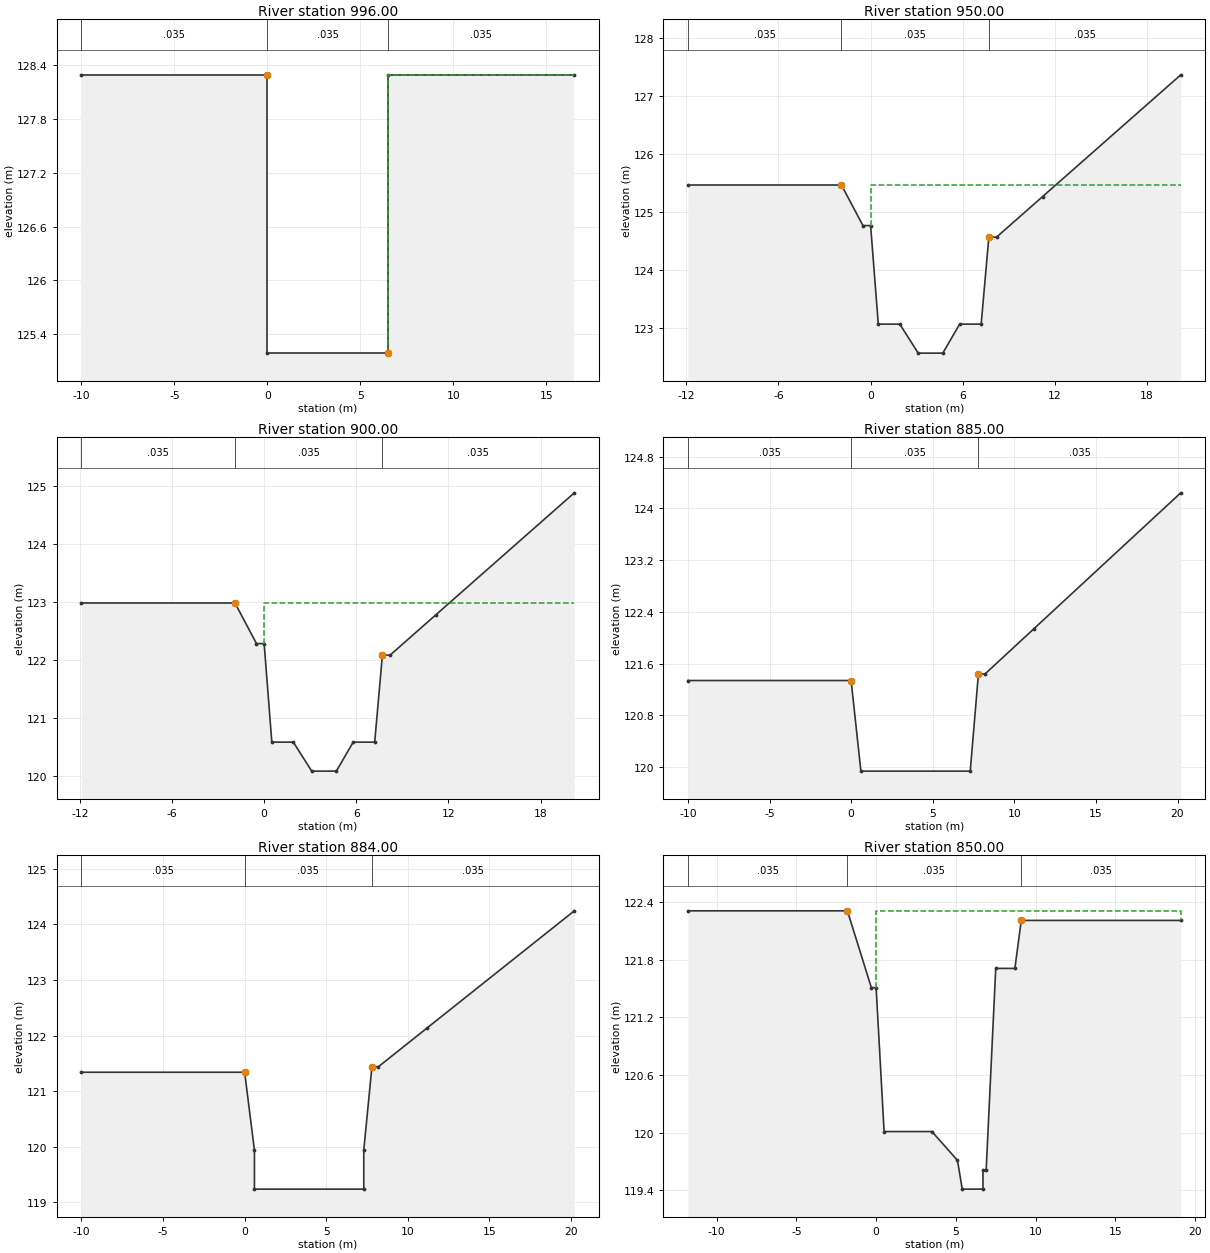
Type RM Length L Ch R = 1 ,996.00  ,46,46,46
BEGIN DESCRIPTION:
19.046
END DESCRIPTION:
#Sta/Elev= 6
     -10  128.29       0  128.29       0  125.19     6.5  125.19     6.5  128.29
    16.5  128.29
#Mann= 3 , 0 , 0
     -10    .035       0       0    .035       0     6.5    .035       0
#XS Ineff= 2 , 0
               0  128.29     6.5          128.29
Permanent Ineff=
       F       F
Bank Sta=0,6.5
XS Rating Curve= 0
Exp/Cntr=.3,.1

Type RM Length L Ch R = 1 ,950.00  ,50,50,50
BEGIN DESCRIPTION:
19
END DESCRIPTION:
#Sta/Elev= 14
   -11.9  125.47    -1.9  125.47     -.5  124.77       0  124.77      .5  123.07
     1.9  123.07     3.1  122.57     4.7  122.57     5.8  123.07     7.2  123.07
     7.7  124.57     8.2  124.57    11.2  125.27    20.2  127.37
#Mann= 3 , 0 , 0
   -11.9    .035       0    -1.9    .035       0     7.7    .035       0
#XS Ineff= 2 , 0
       0    -1.9  125.47     7.7       0  124.57
Permanent Ineff=
       F       F
Bank Sta=-1.9,7.7
XS Rating Curve= 0
Exp/Cntr=.3,.1

Type RM Length L Ch R = 1 ,900.00  ,15,15,15
BEGIN DESCRIPTION:
18
END DESCRIPTION:
#Sta/Elev= 14
   -11.9  122.98    -1.9  122.98     -.5  122.28       0  122.28      .5  120.58
     1.9  120.58     3.1  120.08     4.7  120.08     5.8  120.58     7.2  120.58
     7.7  122.08     8.2  122.08    11.2  122.78    20.2  124.88
#Mann= 3 , 0 , 0
   -11.9    .035       0    -1.9    .035       0     7.7    .035       0
#XS Ineff= 2 , 0
       0    -1.9  122.98     7.7       0  122.08
Permanent Ineff=
       F       F
Bank Sta=-1.9,7.7
XS Rating Curve= 0
Exp/Cntr=.3,.1

Type RM Length L Ch R = 1 ,885.00  ,1,1,1
BEGIN DESCRIPTION:
17.035
END DESCRIPTION:
#Sta/Elev= 8
     -10  121.34       0  121.34      .6  119.94     7.3  119.94     7.8  121.44
     8.2  121.44    11.2  122.14    20.2  124.24
#Mann= 3 , 0 , 0
     -10    .035       0       0    .035       0     7.8    .035       0
#XS Ineff= 2 , 0
       0       0  121.34     7.8       0  121.44
Permanent Ineff=
       F       F
Bank Sta=0,7.8
XS Rating Curve= 0
Exp/Cntr=.3,.1

Type RM Length L Ch R = 1 ,884.00  ,34,34,34
BEGIN DESCRIPTION:
17.034
END DESCRIPTION:
#Sta/Elev= 10
     -10  121.34       0  121.34      .6  119.94      .6  119.24     7.3  119.24
     7.3  119.94     7.8  121.44     8.2  121.44    11.2  122.14    20.2  124.24
#Mann= 3 , 0 , 0
     -10    .035       0       0    .035       0     7.8    .035       0
#XS Ineff= 2 , 0
               0  121.34     7.8          121.44
Permanent Ineff=
       F       F
Bank Sta=0,7.8
XS Rating Curve= 0
Exp/Cntr=.3,.1

Type RM Length L Ch R = 1 ,850.00  ,50,50,50
BEGIN DESCRIPTION:
17
END DESCRIPTION:
#Sta/Elev= 15
   -11.8  122.31    -1.8  122.31     -.3  121.51       0  121.51      .5  120.01
     3.5  120.01     5.1  119.71     5.4  119.41     6.7  119.41     6.7  119.61
     6.9  119.61     7.5  121.71     8.7  121.71     9.1  122.21    19.1  122.21
#Mann= 3 , 0 , 0
   -11.8    .035       0    -1.8    .035       0     9.1    .035       0
#XS Ineff= 2 , 0
       0    -1.8  122.31     9.1       0  122.21
Permanent Ineff=
       F       F
Bank Sta=-1.8,9.1
XS Rating Curve= 0
Exp/Cntr=.3,.1

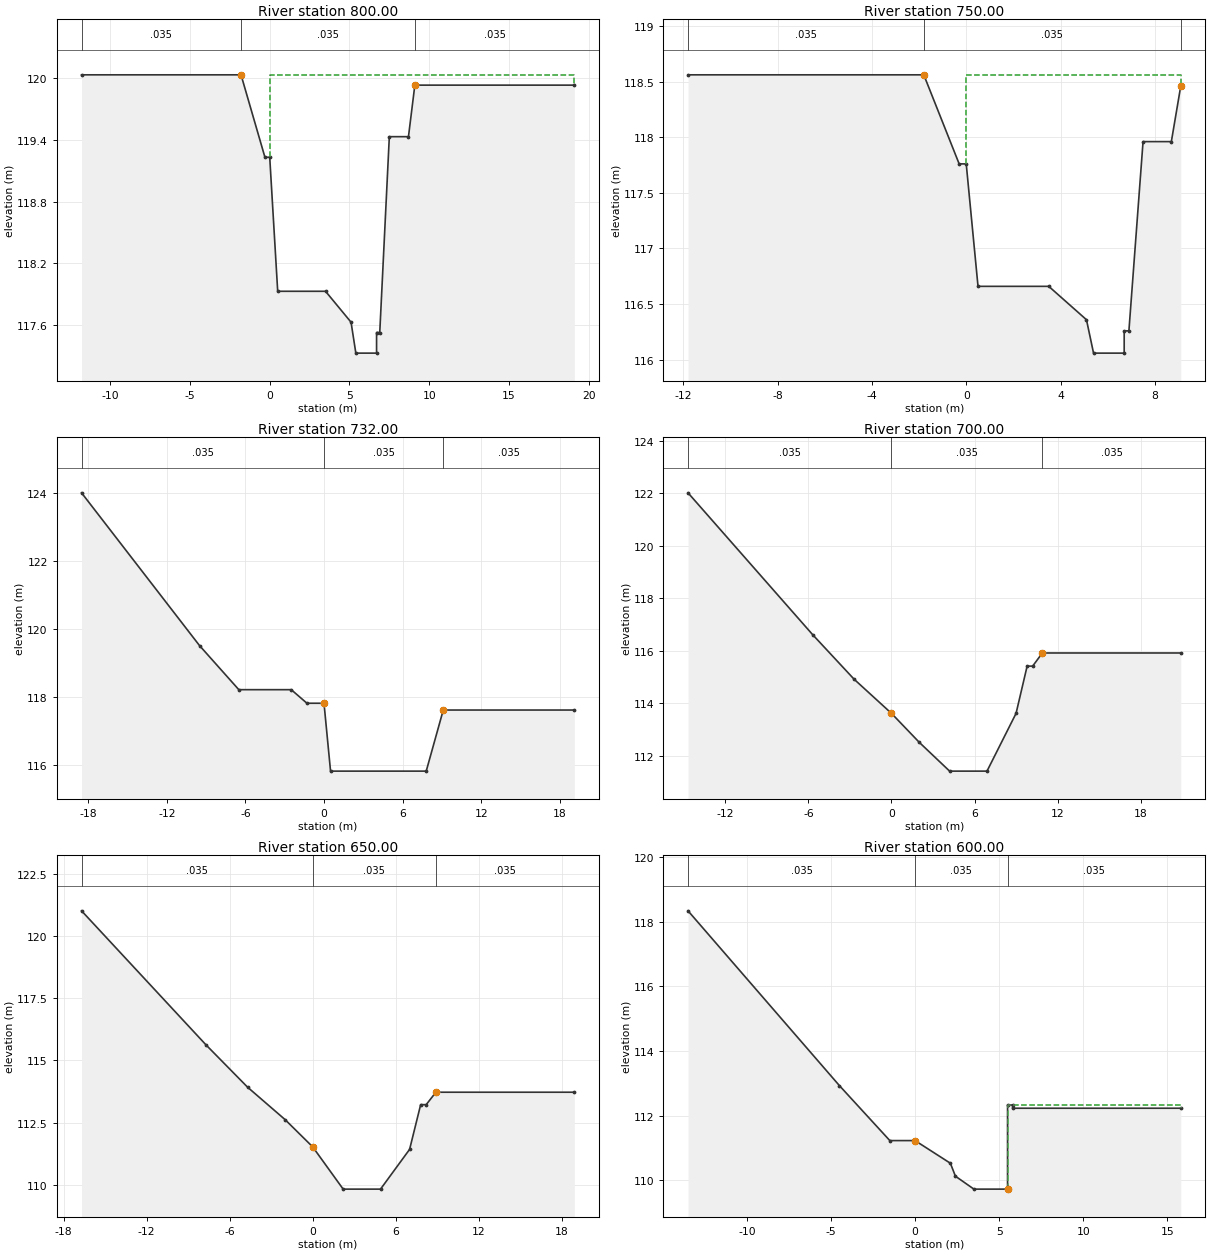
Type RM Length L Ch R = 1 ,800.00  ,50,50,50
BEGIN DESCRIPTION:
16
END DESCRIPTION:
#Sta/Elev= 15
   -11.8  120.03    -1.8  120.03     -.3  119.23       0  119.23      .5  117.93
     3.5  117.93     5.1  117.63     5.4  117.33     6.7  117.33     6.7  117.53
     6.9  117.53     7.5  119.43     8.7  119.43     9.1  119.93    19.1  119.93
#Mann= 3 , 0 , 0
   -11.8    .035       0    -1.8    .035       0     9.1    .035       0
#XS Ineff= 2 , 0
       0    -1.8  120.03     9.1       0  119.93
Permanent Ineff=
       F       F
Bank Sta=-1.8,9.1
XS Rating Curve= 0
Exp/Cntr=.3,.1

Type RM Length L Ch R = 1 ,750.00  ,18,18,18
BEGIN DESCRIPTION:
15
END DESCRIPTION:
#Sta/Elev= 14
   -11.8  118.56    -1.8  118.56     -.3  117.76       0  117.76      .5  116.66
     3.5  116.66     5.1  116.36     5.4  116.06     6.7  116.06     6.7  116.26
     6.9  116.26     7.5  117.96     8.7  117.96     9.1  118.46
#Mann= 3 , 0 , 0
   -11.8    .035       0    -1.8    .035       0     9.1    .035       0
#XS Ineff= 2 , 0
       0    -1.8  118.56     9.1       0  118.46
Permanent Ineff=
       F       F
Bank Sta=-1.8,9.1
XS Rating Curve= 0
Exp/Cntr=.3,.1

Type RM Length L Ch R = 1 ,732.00  ,32,32,32
BEGIN DESCRIPTION:
14.032
END DESCRIPTION:
#Sta/Elev= 10
   -18.5  124.01    -9.5  119.51    -6.5  118.21    -2.5  118.21    -1.3  117.81
       0  117.81      .5  115.81     7.8  115.81     9.1  117.61    19.1  117.61
#Mann= 3 , 0 , 0
   -18.5    .035       0       0    .035       0     9.1    .035       0
#XS Ineff= 2 , 0
               0  117.81     9.1          117.61
Permanent Ineff=
       F       F
Bank Sta=0,9.1
XS Rating Curve= 0
Exp/Cntr=.3,.1

Type RM Length L Ch R = 1 ,700.00  ,50,50,50
BEGIN DESCRIPTION:
14
END DESCRIPTION:
#Sta/Elev= 12
   -14.7  122.02    -5.7  116.62    -2.7  114.92       0  113.62       2  112.52
     4.2  111.42     6.9  111.42       9  113.62     9.8  115.42    10.2  115.42
    10.9  115.92    20.9  115.92
#Mann= 3 , 0 , 0
   -14.7    .035       0       0    .035       0    10.9    .035       0
#XS Ineff= 2 , 0
       0       0  113.62    10.9       0  115.92
Permanent Ineff=
       F       F
Bank Sta=0,10.9
XS Rating Curve= 0
Exp/Cntr=.3,.1

Type RM Length L Ch R = 1 ,650.00  ,50,50,50
BEGIN DESCRIPTION:
13
END DESCRIPTION:
#Sta/Elev= 12
   -16.7  121.02    -7.7  115.62    -4.7  113.92      -2  112.62       0  111.52
     2.2  109.82     4.9  109.82       7  111.42     7.8  113.22     8.2  113.22
     8.9  113.72    18.9  113.72
#Mann= 3 , 0 , 0
   -16.7    .035       0       0    .035       0     8.9    .035       0
#XS Ineff= 2 , 0
       0       0  111.52     8.9       0  113.72
Permanent Ineff=
       F       F
Bank Sta=0,8.9
XS Rating Curve= 0
Exp/Cntr=.3,.1

Type RM Length L Ch R = 1 ,600.00  ,50,50,50
BEGIN DESCRIPTION:
12
END DESCRIPTION:
#Sta/Elev= 12
   -13.5  118.33    -4.5  112.93    -1.5  111.23       0  111.23     2.1  110.53
     2.4  110.13     3.5  109.73     5.5  109.73     5.5  112.33     5.8  112.33
     5.8  112.23    15.8  112.23
#Mann= 3 , 0 , 0
   -13.5    .035       0       0    .035       0     5.5    .035       0
#XS Ineff= 2 , 0
               0  111.23     5.5          112.33
Permanent Ineff=
       F       F
Bank Sta=0,5.5
XS Rating Curve= 0
Exp/Cntr=.3,.1