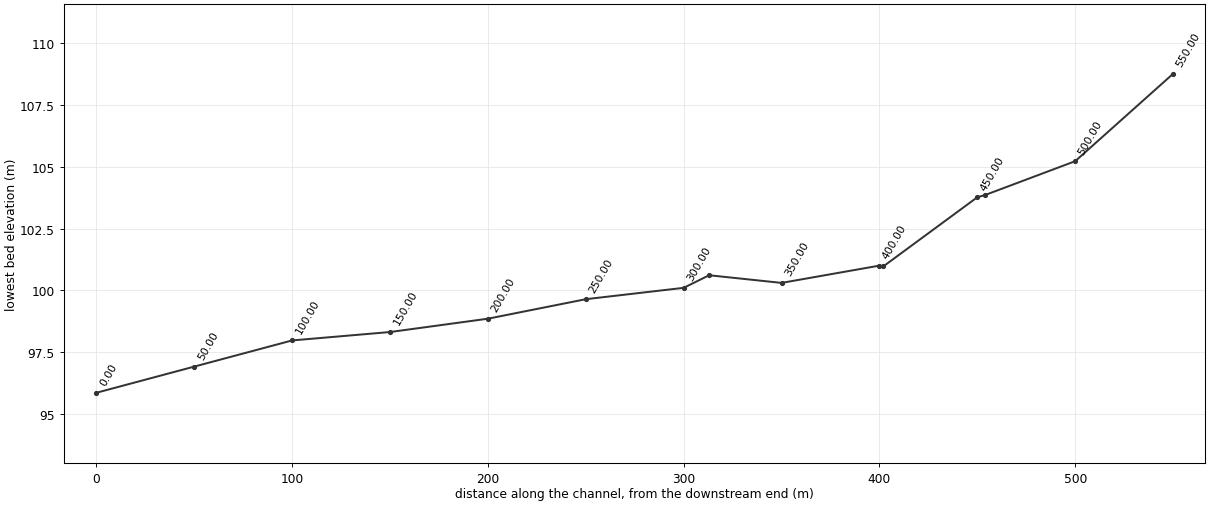
HEC-RAS study DHC.prj: daehan-ch

--- DHC.g01 (geometry) --- (continued)

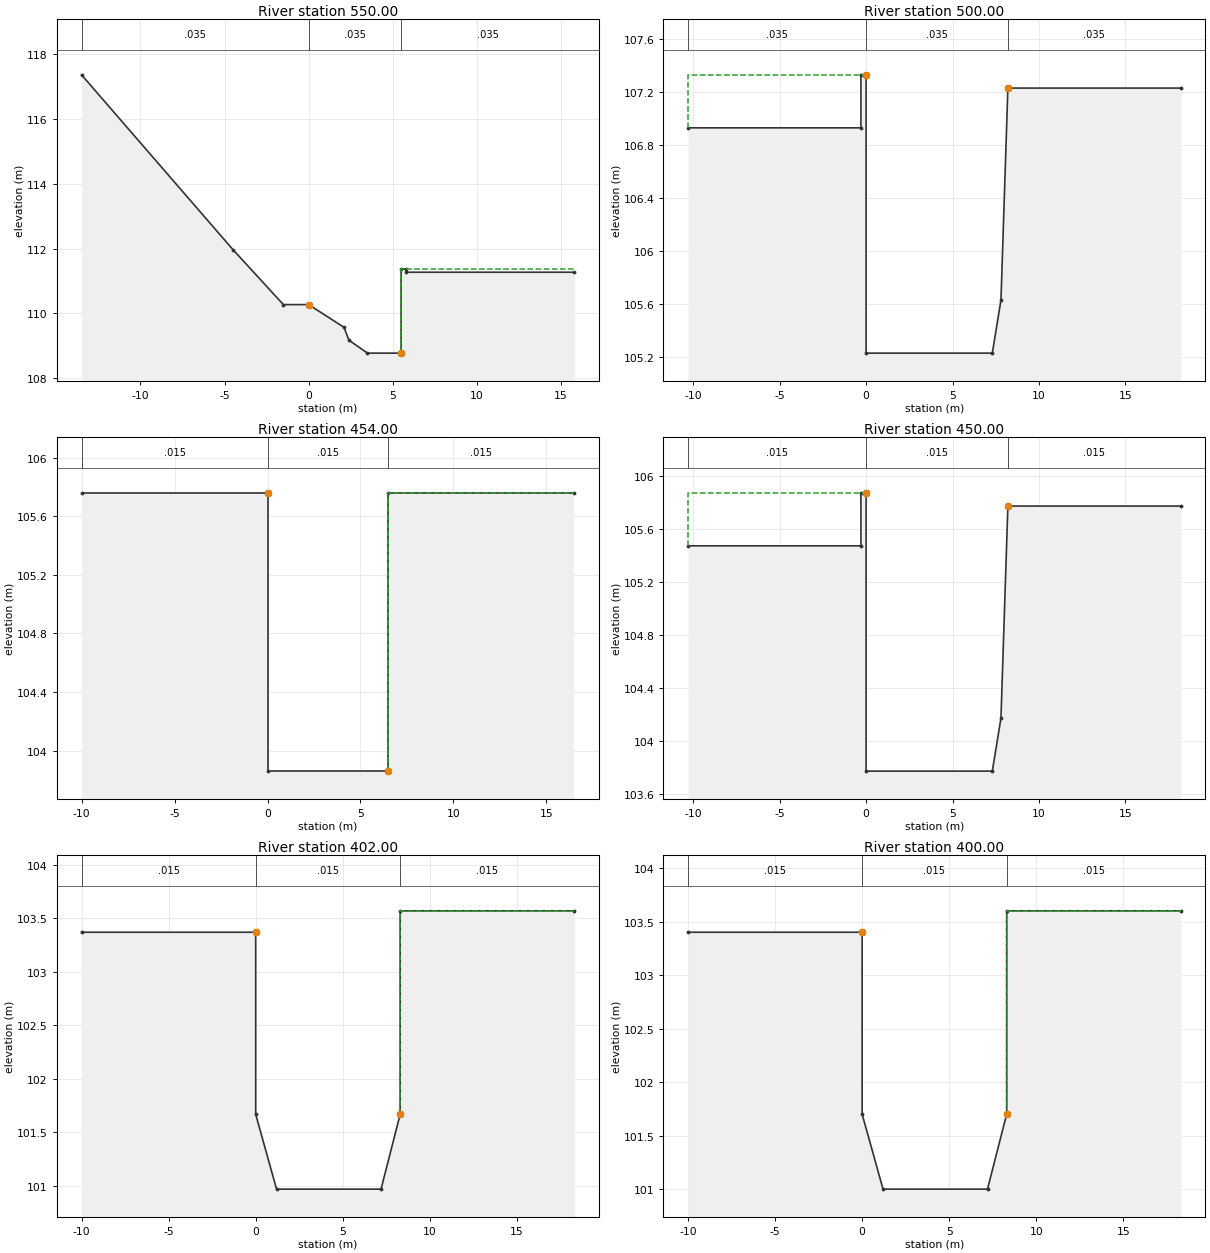
Type RM Length L Ch R = 1 ,550.00  ,50,50,50
BEGIN DESCRIPTION:
11
END DESCRIPTION:
#Sta/Elev= 12
   -13.5  117.37    -4.5  111.97    -1.5  110.27       0  110.27     2.1  109.57
     2.4  109.17     3.5  108.77     5.5  108.77     5.5  111.37     5.8  111.37
     5.8  111.27    15.8  111.27
#Mann= 3 , 0 , 0
   -13.5    .035       0       0    .035       0     5.5    .035       0
#XS Ineff= 2 , 0
               0  110.27     5.5          111.37
Permanent Ineff=
       F       F
Bank Sta=0,5.5
XS Rating Curve= 0
Exp/Cntr=.3,.1

Type RM Length L Ch R = 1 ,500.00  ,46,46,46
BEGIN DESCRIPTION:
10
END DESCRIPTION:
#Sta/Elev= 9
   -10.3  106.93     -.3  106.93     -.3  107.33       0  107.33       0  105.23
     7.3  105.23     7.8  105.63     8.2  107.23    18.2  107.23
#Mann= 3 , 0 , 0
   -10.3    .035       0       0    .035       0     8.2    .035       0
#XS Ineff= 2 , 0
               0  107.33     8.2          107.23
Permanent Ineff=
       F       F
Bank Sta=0,8.2
XS Rating Curve= 0
Exp/Cntr=.3,.1

Type RM Length L Ch R = 1 ,454.00  ,4,4,4
BEGIN DESCRIPTION:
9.004
END DESCRIPTION:
#Sta/Elev= 6
     -10  105.76       0  105.76       0  103.86     6.5  103.86     6.5  105.76
    16.5  105.76
#Mann= 3 , 0 , 0
     -10    .015       0       0    .015       0     6.5    .015       0
#XS Ineff= 2 , 0
               0  105.76     6.5          105.76
Permanent Ineff=
       F       F
Bank Sta=0,6.5
XS Rating Curve= 0
Exp/Cntr=.3,.1

Type RM Length L Ch R = 1 ,450.00  ,48,48,48
BEGIN DESCRIPTION:
9
END DESCRIPTION:
#Sta/Elev= 9
   -10.3  105.47     -.3  105.47     -.3  105.87       0  105.87       0  103.77
     7.3  103.77     7.8  104.17     8.2  105.77    18.2  105.77
#Mann= 3 , 0 , 0
   -10.3    .015       0       0    .015       0     8.2    .015       0
#XS Ineff= 2 , 0
               0  105.87     8.2          105.77
Permanent Ineff=
       F       F
Bank Sta=0,8.2
XS Rating Curve= 0
Exp/Cntr=.3,.1

Type RM Length L Ch R = 1 ,402.00  ,2,2,2
BEGIN DESCRIPTION:
8.002
END DESCRIPTION:
#Sta/Elev= 8
     -10  103.37       0  103.37       0  101.67     1.2  100.97     7.2  100.97
     8.3  101.67     8.3  103.57    18.3  103.57
#Mann= 3 , 0 , 0
     -10    .015       0       0    .015       0     8.3    .015       0
#XS Ineff= 2 , 0
               0  103.37     8.3          103.57
Permanent Ineff=
       F       F
Bank Sta=0,8.3
XS Rating Curve= 0
Exp/Cntr=.3,.1

Type RM Length L Ch R = 1 ,400.00  ,50,50,50
BEGIN DESCRIPTION:
8
END DESCRIPTION:
#Sta/Elev= 8
     -10   103.4       0   103.4       0   101.7     1.2     101     7.2     101
     8.3   101.7     8.3   103.6    18.3   103.6
#Mann= 3 , 0 , 0
     -10    .015       0       0    .015       0     8.3    .015       0
#XS Ineff= 2 , 0
               0   103.4     8.3           103.6
Permanent Ineff=
       F       F
Bank Sta=0,8.3
XS Rating Curve= 0
Exp/Cntr=.3,.1

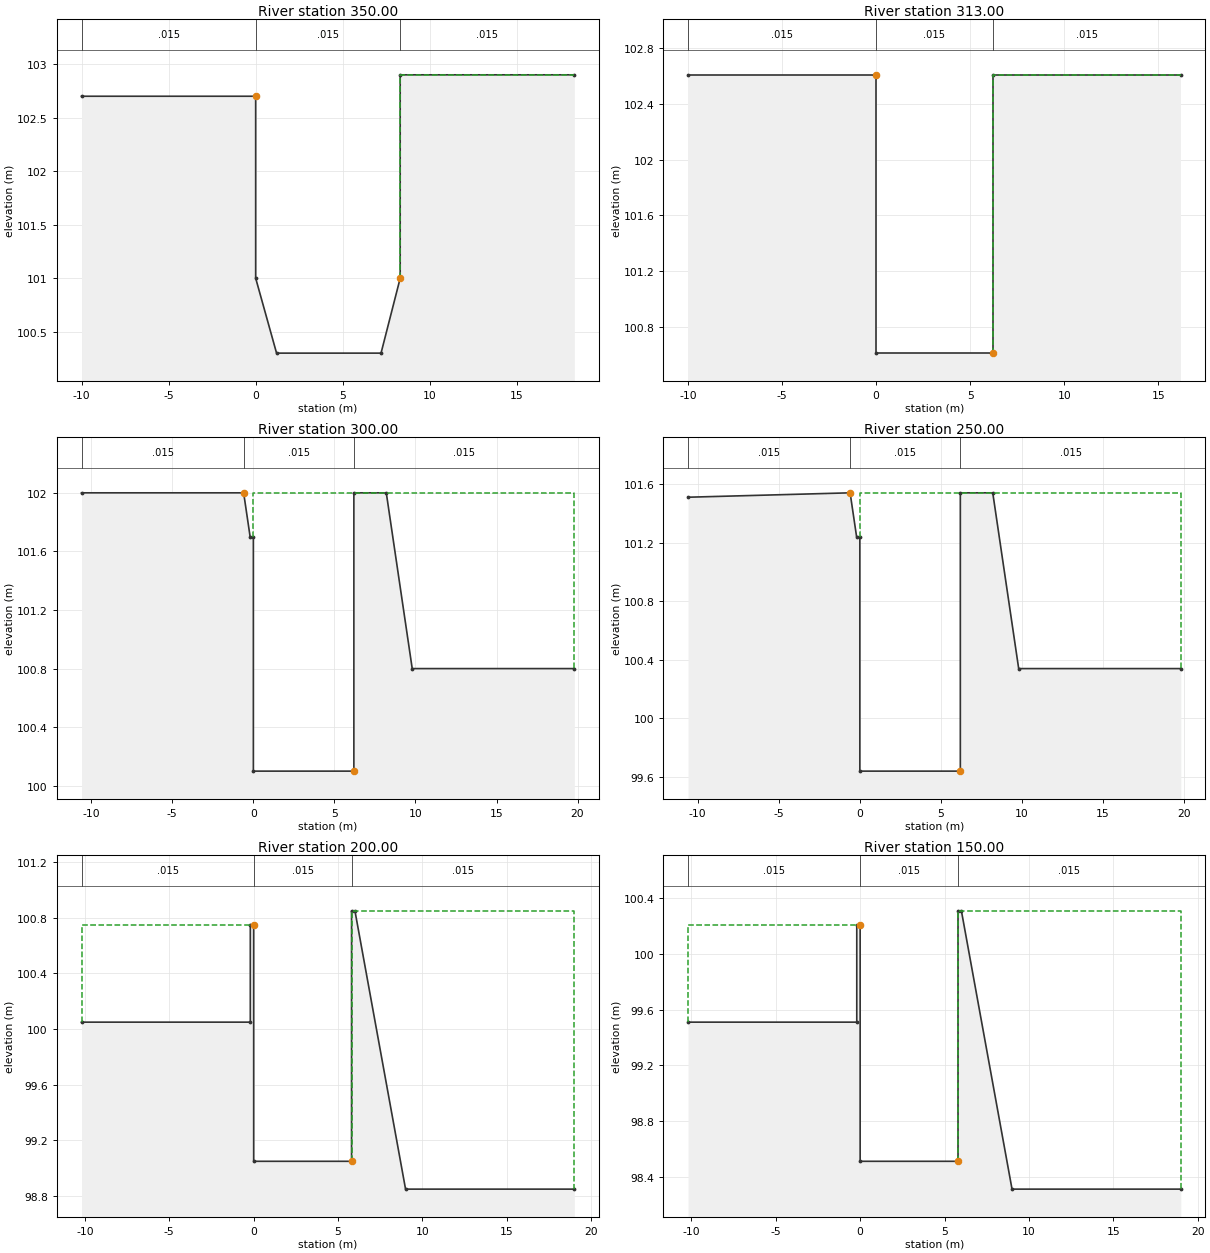
Type RM Length L Ch R = 1 ,350.00  ,37,37,37
BEGIN DESCRIPTION:
7
END DESCRIPTION:
#Sta/Elev= 8
     -10   102.7       0   102.7       0     101     1.2   100.3     7.2   100.3
     8.3     101     8.3   102.9    18.3   102.9
#Mann= 3 , 0 , 0
     -10    .015       0       0    .015       0     8.3    .015       0
#XS Ineff= 2 , 0
               0   102.7     8.3           102.9
Permanent Ineff=
       F       F
Bank Sta=0,8.3
XS Rating Curve= 0
Exp/Cntr=.3,.1

Type RM Length L Ch R = 1 ,313.00  ,13,13,13
BEGIN DESCRIPTION:
6.013
END DESCRIPTION:
#Sta/Elev= 6
     -10  102.61       0  102.61       0  100.61     6.2  100.61     6.2  102.61
    16.2  102.61
#Mann= 3 , 0 , 0
     -10    .015       0       0    .015       0     6.2    .015       0
#XS Ineff= 2 , 0
               0  102.61     6.2          102.61
Permanent Ineff=
       F       F
Bank Sta=0,6.2
XS Rating Curve= 0
Exp/Cntr=.3,.1

Type RM Length L Ch R = 1 ,300.00  ,50,50,50
BEGIN DESCRIPTION:
6
END DESCRIPTION:
#Sta/Elev= 10
   -10.6     102     -.6     102     -.2   101.7       0   101.7       0   100.1
     6.2   100.1     6.2     102     8.2     102     9.8   100.8    19.8   100.8
#Mann= 3 , 0 , 0
   -10.6    .015       0     -.6    .015       0     6.2    .015       0
#XS Ineff= 2 , 0
       0     -.6     102     6.2       0   100.1
Permanent Ineff=
       F       F
Bank Sta=-.6,6.2
XS Rating Curve= 0
Exp/Cntr=.3,.1

Type RM Length L Ch R = 1 ,250.00  ,50,50,50
BEGIN DESCRIPTION:
5
END DESCRIPTION:
#Sta/Elev= 10
   -10.6  101.51     -.6  101.54     -.2  101.24       0  101.24       0   99.64
     6.2   99.64     6.2  101.54     8.2  101.54     9.8  100.34    19.8  100.34
#Mann= 3 , 0 , 0
   -10.6    .015       0     -.6    .015       0     6.2    .015       0
#XS Ineff= 2 , 0
       0     -.6  101.54     6.2       0   99.64
Permanent Ineff=
       F       F
Bank Sta=-.6,6.2
XS Rating Curve= 0
Exp/Cntr=.3,.1

Type RM Length L Ch R = 1 ,200.00  ,50,50,50
BEGIN DESCRIPTION:
4
END DESCRIPTION:
#Sta/Elev= 10
   -10.2  100.05     -.2  100.05     -.2  100.75       0  100.75       0   99.05
     5.8   99.05     5.8  100.85       6  100.85       9   98.85      19   98.85
#Mann= 3 , 0 , 0
   -10.2    .015       0       0    .015       0     5.8    .015       0
#XS Ineff= 2 , 0
               0  100.75     5.8          100.85
Permanent Ineff=
       F       F
Bank Sta=0,5.8
XS Rating Curve= 0
Exp/Cntr=.3,.1

Type RM Length L Ch R = 1 ,150.00  ,50,50,50
BEGIN DESCRIPTION:
3
END DESCRIPTION:
#Sta/Elev= 10
   -10.2   99.51     -.2   99.51     -.2  100.21       0  100.21       0   98.51
     5.8   98.51     5.8  100.31       6  100.31       9   98.31      19   98.31
#Mann= 3 , 0 , 0
   -10.2    .015       0       0    .015       0     5.8    .015       0
#XS Ineff= 2 , 0
               0  100.21     5.8          100.31
Permanent Ineff=
       F       F
Bank Sta=0,5.8
XS Rating Curve= 0
Exp/Cntr=.3,.1

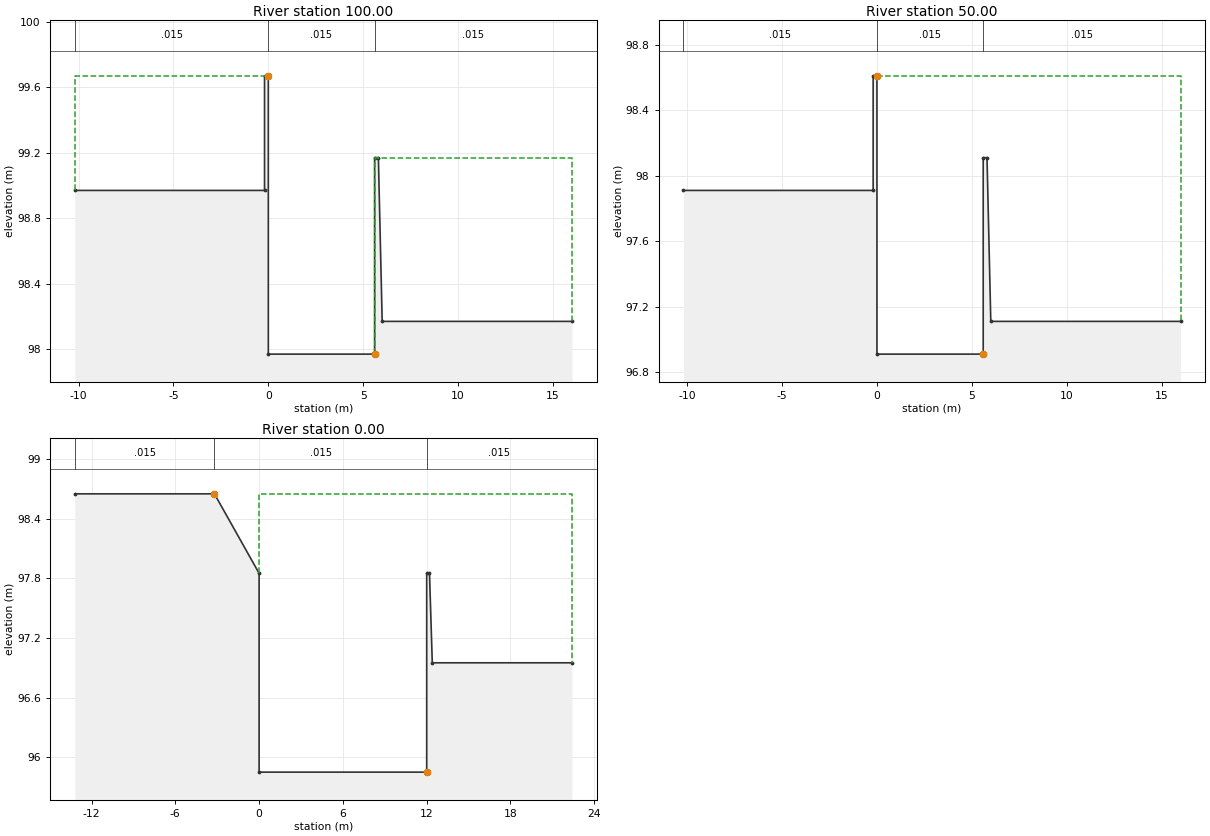
Type RM Length L Ch R = 1 ,100.00  ,50,50,50
BEGIN DESCRIPTION:
2
END DESCRIPTION:
#Sta/Elev= 10
   -10.2   98.97     -.2   98.97     -.2   99.67       0   99.67       0   97.97
     5.6   97.97     5.6   99.17     5.8   99.17       6   98.17      16   98.17
#Mann= 3 , 0 , 0
   -10.2    .015       0       0    .015       0     5.6    .015       0
#XS Ineff= 2 , 0
               0   99.67     5.6           99.17
Permanent Ineff=
       F       F
Bank Sta=0,5.6
XS Rating Curve= 0
Exp/Cntr=.3,.1

Type RM Length L Ch R = 1 ,50.00   ,50,50,50
BEGIN DESCRIPTION:
1
END DESCRIPTION:
#Sta/Elev= 10
   -10.2   97.91     -.2   97.91     -.2   98.61       0   98.61       0   96.91
     5.6   96.91     5.6   98.11     5.8   98.11       6   97.11      16   97.11
#Mann= 3 , 0 , 0
   -10.2    .015       0       0    .015       0     5.6    .015       0
#XS Ineff= 2 , 0
       0       0   98.61     5.6       0   96.91
Permanent Ineff=
       F       F
Bank Sta=0,5.6
XS Rating Curve= 0
Exp/Cntr=.3,.1

Type RM Length L Ch R = 1 ,0.00    ,0,0,0
BEGIN DESCRIPTION:
0
END DESCRIPTION:
#Sta/Elev= 9
   -13.2   98.65    -3.2   98.65       0   97.85       0   95.85      12   95.85
      12   97.85    12.2   97.85    12.4   96.95    22.4   96.95
#Mann= 3 , 0 , 0
   -13.2    .015       0    -3.2    .015       0      12    .015       0
#XS Ineff= 2 , 0
       0    -3.2   98.65      12       0   95.85
Permanent Ineff=
       F       F
Bank Sta=-3.2,12
XS Rating Curve= 0
Exp/Cntr=.3,.1

Chan Stop Cuts=-1