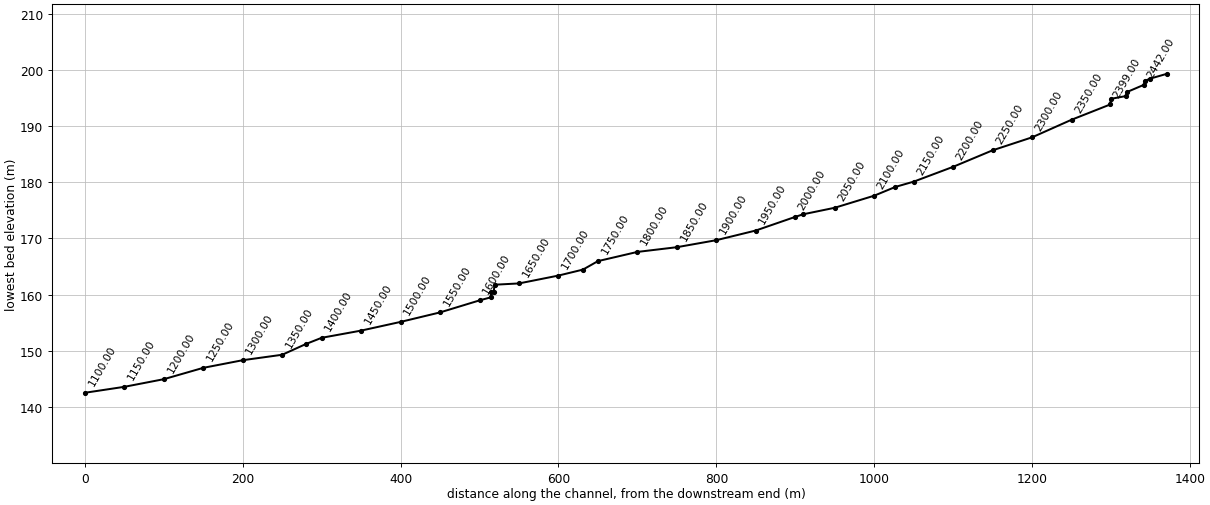
--- JKC.prj (project) ---

Proj Title=jogae-ch
Current Plan=p01
Default Exp/Contr=.3,.1
SI Units
Geom File=g01
Flow File=f01
Plan File=p01
Y Axis Title=Elevation
X Axis Title(PF)=Main Channel Distance
X Axis Title(XS)=Station
BEGIN DESCRIPTION:
           BACK WATER COMPUTATION
      APPLICATION OF HEC-2 BY Samju Construction Engineering
      jogae-ch: 10,20,30,50,80 yr
END DESCRIPTION:
DSS Export Rating Curves= 0
DSS Export Rating Curve Sorted= 0
DSS Export Volume Flow Curves= 0
DXF OffsetX= 0
DXF OffsetY= 0
DXF ScaleX= 1
DXF ScaleY= 10

--- JKC.p01 (plan) ---

Plan Title=Imported Plan 01
Version=Version 3.0.1  Mar 2001
Short Identifier=Imported Pla
Geom File=g01
Flow File=f01
Subcritical Flow
K Sum by GR= 0
Std Step Tol= 0.003
Critical Tol= 0.003
Num of Std Step Trials= 20
Max Error Tol= 0.1
Flow Tol Ratio= 0.001
Split Flow NTrial= 30
Split Flow Tol= 0.02
Split Flow Ratio= 0.02
Log Output Level= 0
Friction Slope Method= 1
Unsteady Friction Slope Method= 2
Parabolic Critical Depth
Global Vel Dist= 0 , 0 , 0
Global Log Level= 0
CheckData=True
Encroach Param=-1 ,0,0, 0
Computation Interval=1HOUR
Output Interval=1HOUR
Run HTab= 0
Run UNet= 0
Run PostProcess= 0
UNET Theta= 1
UNET ZTol= 0.02
UNET ZSATol= 0.1
UNET MxIter= 20
UNET MaxInSteps= 20
UNET DtIC= 0
UNET DtMin= 0
UNET MaxCRTS= 20
UNET WFStab= 2
UNET SFStab= 1
UNET WFX= 1
UNET SFX= 1
UNET Convert EG Bridges=-1
UNET Use Existing IB Tables=-1
Instantaneous Interval=1HOUR
Write IC File= 0
Write Velocity= 0
Write Detailed= 0

--- JKC.f01 (steady flow) ---

Flow Title=Imported Flow 01
Version=Version 3.0.1  Mar 2001
Number of Profiles= 5
Profile Names=10YR,20YR,30YR,50YR,80YR
River Rch & RM=RIVER-1,Reach-1         ,2471.00
    42.5   46.85    49.4   52.61   55.56
Boundary for River Rch & Prof#=RIVER-1,Reach-1         , 1
Up Type= 0
Dn Type= 3
Dn Slope=.022
Boundary for River Rch & Prof#=RIVER-1,Reach-1         , 2
Up Type= 0
Dn Type= 3
Dn Slope=.022
Boundary for River Rch & Prof#=RIVER-1,Reach-1         , 3
Up Type= 0
Dn Type= 3
Dn Slope=.022
Boundary for River Rch & Prof#=RIVER-1,Reach-1         , 4
Up Type= 0
Dn Type= 3
Dn Slope=.022
Boundary for River Rch & Prof#=RIVER-1,Reach-1         , 5
Up Type= 0
Dn Type= 3
Dn Slope=.022
DSS Import GetInterval= 0
DSS Import GetPeak= 0
DSS Import FillOption= 0

--- JKC.g01 (geometry) ---

Geom Title=Imported Geom 01
Version=Version 3.0.1  Mar 2001

River Reach=RIVER-1         ,Reach-1
Reach XY= 2
              .5             .95              .5             .05

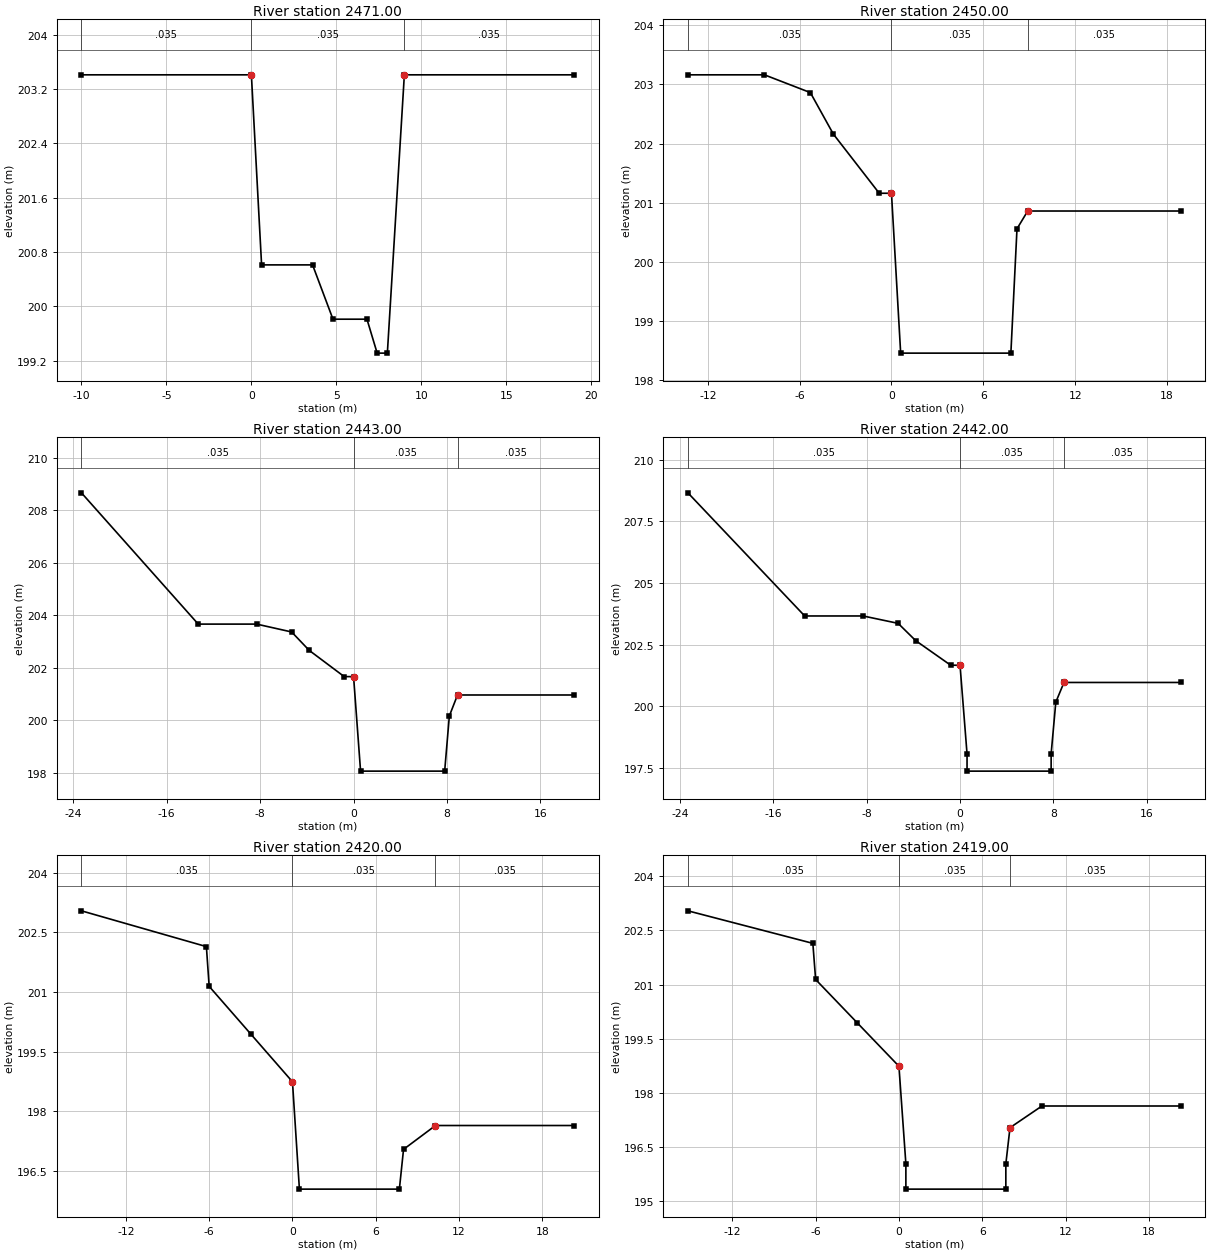
Type RM Length L Ch R = 1 ,2471.00 ,21,21,21
BEGIN DESCRIPTION:
49.021
END DESCRIPTION:
#Sta/Elev= 10
     -10  203.41       0  203.41      .6  200.61     3.6  200.61     4.8  199.81
     6.8  199.81     7.4  199.31       8  199.31       9  203.41      19  203.41
#Mann= 3 , 0 , 0
     -10    .035       0       0    .035       0       9    .035       0
#XS Ineff= 2 , 0
               0  203.41       9          203.41
Permanent Ineff=
       F       F
Bank Sta=0,9
XS Rating Curve= 0
Exp/Cntr=.3,.1

Type RM Length L Ch R = 1 ,2450.00 ,7,7,7
BEGIN DESCRIPTION:
49
END DESCRIPTION:
#Sta/Elev= 11
   -13.3  203.16    -8.3  203.16    -5.3  202.86    -3.8  202.16     -.8  201.16
       0  201.16      .6  198.46     7.8  198.46     8.2  200.56     8.9  200.86
    18.9  200.86
#Mann= 3 , 0 , 0
   -13.3    .035       0       0    .035       0     8.9    .035       0
#XS Ineff= 2 , 0
               0  201.16     8.9          200.86
Permanent Ineff=
       F       F
Bank Sta=0,8.9
XS Rating Curve= 0
Exp/Cntr=.3,.1

Type RM Length L Ch R = 1 ,2443.00 ,1,1,1
BEGIN DESCRIPTION:
48.043
END DESCRIPTION:
#Sta/Elev= 12
   -23.3  208.66   -13.3  203.66    -8.3  203.66    -5.3  203.36    -3.8  202.66
     -.8  201.66       0  201.66      .6  198.06     7.8  198.06     8.2  200.16
     8.9  200.96    18.9  200.96
#Mann= 3 , 0 , 0
   -23.3    .035       0       0    .035       0     8.9    .035       0
#XS Ineff= 2 , 0
               0  201.66     8.9          200.96
Permanent Ineff=
       F       F
Bank Sta=0,8.9
XS Rating Curve= 0
Exp/Cntr=.3,.1

Type RM Length L Ch R = 1 ,2442.00 ,22,22,22
BEGIN DESCRIPTION:
48.042
END DESCRIPTION:
#Sta/Elev= 14
   -23.3  208.66   -13.3  203.66    -8.3  203.66    -5.3  203.36    -3.8  202.66
     -.8  201.66       0  201.66      .6  198.06      .6  197.36     7.8  197.36
     7.8  198.06     8.2  200.16     8.9  200.96    18.9  200.96
#Mann= 3 , 0 , 0
   -23.3    .035       0       0    .035       0     8.9    .035       0
#XS Ineff= 2 , 0
               0  201.66     8.9          200.96
Permanent Ineff=
       F       F
Bank Sta=0,8.9
XS Rating Curve= 0
Exp/Cntr=.3,.1

Type RM Length L Ch R = 1 ,2420.00 ,1,1,1
BEGIN DESCRIPTION:
48.02
END DESCRIPTION:
#Sta/Elev= 10
   -15.2  203.04    -6.2  202.14      -6  201.14      -3  199.94       0  198.74
      .5  196.04     7.7  196.04       8  197.04    10.3  197.64    20.3  197.64
#Mann= 3 , 0 , 0
   -15.2    .035       0       0    .035       0    10.3    .035       0
#XS Ineff= 2 , 0
               0  198.74    10.3          197.64
Permanent Ineff=
       F       F
Bank Sta=0,10.3
XS Rating Curve= 0
Exp/Cntr=.3,.1

Type RM Length L Ch R = 1 ,2419.00 ,19,19,19
BEGIN DESCRIPTION:
48.019
END DESCRIPTION:
#Sta/Elev= 12
   -15.2  203.04    -6.2  202.14      -6  201.14      -3  199.94       0  198.74
      .5  196.04      .5  195.34     7.7  195.34     7.7  196.04       8  197.04
    10.3  197.64    20.3  197.64
#Mann= 3 , 0 , 0
   -15.2    .035       0       0    .035       0       8    .035       0
#XS Ineff= 2 , 0
               0  198.74       8          197.04
Permanent Ineff=
       F       F
Bank Sta=0,8
XS Rating Curve= 0
Exp/Cntr=.3,.1

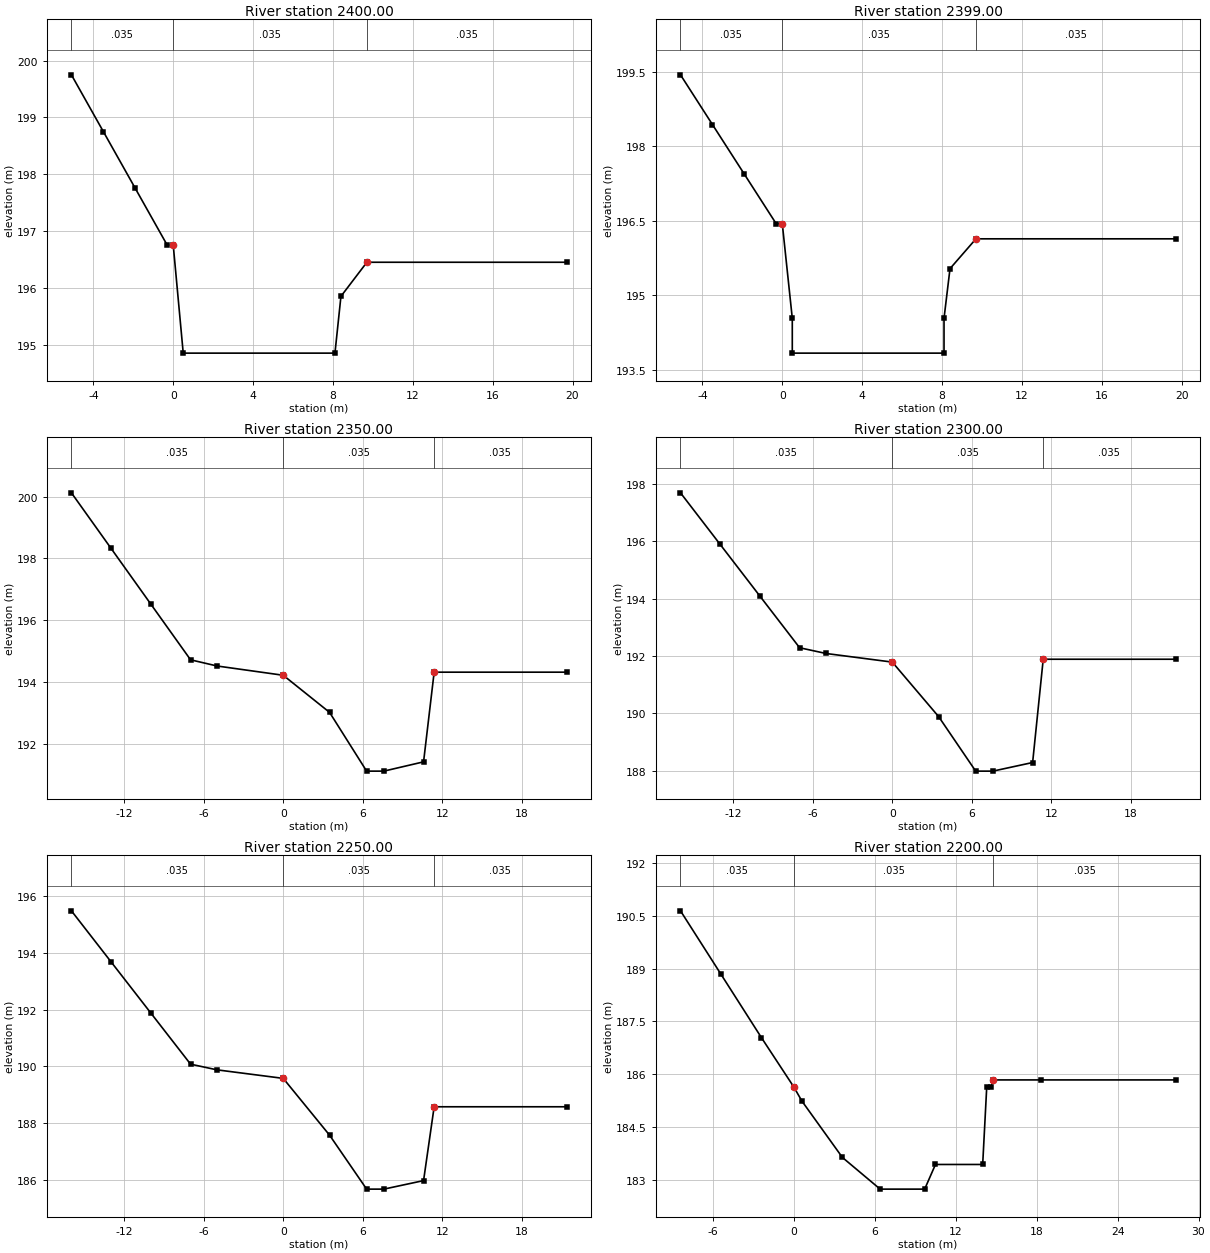
Type RM Length L Ch R = 1 ,2400.00 ,1,1,1
BEGIN DESCRIPTION:
48
END DESCRIPTION:
#Sta/Elev= 10
    -5.1  199.75    -3.5  198.75    -1.9  197.75     -.3  196.75       0  196.75
      .5  194.85     8.1  194.85     8.4  195.85     9.7  196.45    19.7  196.45
#Mann= 3 , 0 , 0
    -5.1    .035       0       0    .035       0     9.7    .035       0
#XS Ineff= 2 , 0
               0  196.75     9.7          196.45
Permanent Ineff=
       F       F
Bank Sta=0,9.7
XS Rating Curve= 0
Exp/Cntr=.3,.1

Type RM Length L Ch R = 1 ,2399.00 ,49,49,49
BEGIN DESCRIPTION:
47.049
END DESCRIPTION:
#Sta/Elev= 12
    -5.1  199.44    -3.5  198.44    -1.9  197.44     -.3  196.44       0  196.44
      .5  194.54      .5  193.84     8.1  193.84     8.1  194.54     8.4  195.54
     9.7  196.14    19.7  196.14
#Mann= 3 , 0 , 0
    -5.1    .035       0       0    .035       0     9.7    .035       0
#XS Ineff= 2 , 0
               0  196.44     9.7          196.14
Permanent Ineff=
       F       F
Bank Sta=0,9.7
XS Rating Curve= 0
Exp/Cntr=.3,.1

Type RM Length L Ch R = 1 ,2350.00 ,50,50,50
BEGIN DESCRIPTION:
47
END DESCRIPTION:
#Sta/Elev= 12
     -16  200.12     -13  198.32     -10  196.52      -7  194.72      -5  194.52
       0  194.22     3.5  193.02     6.3  191.12     7.6  191.12    10.6  191.42
    11.4  194.32    21.4  194.32
#Mann= 3 , 0 , 0
     -16    .035       0       0    .035       0    11.4    .035       0
#XS Ineff= 2 , 0
               0  194.22    11.4          194.32
Permanent Ineff=
       F       F
Bank Sta=0,11.4
XS Rating Curve= 0
Exp/Cntr=.3,.1

Type RM Length L Ch R = 1 ,2300.00 ,50,50,50
BEGIN DESCRIPTION:
46
END DESCRIPTION:
#Sta/Elev= 12
     -16  197.69     -13  195.89     -10  194.09      -7  192.29      -5  192.09
       0  191.79     3.5  189.89     6.3  187.99     7.6  187.99    10.6  188.29
    11.4  191.89    21.4  191.89
#Mann= 3 , 0 , 0
     -16    .035       0       0    .035       0    11.4    .035       0
#XS Ineff= 2 , 0
               0  191.79    11.4          191.89
Permanent Ineff=
       F       F
Bank Sta=0,11.4
XS Rating Curve= 0
Exp/Cntr=.3,.1

Type RM Length L Ch R = 1 ,2250.00 ,50,50,50
BEGIN DESCRIPTION:
45
END DESCRIPTION:
#Sta/Elev= 12
     -16  195.48     -13  193.68     -10  191.88      -7  190.08      -5  189.88
       0  189.58     3.5  187.58     6.3  185.68     7.6  185.68    10.6  185.98
    11.4  188.58    21.4  188.58
#Mann= 3 , 0 , 0
     -16    .035       0       0    .035       0    11.4    .035       0
#XS Ineff= 2 , 0
               0  189.58    11.4          188.58
Permanent Ineff=
       F       F
Bank Sta=0,11.4
XS Rating Curve= 0
Exp/Cntr=.3,.1

Type RM Length L Ch R = 1 ,2200.00 ,50,50,50
BEGIN DESCRIPTION:
44
END DESCRIPTION:
#Sta/Elev= 15
    -8.4  190.64    -5.4  188.84    -2.4  187.04       0  185.64      .6  185.24
     3.6  183.64     6.4  182.74     9.7  182.74    10.5  183.44      14  183.44
    14.3  185.64    14.6  185.64    14.8  185.84    18.3  185.84    28.3  185.84
#Mann= 3 , 0 , 0
    -8.4    .035       0       0    .035       0    14.8    .035       0
#XS Ineff= 2 , 0
       0       0  185.64    14.8       0  185.84
Permanent Ineff=
       F       F
Bank Sta=0,14.8
XS Rating Curve= 0
Exp/Cntr=.3,.1

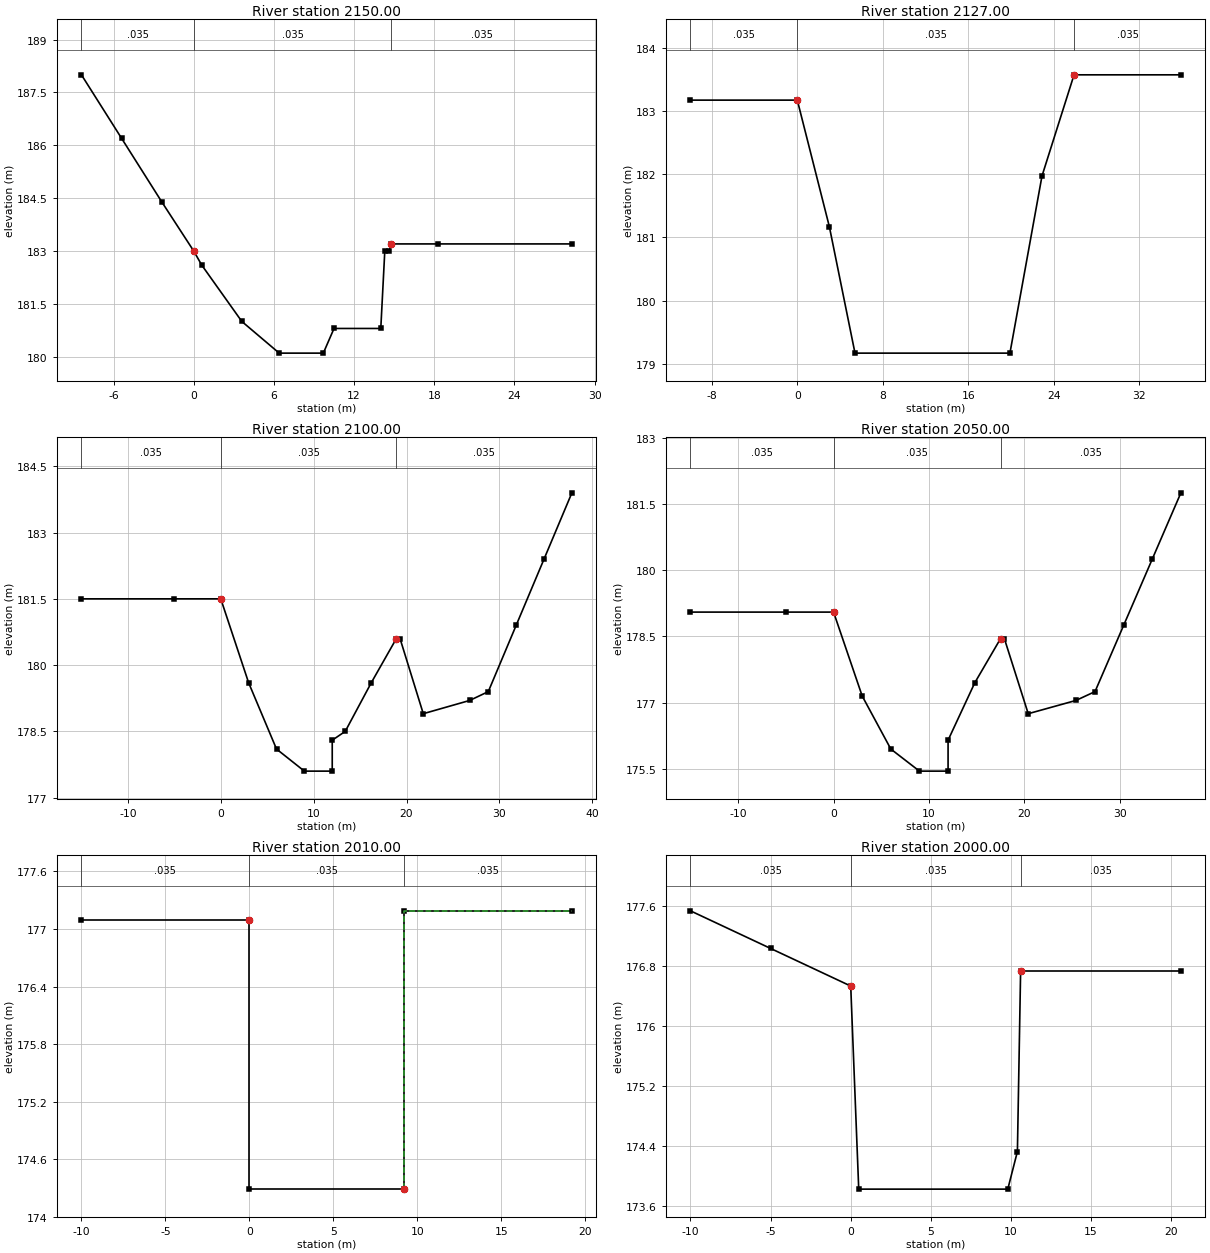
Type RM Length L Ch R = 1 ,2150.00 ,23,23,23
BEGIN DESCRIPTION:
43
END DESCRIPTION:
#Sta/Elev= 15
    -8.4     188    -5.4   186.2    -2.4   184.4       0     183      .6   182.6
     3.6     181     6.4   180.1     9.7   180.1    10.5   180.8      14   180.8
    14.3     183    14.6     183    14.8   183.2    18.3   183.2    28.3   183.2
#Mann= 3 , 0 , 0
    -8.4    .035       0       0    .035       0    14.8    .035       0
#XS Ineff= 2 , 0
       0       0     183    14.8       0   183.2
Permanent Ineff=
       F       F
Bank Sta=0,14.8
XS Rating Curve= 0
Exp/Cntr=.3,.1

Type RM Length L Ch R = 1 ,2127.00 ,27,27,27
BEGIN DESCRIPTION:
42.027
END DESCRIPTION:
#Sta/Elev= 8
     -10  183.17       0  183.17       3  181.17     5.4  179.17    19.9  179.17
    22.9  181.97    25.9  183.57    35.9  183.57
#Mann= 3 , 0 , 0
     -10    .035       0       0    .035       0    25.9    .035       0
#XS Ineff= 2 , 0
               0  183.17    25.9          183.57
Permanent Ineff=
       F       F
Bank Sta=0,25.9
XS Rating Curve= 0
Exp/Cntr=.3,.1

Type RM Length L Ch R = 1 ,2100.00 ,50,50,50
BEGIN DESCRIPTION:
42
END DESCRIPTION:
#Sta/Elev= 18
     -15   181.5      -5   181.5       0   181.5       3   179.6       6   178.1
       9   177.6      12   177.6      12   178.3    13.4   178.5    16.2   179.6
    18.9   180.6    19.3   180.6    21.8   178.9    26.8   179.2    28.8   179.4
    31.8   180.9    34.8   182.4    37.8   183.9
#Mann= 3 , 0 , 0
     -15    .035       0       0    .035       0    18.9    .035       0
#XS Ineff= 2 , 0
               0   181.5    18.9           180.6
Permanent Ineff=
       F       F
Bank Sta=0,18.9
XS Rating Curve= 0
Exp/Cntr=.3,.1

Type RM Length L Ch R = 1 ,2050.00 ,40,40,40
BEGIN DESCRIPTION:
41
END DESCRIPTION:
#Sta/Elev= 17
     -15  179.05      -5  179.05       0  179.05       3  177.15       6  175.95
       9  175.45      12  175.45      12  176.15    14.8  177.45    17.5  178.45
    17.9  178.45    20.4  176.75    25.4  177.05    27.4  177.25    30.4  178.75
    33.4  180.25    36.4  181.75
#Mann= 3 , 0 , 0
     -15    .035       0       0    .035       0    17.5    .035       0
#XS Ineff= 2 , 0
       0       0  179.05    17.5       0  178.45
Permanent Ineff=
       F       F
Bank Sta=0,17.5
XS Rating Curve= 0
Exp/Cntr=.3,.1

Type RM Length L Ch R = 1 ,2010.00 ,10,10,10
BEGIN DESCRIPTION:
40.01
END DESCRIPTION:
#Sta/Elev= 6
     -10  177.09       0  177.09       0  174.29     9.2  174.29     9.2  177.19
    19.2  177.19
#Mann= 3 , 0 , 0
     -10    .035       0       0    .035       0     9.2    .035       0
#XS Ineff= 2 , 0
               0  177.09     9.2          177.19
Permanent Ineff=
       F       F
Bank Sta=0,9.2
XS Rating Curve= 0
Exp/Cntr=.3,.1

Type RM Length L Ch R = 1 ,2000.00 ,50,50,50
BEGIN DESCRIPTION:
40
END DESCRIPTION:
#Sta/Elev= 8
     -10  177.53      -5  177.03       0  176.53      .5  173.83     9.8  173.83
    10.4  174.33    10.6  176.73    20.6  176.73
#Mann= 3 , 0 , 0
     -10    .035       0       0    .035       0    10.6    .035       0
#XS Ineff= 2 , 0
               0  176.53    10.6          176.73
Permanent Ineff=
       F       F
Bank Sta=0,10.6
XS Rating Curve= 0
Exp/Cntr=.3,.1

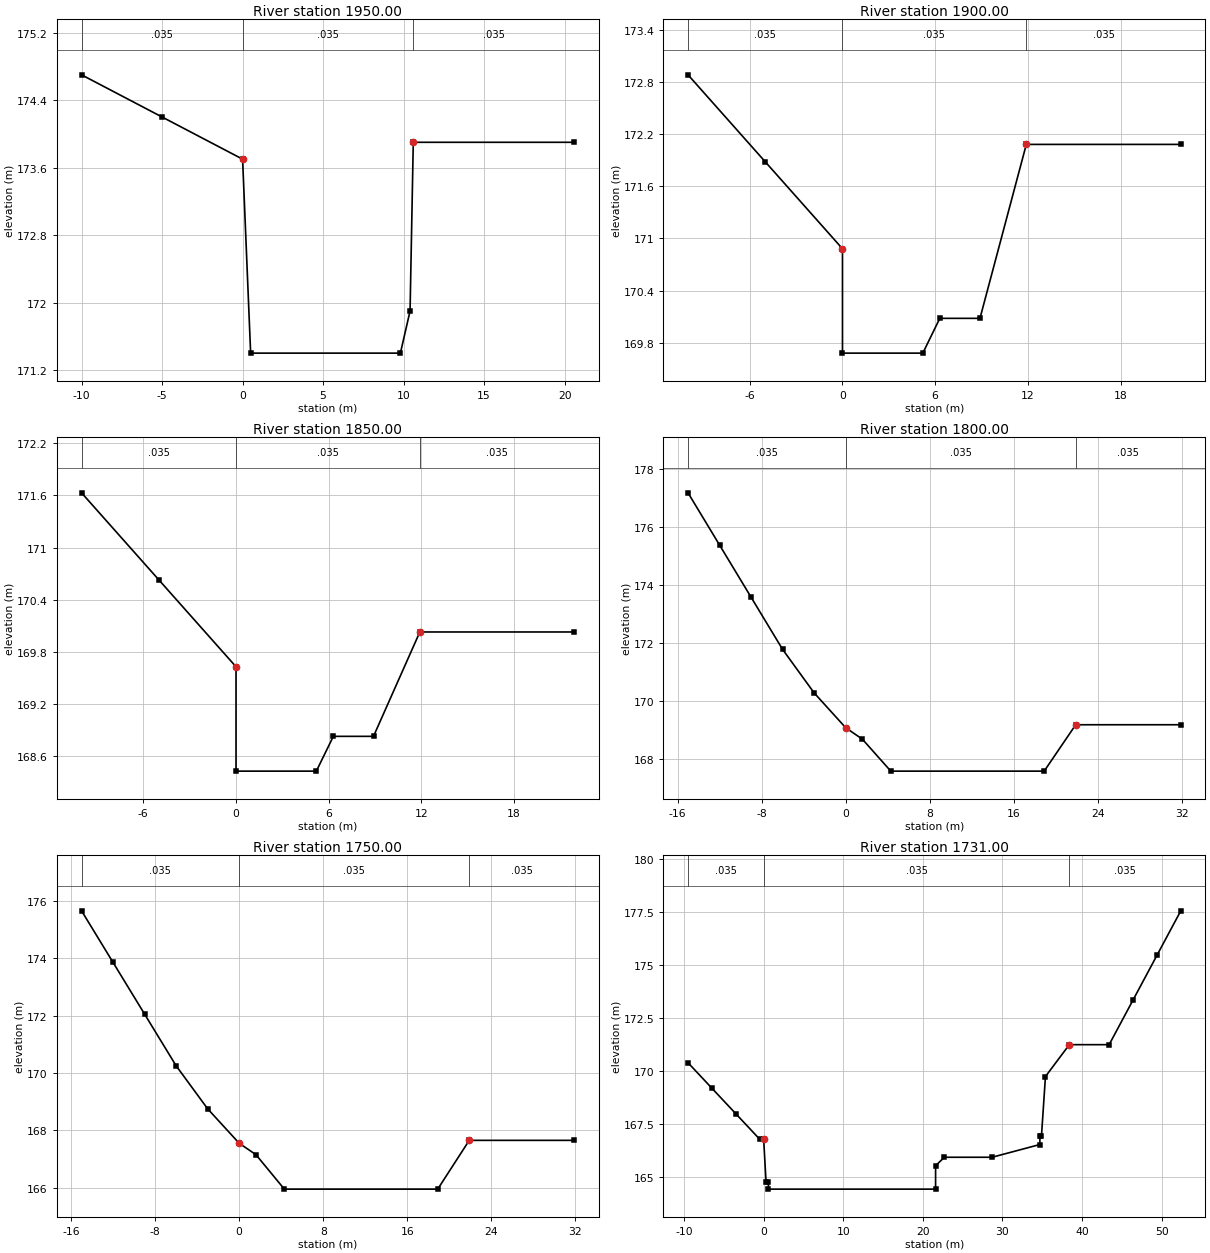
Type RM Length L Ch R = 1 ,1950.00 ,50,50,50
BEGIN DESCRIPTION:
39
END DESCRIPTION:
#Sta/Elev= 8
     -10   174.7      -5   174.2       0   173.7      .5   171.4     9.8   171.4
    10.4   171.9    10.6   173.9    20.6   173.9
#Mann= 3 , 0 , 0
     -10    .035       0       0    .035       0    10.6    .035       0
#XS Ineff= 2 , 0
               0   173.7    10.6           173.9
Permanent Ineff=
       F       F
Bank Sta=0,10.6
XS Rating Curve= 0
Exp/Cntr=.3,.1

Type RM Length L Ch R = 1 ,1900.00 ,50,50,50
BEGIN DESCRIPTION:
38
END DESCRIPTION:
#Sta/Elev= 9
     -10  172.88      -5  171.88       0  170.88       0  169.68     5.2  169.68
     6.3  170.08     8.9  170.08    11.9  172.08    21.9  172.08
#Mann= 3 , 0 , 0
     -10    .035       0       0    .035       0    11.9    .035       0
#XS Ineff= 2 , 0
               0  170.88    11.9          172.08
Permanent Ineff=
       F       F
Bank Sta=0,11.9
XS Rating Curve= 0
Exp/Cntr=.3,.1

Type RM Length L Ch R = 1 ,1850.00 ,50,50,50
BEGIN DESCRIPTION:
37
END DESCRIPTION:
#Sta/Elev= 9
     -10  171.63      -5  170.63       0  169.63       0  168.43     5.2  168.43
     6.3  168.83     8.9  168.83    11.9  170.03    21.9  170.03
#Mann= 3 , 0 , 0
     -10    .035       0       0    .035       0    11.9    .035       0
#XS Ineff= 2 , 0
               0  169.63    11.9          170.03
Permanent Ineff=
       F       F
Bank Sta=0,11.9
XS Rating Curve= 0
Exp/Cntr=.3,.1

Type RM Length L Ch R = 1 ,1800.00 ,50,50,50
BEGIN DESCRIPTION:
36
END DESCRIPTION:
#Sta/Elev= 11
     -15  177.19     -12  175.39      -9  173.59      -6  171.79      -3  170.29
       0  169.09     1.6  168.69     4.3  167.59    18.9  167.59    21.9  169.19
    31.9  169.19
#Mann= 3 , 0 , 0
     -15    .035       0       0    .035       0    21.9    .035       0
#XS Ineff= 2 , 0
               0  169.09    21.9          169.19
Permanent Ineff=
       F       F
Bank Sta=0,21.9
XS Rating Curve= 0
Exp/Cntr=.3,.1

Type RM Length L Ch R = 1 ,1750.00 ,19,19,19
BEGIN DESCRIPTION:
35
END DESCRIPTION:
#Sta/Elev= 11
     -15  175.65     -12  173.85      -9  172.05      -6  170.25      -3  168.75
       0  167.55     1.6  167.15     4.3  165.95    18.9  165.95    21.9  167.65
    31.9  167.65
#Mann= 3 , 0 , 0
     -15    .035       0       0    .035       0    21.9    .035       0
#XS Ineff= 2 , 0
               0  167.55    21.9          167.65
Permanent Ineff=
       F       F
Bank Sta=0,21.9
XS Rating Curve= 0
Exp/Cntr=.3,.1

Type RM Length L Ch R = 1 ,1731.00 ,31,31,31
BEGIN DESCRIPTION:
34.031
END DESCRIPTION:
#Sta/Elev= 21
    -9.5  170.39    -6.5  169.19    -3.5  167.99     -.5  166.79       0  166.79
      .3  164.79      .6  164.79      .6  164.44    21.6  164.44    21.6  165.54
    22.7  165.94    28.7  165.94    34.7  166.54    34.7  166.94    34.9  166.94
    35.4  169.74    38.4  171.24    43.4  171.24    46.4  173.34    49.4  175.44
    52.4  177.54
#Mann= 3 , 0 , 0
    -9.5    .035       0       0    .035       0    38.4    .035       0
#XS Ineff= 2 , 0
       0       0  166.79    38.4       0  171.24
Permanent Ineff=
       F       F
Bank Sta=0,38.4
XS Rating Curve= 0
Exp/Cntr=.3,.1

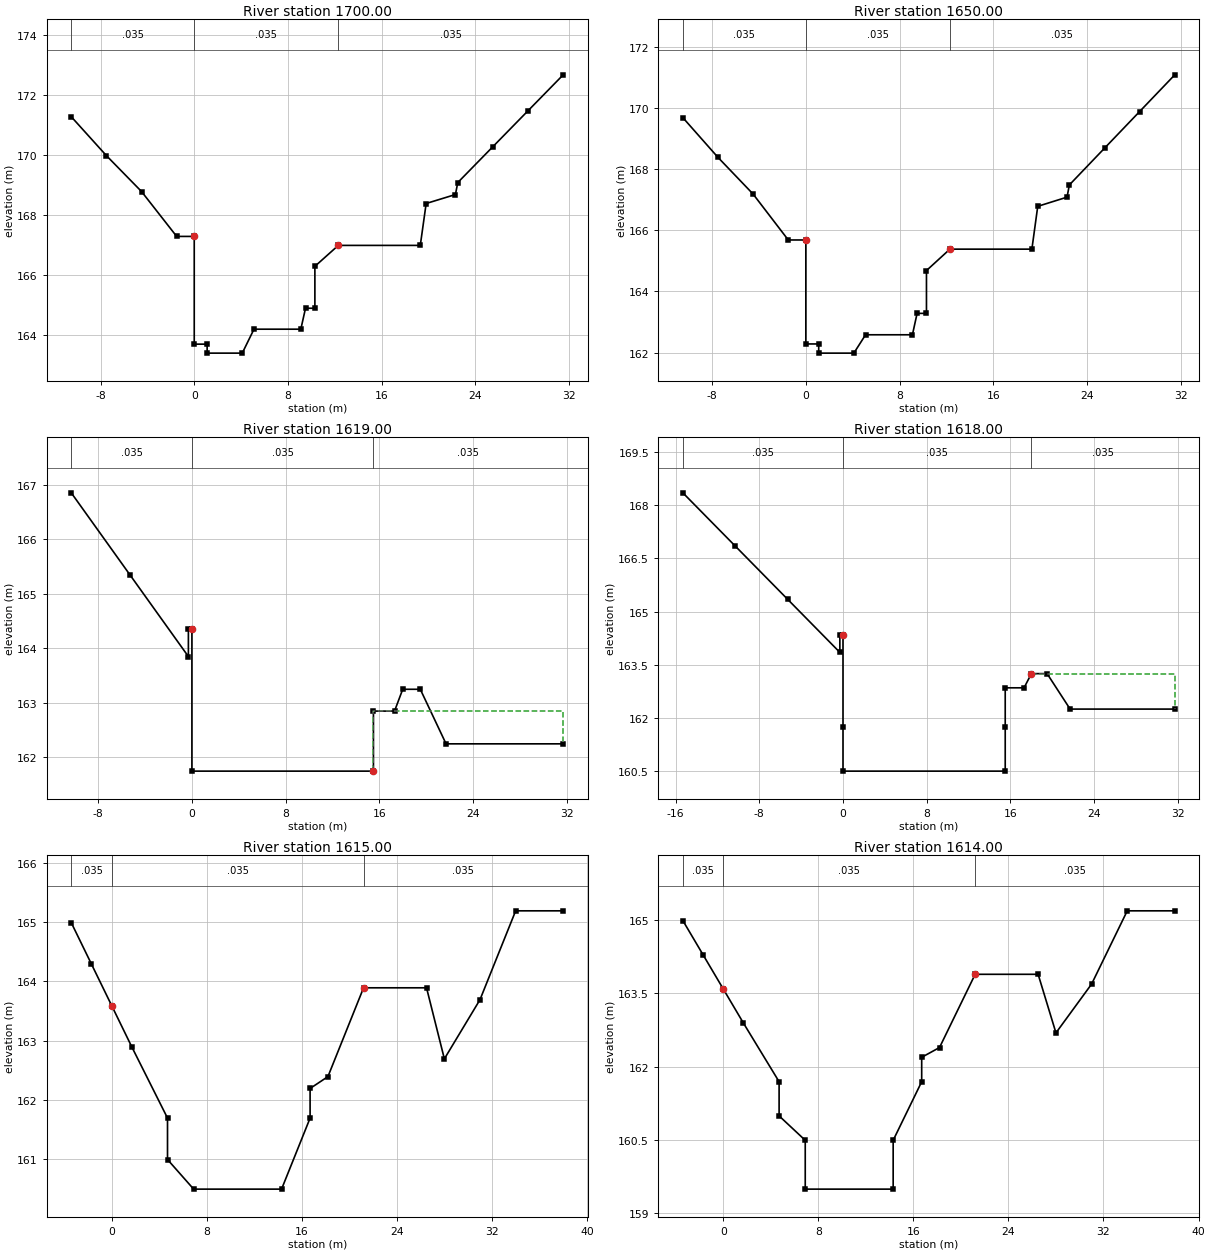
Type RM Length L Ch R = 1 ,1700.00 ,50,50,50
BEGIN DESCRIPTION:
34
END DESCRIPTION:
#Sta/Elev= 22
   -10.5  171.28    -7.5  169.98    -4.5  168.78    -1.5  167.28       0  167.28
       0  163.68     1.1  163.68     1.1  163.38     4.1  163.38     5.1  164.18
     9.1  164.18     9.5  164.88    10.3  164.88    10.3  166.28    12.3  166.98
    19.3  166.98    19.8  168.38    22.3  168.68    22.5  169.08    25.5  170.28
    28.5  171.48    31.5  172.68
#Mann= 3 , 0 , 0
   -10.5    .035       0       0    .035       0    12.3    .035       0
#XS Ineff= 2 , 0
       0       0  167.28    12.3       0  166.98
Permanent Ineff=
       F       F
Bank Sta=0,12.3
XS Rating Curve= 0
Exp/Cntr=.3,.1

Type RM Length L Ch R = 1 ,1650.00 ,31,31,31
BEGIN DESCRIPTION:
33
END DESCRIPTION:
#Sta/Elev= 22
   -10.5  169.68    -7.5  168.38    -4.5  167.18    -1.5  165.68       0  165.68
       0  162.28     1.1  162.28     1.1  161.98     4.1  161.98     5.1  162.58
     9.1  162.58     9.5  163.28    10.3  163.28    10.3  164.68    12.3  165.38
    19.3  165.38    19.8  166.78    22.3  167.08    22.5  167.48    25.5  168.68
    28.5  169.88    31.5  171.08
#Mann= 3 , 0 , 0
   -10.5    .035       0       0    .035       0    12.3    .035       0
#XS Ineff= 2 , 0
               0  165.68    12.3          165.38
Permanent Ineff=
       F       F
Bank Sta=0,12.3
XS Rating Curve= 0
Exp/Cntr=.3,.1

Type RM Length L Ch R = 1 ,1619.00 ,1,1,1
BEGIN DESCRIPTION:
32.019
END DESCRIPTION:
#Sta/Elev= 13
   -10.3  166.85    -5.3  165.35     -.3  163.85     -.3  164.35       0  164.35
       0  161.75    15.5  161.75    15.5  162.85    17.3  162.85      18  163.25
    19.5  163.25    21.7  162.25    31.7  162.25
#Mann= 3 , 0 , 0
   -10.3    .035       0       0    .035       0    15.5    .035       0
#XS Ineff= 2 , 0
               0  164.35    15.5          162.85
Permanent Ineff=
       F       F
Bank Sta=0,15.5
XS Rating Curve= 0
Exp/Cntr=.3,.1

Type RM Length L Ch R = 1 ,1618.00 ,3,3,3
BEGIN DESCRIPTION:
32.018
END DESCRIPTION:
#Sta/Elev= 16
   -15.3  168.35   -10.3  166.85    -5.3  165.35     -.3  163.85     -.3  164.35
       0  164.35       0  161.75       0   160.5    15.5   160.5    15.5  161.75
    15.5  162.85    17.3  162.85      18  163.25    19.5  163.25    21.7  162.25
    31.7  162.25
#Mann= 3 , 0 , 0
   -15.3    .035       0       0    .035       0      18    .035       0
#XS Ineff= 2 , 0
               0  164.35      18          163.25
Permanent Ineff=
       F       F
Bank Sta=0,18
XS Rating Curve= 0
Exp/Cntr=.3,.1

Type RM Length L Ch R = 1 ,1615.00 ,1,1,1
BEGIN DESCRIPTION:
32.015
END DESCRIPTION:
#Sta/Elev= 17
    -3.4  164.99    -1.7  164.29       0  163.59     1.7  162.89     4.7  161.69
     4.7  160.99     6.9  160.49    14.3  160.49    16.7  161.69    16.7  162.19
    18.2  162.39    21.2  163.89    26.5  163.89      28  162.69      31  163.69
      34  165.19      38  165.19
#Mann= 3 , 0 , 0
    -3.4    .035       0       0    .035       0    21.2    .035       0
#XS Ineff= 2 , 0
               0  163.59    21.2          163.89
Permanent Ineff=
       F       F
Bank Sta=0,21.2
XS Rating Curve= 0
Exp/Cntr=.3,.1

Type RM Length L Ch R = 1 ,1614.00 ,14,14,14
BEGIN DESCRIPTION:
32.014
END DESCRIPTION:
#Sta/Elev= 19
    -3.4  164.99    -1.7  164.29       0  163.59     1.7  162.89     4.7  161.69
     4.7  160.99     6.9  160.49     6.9  159.49    14.3  159.49    14.3  160.49
    16.7  161.69    16.7  162.19    18.2  162.39    21.2  163.89    26.5  163.89
      28  162.69      31  163.69      34  165.19      38  165.19
#Mann= 3 , 0 , 0
    -3.4    .035       0       0    .035       0    21.2    .035       0
#XS Ineff= 2 , 0
               0  163.59    21.2          163.89
Permanent Ineff=
       F       F
Bank Sta=0,21.2
XS Rating Curve= 0
Exp/Cntr=.3,.1

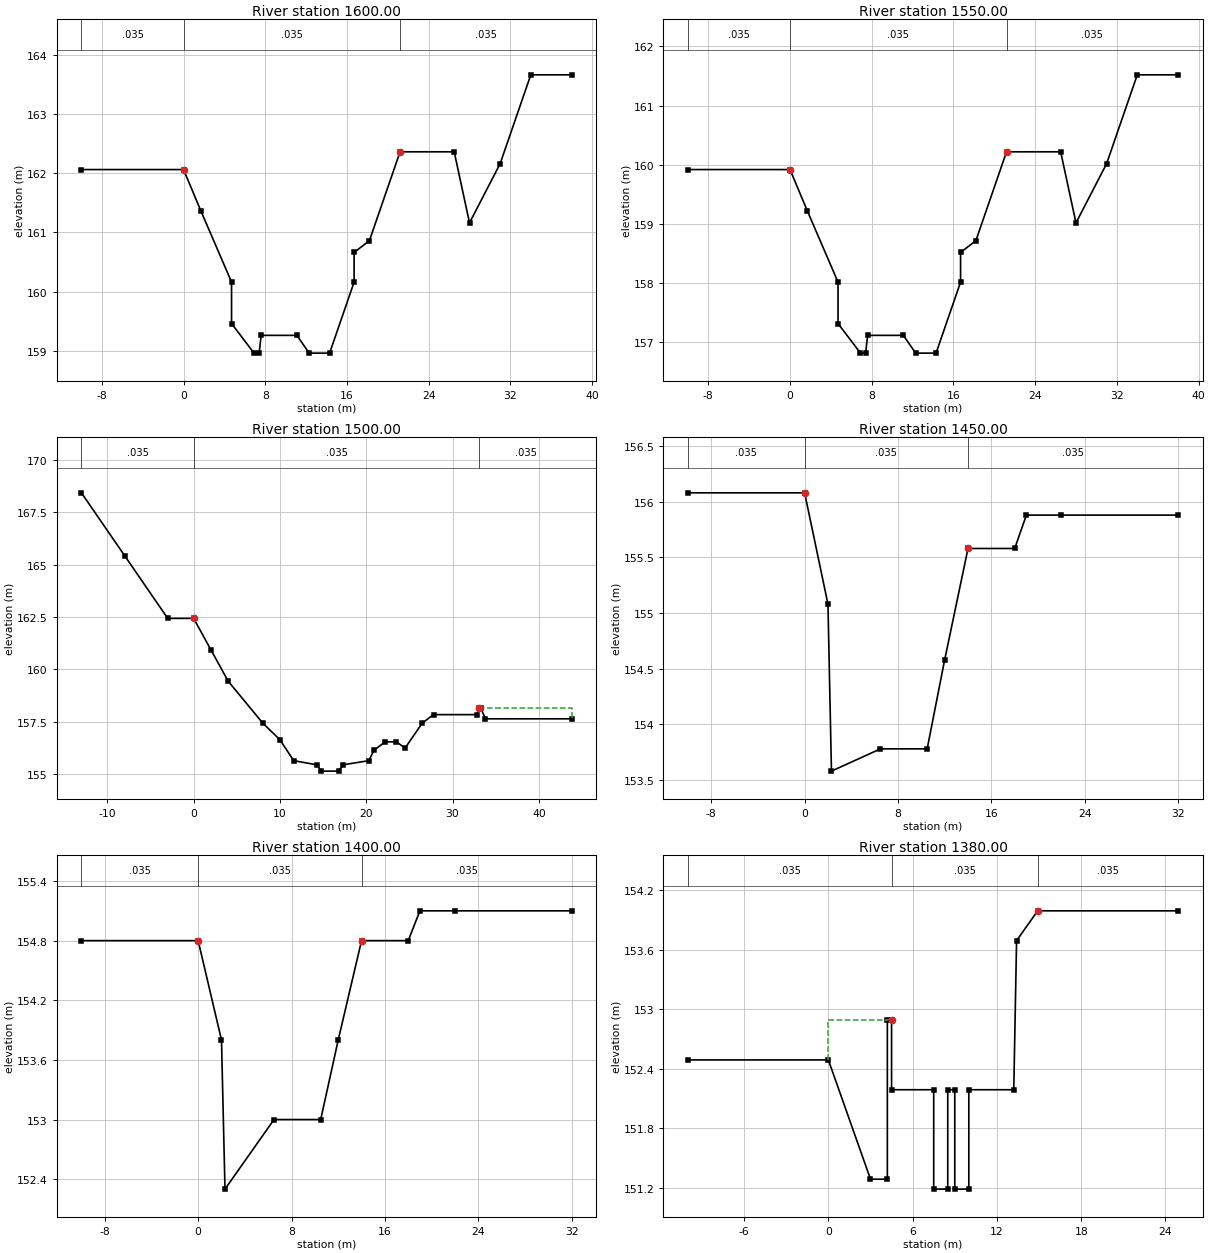
Type RM Length L Ch R = 1 ,1600.00 ,50,50,50
BEGIN DESCRIPTION:
32
END DESCRIPTION:
#Sta/Elev= 20
     -10  162.06       0  162.06     1.7  161.36     4.7  160.16     4.7  159.46
     6.9  158.96     7.4  158.96     7.6  159.26    11.1  159.26    12.3  158.96
    14.3  158.96    16.7  160.16    16.7  160.66    18.2  160.86    21.2  162.36
    26.5  162.36      28  161.16      31  162.16      34  163.66      38  163.66
#Mann= 3 , 0 , 0
     -10    .035       0       0    .035       0    21.2    .035       0
#XS Ineff= 2 , 0
               0  162.06    21.2          162.36
Permanent Ineff=
       F       F
Bank Sta=0,21.2
XS Rating Curve= 0
Exp/Cntr=.3,.1

Type RM Length L Ch R = 1 ,1550.00 ,50,50,50
BEGIN DESCRIPTION:
31
END DESCRIPTION:
#Sta/Elev= 20
     -10  159.92       0  159.92     1.7  159.22     4.7  158.02     4.7  157.32
     6.9  156.82     7.4  156.82     7.6  157.12    11.1  157.12    12.3  156.82
    14.3  156.82    16.7  158.02    16.7  158.52    18.2  158.72    21.2  160.22
    26.5  160.22      28  159.02      31  160.02      34  161.52      38  161.52
#Mann= 3 , 0 , 0
     -10    .035       0       0    .035       0    21.2    .035       0
#XS Ineff= 2 , 0
               0  159.92    21.2          160.22
Permanent Ineff=
       F       F
Bank Sta=0,21.2
XS Rating Curve= 0
Exp/Cntr=.3,.1

Type RM Length L Ch R = 1 ,1500.00 ,50,50,50
BEGIN DESCRIPTION:
30
END DESCRIPTION:
#Sta/Elev= 25
     -13  168.43      -8  165.43      -3  162.43       0  162.43       2  160.93
       4  159.43       8  157.43      10  156.63    11.6  155.63    14.3  155.43
    14.8  155.13    16.8  155.13    17.3  155.43    20.3  155.63    20.9  156.13
    22.2  156.53    23.5  156.53    24.5  156.23    26.5  157.43    27.8  157.83
    32.8  157.83    33.1  158.13    33.3  158.13    33.8  157.63    43.8  157.63
#Mann= 3 , 0 , 0
     -13    .035       0       0    .035       0    33.1    .035       0
#XS Ineff= 2 , 0
               0  162.43    33.1          158.13
Permanent Ineff=
       F       F
Bank Sta=0,33.1
XS Rating Curve= 0
Exp/Cntr=.3,.1

Type RM Length L Ch R = 1 ,1450.00 ,50,50,50
BEGIN DESCRIPTION:
29
END DESCRIPTION:
#Sta/Elev= 12
     -10  156.08       0  156.08       2  155.08     2.3  153.58     6.5  153.78
    10.5  153.78      12  154.58      14  155.58      18  155.58      19  155.88
      22  155.88      32  155.88
#Mann= 3 , 0 , 0
     -10    .035       0       0    .035       0      14    .035       0
#XS Ineff= 2 , 0
               0  156.08      14          155.58
Permanent Ineff=
       F       F
Bank Sta=0,14
XS Rating Curve= 0
Exp/Cntr=.3,.1

Type RM Length L Ch R = 1 ,1400.00 ,20,20,20
BEGIN DESCRIPTION:
28
END DESCRIPTION:
#Sta/Elev= 12
     -10   154.8       0   154.8       2   153.8     2.3   152.3     6.5     153
    10.5     153      12   153.8      14   154.8      18   154.8      19   155.1
      22   155.1      32   155.1
#Mann= 3 , 0 , 0
     -10    .035       0       0    .035       0      14    .035       0
#XS Ineff= 2 , 0
               0   154.8      14           154.8
Permanent Ineff=
       F       F
Bank Sta=0,14
XS Rating Curve= 0
Exp/Cntr=.3,.1

Type RM Length L Ch R = 1 ,1380.00 ,30,30,30
BEGIN DESCRIPTION:
27.03
END DESCRIPTION:
#Sta/Elev= 19
     -10  152.49       0  152.49       3  151.29     4.2  151.29     4.2  152.89
     4.5  152.89     4.5  152.19     7.5  152.19     7.5  151.19     8.5  151.19
     8.5  152.19       9  152.19       9  151.19      10  151.19      10  152.19
    13.2  152.19    13.4  153.69    14.9  153.99    24.9  153.99
#Mann= 3 , 0 , 0
     -10    .035       0     4.5    .035       0    14.9    .035       0
#XS Ineff= 2 , 0
       0     4.5  152.89    14.9       0  153.99
Permanent Ineff=
       F       F
Bank Sta=4.5,14.9
XS Rating Curve= 0
Exp/Cntr=.3,.1

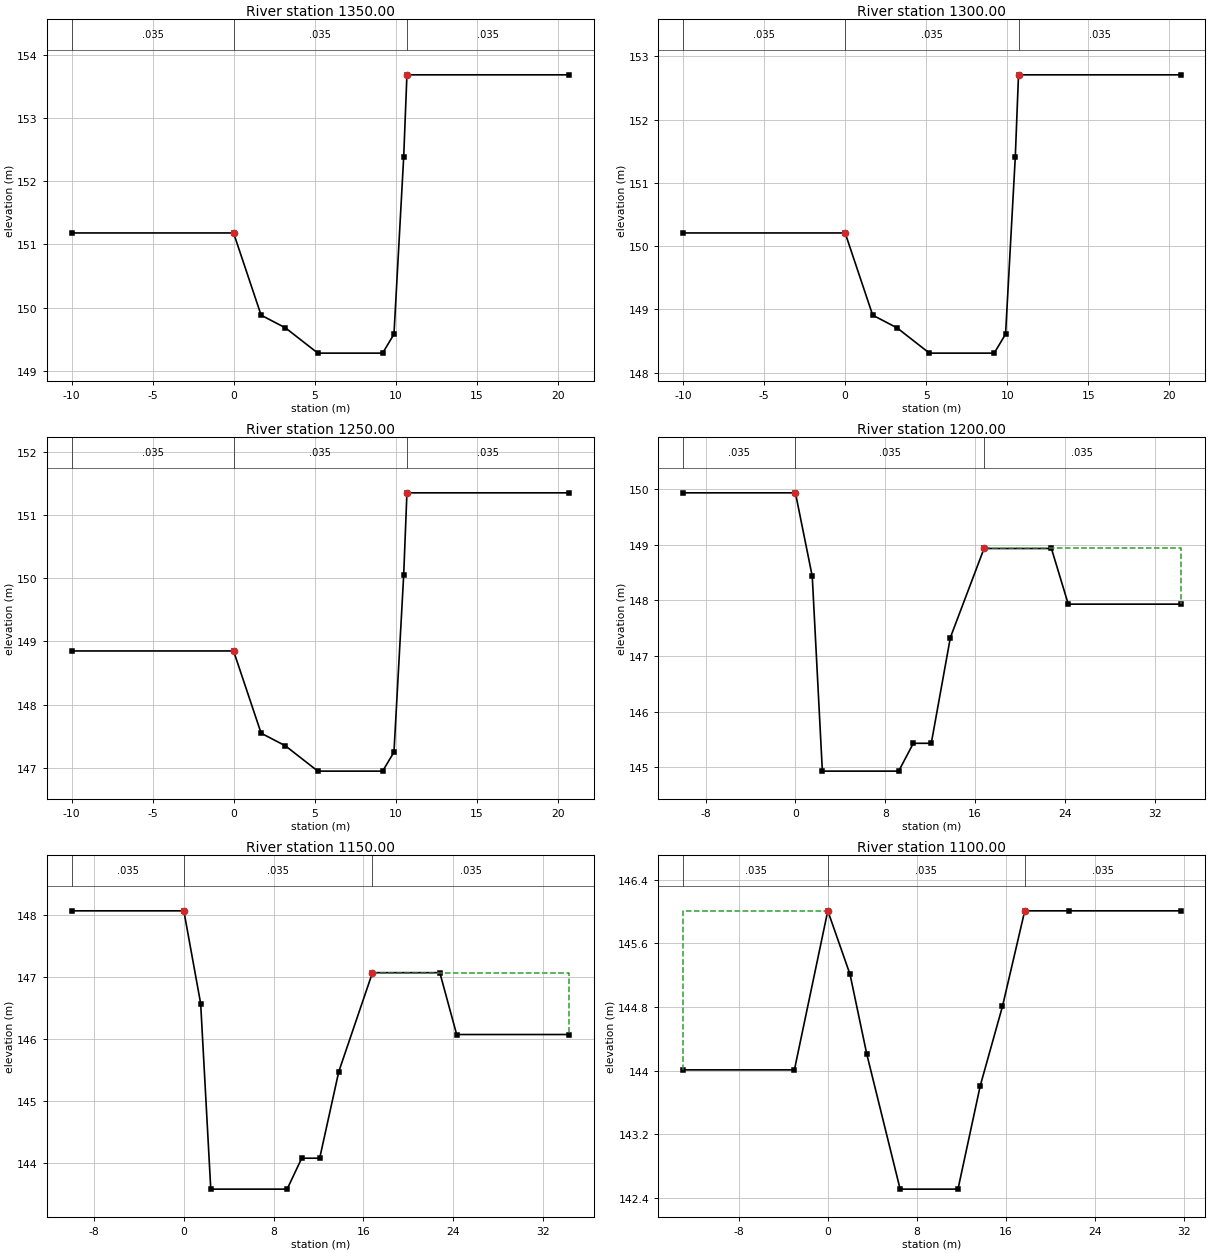
Type RM Length L Ch R = 1 ,1350.00 ,50,50,50
BEGIN DESCRIPTION:
27
END DESCRIPTION:
#Sta/Elev= 10
     -10  151.18       0  151.18     1.7  149.88     3.2  149.68     5.2  149.28
     9.2  149.28     9.9  149.58    10.5  152.38    10.7  153.68    20.7  153.68
#Mann= 3 , 0 , 0
     -10    .035       0       0    .035       0    10.7    .035       0
#XS Ineff= 2 , 0
               0  151.18    10.7          153.68
Permanent Ineff=
       F       F
Bank Sta=0,10.7
XS Rating Curve= 0
Exp/Cntr=.3,.1

Type RM Length L Ch R = 1 ,1300.00 ,50,50,50
BEGIN DESCRIPTION:
26
END DESCRIPTION:
#Sta/Elev= 10
     -10  150.21       0  150.21     1.7  148.91     3.2  148.71     5.2  148.31
     9.2  148.31     9.9  148.61    10.5  151.41    10.7  152.71    20.7  152.71
#Mann= 3 , 0 , 0
     -10    .035       0       0    .035       0    10.7    .035       0
#XS Ineff= 2 , 0
               0  150.21    10.7          152.71
Permanent Ineff=
       F       F
Bank Sta=0,10.7
XS Rating Curve= 0
Exp/Cntr=.3,.1

Type RM Length L Ch R = 1 ,1250.00 ,50,50,50
BEGIN DESCRIPTION:
25
END DESCRIPTION:
#Sta/Elev= 10
     -10  148.85       0  148.85     1.7  147.55     3.2  147.35     5.2  146.95
     9.2  146.95     9.9  147.25    10.5  150.05    10.7  151.35    20.7  151.35
#Mann= 3 , 0 , 0
     -10    .035       0       0    .035       0    10.7    .035       0
#XS Ineff= 2 , 0
               0  148.85    10.7          151.35
Permanent Ineff=
       F       F
Bank Sta=0,10.7
XS Rating Curve= 0
Exp/Cntr=.3,.1

Type RM Length L Ch R = 1 ,1200.00 ,50,50,50
BEGIN DESCRIPTION:
24
END DESCRIPTION:
#Sta/Elev= 12
     -10  149.93       0  149.93     1.5  148.43     2.4  144.93     9.2  144.93
    10.5  145.43    12.1  145.43    13.8  147.33    16.8  148.93    22.8  148.93
    24.3  147.93    34.3  147.93
#Mann= 3 , 0 , 0
     -10    .035       0       0    .035       0    16.8    .035       0
#XS Ineff= 2 , 0
               0  149.93    16.8          148.93
Permanent Ineff=
       F       F
Bank Sta=0,16.8
XS Rating Curve= 0
Exp/Cntr=.3,.1

Type RM Length L Ch R = 1 ,1150.00 ,50,50,50
BEGIN DESCRIPTION:
23
END DESCRIPTION:
#Sta/Elev= 12
     -10  148.07       0  148.07     1.5  146.57     2.4  143.57     9.2  143.57
    10.5  144.07    12.1  144.07    13.8  145.47    16.8  147.07    22.8  147.07
    24.3  146.07    34.3  146.07
#Mann= 3 , 0 , 0
     -10    .035       0       0    .035       0    16.8    .035       0
#XS Ineff= 2 , 0
               0  148.07    16.8          147.07
Permanent Ineff=
       F       F
Bank Sta=0,16.8
XS Rating Curve= 0
Exp/Cntr=.3,.1

Type RM Length L Ch R = 1 ,1100.00 ,50,50,50
BEGIN DESCRIPTION:
22
END DESCRIPTION:
#Sta/Elev= 12
     -13  144.01      -3  144.01       0  146.01       2  145.21     3.5  144.21
     6.5  142.51    11.7  142.51    13.7  143.81    15.7  144.81    17.7  146.01
    21.7  146.01    31.7  146.01
#Mann= 3 , 0 , 0
     -13    .035       0       0    .035       0    17.7    .035       0
#XS Ineff= 2 , 0
               0  146.01    17.7          146.01
Permanent Ineff=
       F       F
Bank Sta=0,17.7
XS Rating Curve= 0
Exp/Cntr=.3,.1