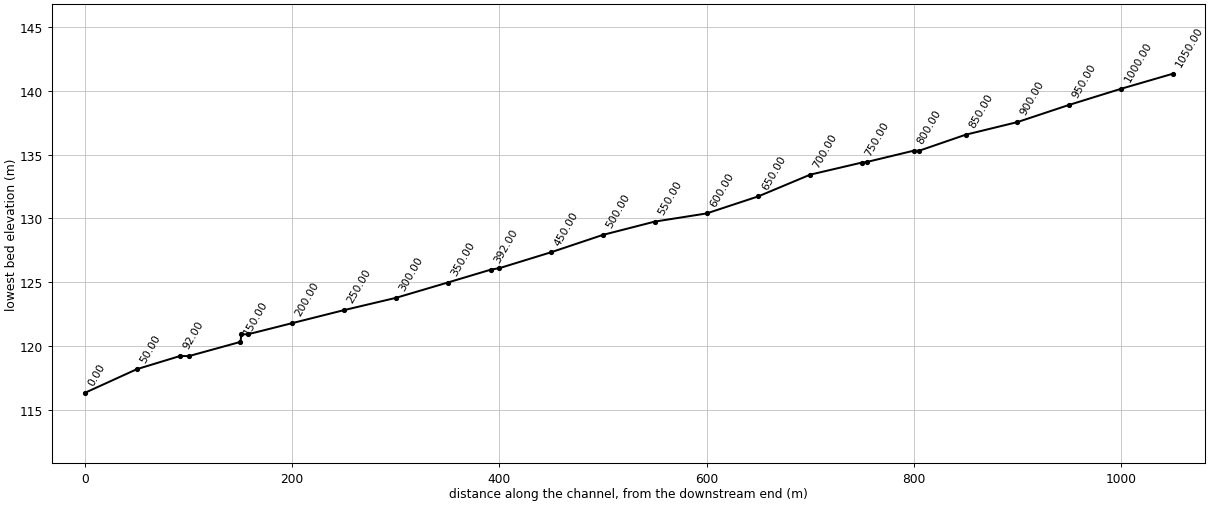
HEC-RAS study JKC.prj: jogae-ch

--- JKC.g01 (geometry) --- (continued)

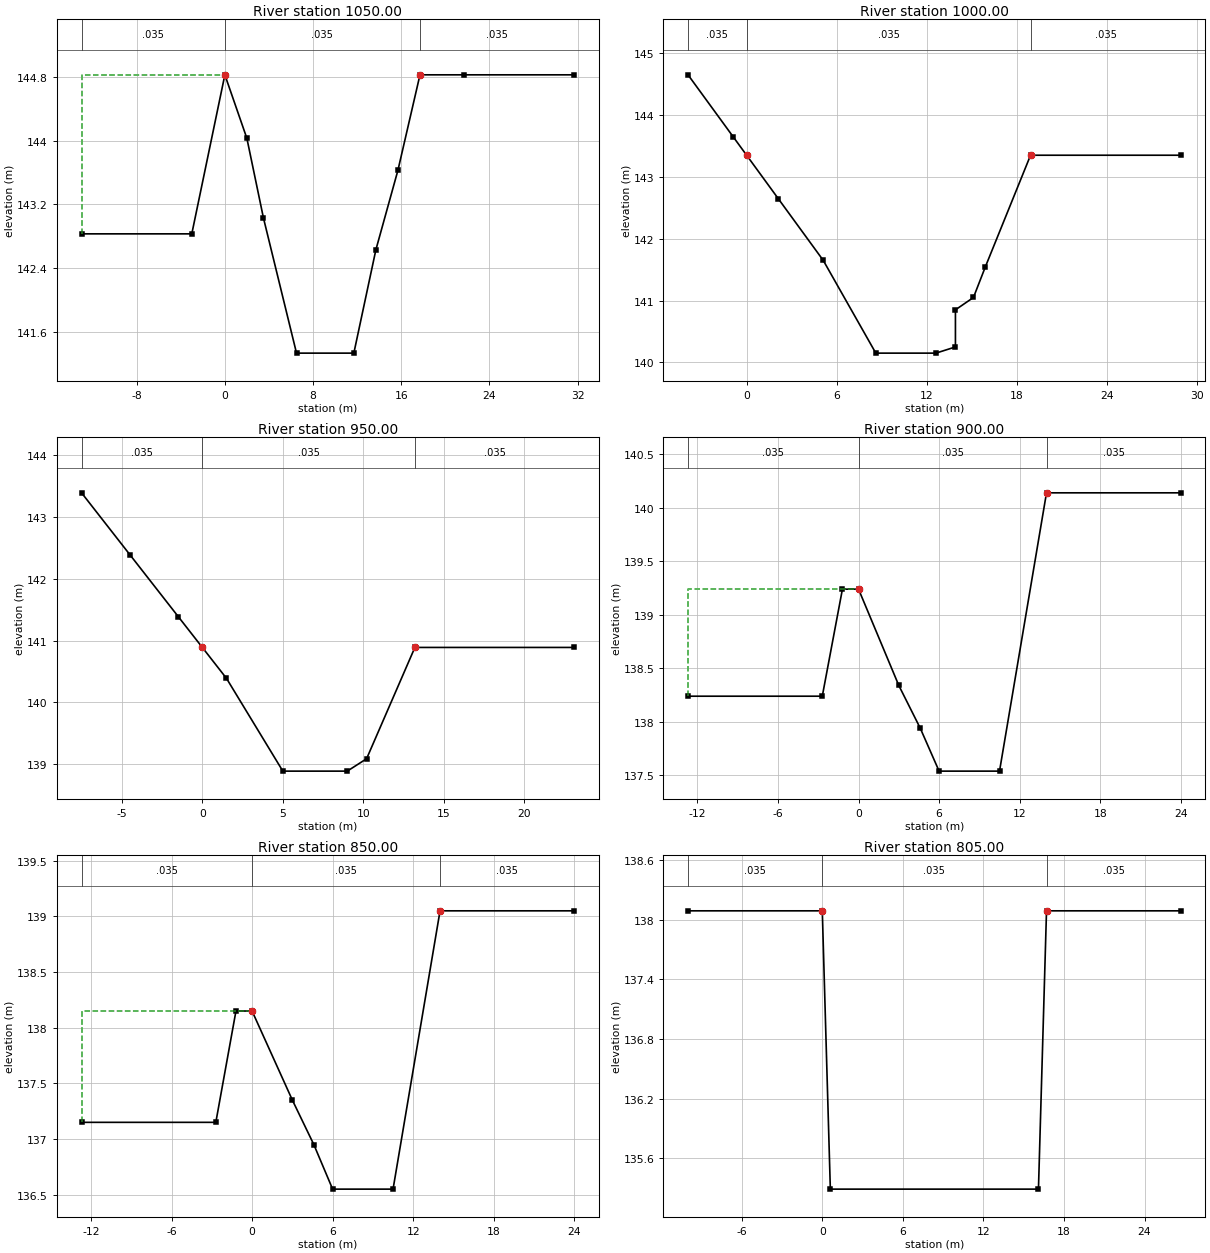
Type RM Length L Ch R = 1 ,1050.00 ,50,50,50
BEGIN DESCRIPTION:
21
END DESCRIPTION:
#Sta/Elev= 12
     -13  142.83      -3  142.83       0  144.83       2  144.03     3.5  143.03
     6.5  141.33    11.7  141.33    13.7  142.63    15.7  143.63    17.7  144.83
    21.7  144.83    31.7  144.83
#Mann= 3 , 0 , 0
     -13    .035       0       0    .035       0    17.7    .035       0
#XS Ineff= 2 , 0
               0  144.83    17.7          144.83
Permanent Ineff=
       F       F
Bank Sta=0,17.7
XS Rating Curve= 0
Exp/Cntr=.3,.1

Type RM Length L Ch R = 1 ,1000.00 ,50,50,50
BEGIN DESCRIPTION:
20
END DESCRIPTION:
#Sta/Elev= 13
    -3.9  144.65     -.9  143.65       0  143.35     2.1  142.65     5.1  141.65
     8.6  140.15    12.6  140.15    13.9  140.25    13.9  140.85    15.1  141.05
    15.9  141.55    18.9  143.35    28.9  143.35
#Mann= 3 , 0 , 0
    -3.9    .035       0       0    .035       0    18.9    .035       0
#XS Ineff= 2 , 0
               0  143.35    18.9          143.35
Permanent Ineff=
       F       F
Bank Sta=0,18.9
XS Rating Curve= 0
Exp/Cntr=.3,.1

Type RM Length L Ch R = 1 ,950.00  ,50,50,50
BEGIN DESCRIPTION:
19
END DESCRIPTION:
#Sta/Elev= 10
    -7.5  143.39    -4.5  142.39    -1.5  141.39       0  140.89     1.5  140.39
       5  138.89       9  138.89    10.2  139.09    13.2  140.89    23.1  140.89
#Mann= 3 , 0 , 0
    -7.5    .035       0       0    .035       0    13.2    .035       0
#XS Ineff= 2 , 0
               0  140.89    13.2          140.89
Permanent Ineff=
       F       F
Bank Sta=0,13.2
XS Rating Curve= 0
Exp/Cntr=.3,.1

Type RM Length L Ch R = 1 ,900.00  ,50,50,50
BEGIN DESCRIPTION:
18
END DESCRIPTION:
#Sta/Elev= 10
   -12.7  138.24    -2.7  138.24    -1.2  139.24       0  139.24       3  138.34
     4.6  137.94       6  137.54    10.5  137.54      14  140.14      24  140.14
#Mann= 3 , 0 , 0
   -12.7    .035       0       0    .035       0      14    .035       0
#XS Ineff= 2 , 0
               0  139.24      14          140.14
Permanent Ineff=
       F       F
Bank Sta=0,14
XS Rating Curve= 0
Exp/Cntr=.3,.1

Type RM Length L Ch R = 1 ,850.00  ,45,45,45
BEGIN DESCRIPTION:
17
END DESCRIPTION:
#Sta/Elev= 10
   -12.7  137.15    -2.7  137.15    -1.2  138.15       0  138.15       3  137.35
     4.6  136.95       6  136.55    10.5  136.55      14  139.05      24  139.05
#Mann= 3 , 0 , 0
   -12.7    .035       0       0    .035       0      14    .035       0
#XS Ineff= 2 , 0
               0  138.15      14          139.05
Permanent Ineff=
       F       F
Bank Sta=0,14
XS Rating Curve= 0
Exp/Cntr=.3,.1

Type RM Length L Ch R = 1 ,805.00  ,5,5,5
BEGIN DESCRIPTION:
16.005
END DESCRIPTION:
#Sta/Elev= 6
     -10  138.09       0  138.09      .6  135.29    16.1  135.29    16.7  138.09
    26.7  138.09
#Mann= 3 , 0 , 0
     -10    .035       0       0    .035       0    16.7    .035       0
#XS Ineff= 2 , 0
               0  138.09    16.7          138.09
Permanent Ineff=
       F       F
Bank Sta=0,16.7
XS Rating Curve= 0
Exp/Cntr=.3,.1

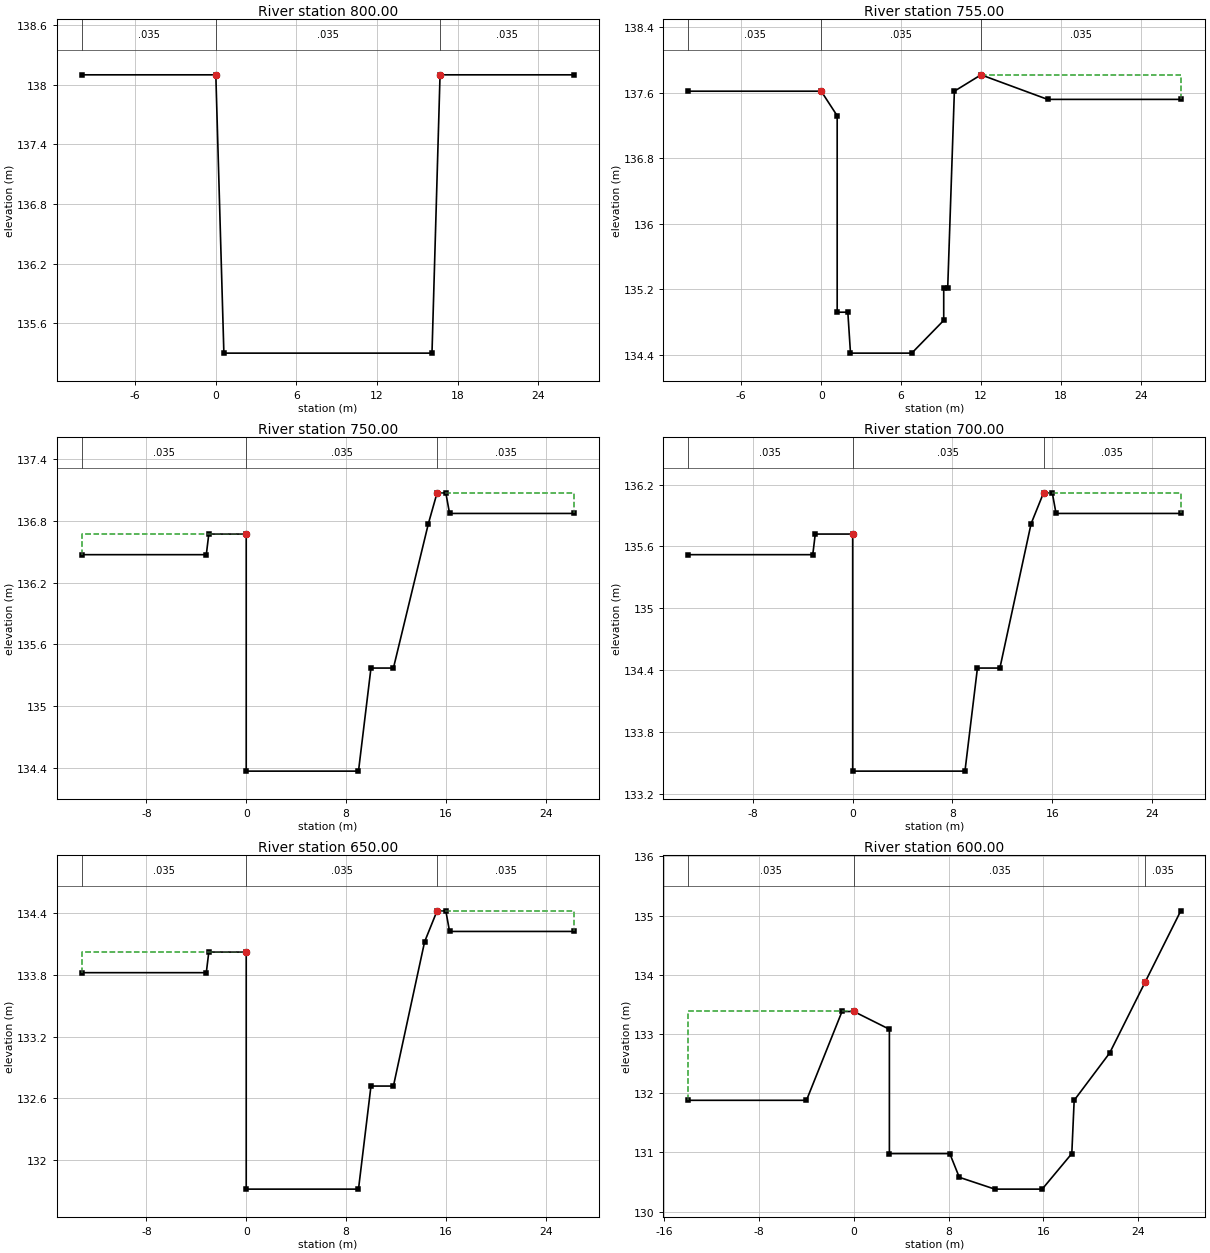
Type RM Length L Ch R = 1 ,800.00  ,45,45,45
BEGIN DESCRIPTION:
16
END DESCRIPTION:
#Sta/Elev= 6
     -10   138.1       0   138.1      .6   135.3    16.1   135.3    16.7   138.1
    26.7   138.1
#Mann= 3 , 0 , 0
     -10    .035       0       0    .035       0    16.7    .035       0
#XS Ineff= 2 , 0
               0   138.1    16.7           138.1
Permanent Ineff=
       F       F
Bank Sta=0,16.7
XS Rating Curve= 0
Exp/Cntr=.3,.1

Type RM Length L Ch R = 1 ,755.00  ,5,5,5
BEGIN DESCRIPTION:
15.005
END DESCRIPTION:
#Sta/Elev= 14
     -10  137.62       0  137.62     1.2  137.32     1.2  134.92       2  134.92
     2.2  134.42     6.8  134.42     9.2  134.82     9.2  135.22     9.5  135.22
      10  137.62      12  137.82      17  137.52      27  137.52
#Mann= 3 , 0 , 0
     -10    .035       0       0    .035       0      12    .035       0
#XS Ineff= 2 , 0
               0  137.62      12          137.82
Permanent Ineff=
       F       F
Bank Sta=0,12
XS Rating Curve= 0
Exp/Cntr=.3,.1

Type RM Length L Ch R = 1 ,750.00  ,50,50,50
BEGIN DESCRIPTION:
15
END DESCRIPTION:
#Sta/Elev= 13
   -13.2  136.47    -3.2  136.47      -3  136.67       0  136.67       0  134.37
       9  134.37      10  135.37    11.8  135.37    14.6  136.77    15.3  137.07
      16  137.07    16.3  136.87    26.3  136.87
#Mann= 3 , 0 , 0
   -13.2    .035       0       0    .035       0    15.3    .035       0
#XS Ineff= 2 , 0
               0  136.67    15.3          137.07
Permanent Ineff=
       F       F
Bank Sta=0,15.3
XS Rating Curve= 0
Exp/Cntr=.3,.1

Type RM Length L Ch R = 1 ,700.00  ,50,50,50
BEGIN DESCRIPTION:
14
END DESCRIPTION:
#Sta/Elev= 13
   -13.2  135.52    -3.2  135.52      -3  135.72       0  135.72       0  133.42
       9  133.42      10  134.42    11.8  134.42    14.3  135.82    15.3  136.12
      16  136.12    16.3  135.92    26.3  135.92
#Mann= 3 , 0 , 0
   -13.2    .035       0       0    .035       0    15.3    .035       0
#XS Ineff= 2 , 0
       0       0  135.72    15.3       0  136.12
Permanent Ineff=
       F       F
Bank Sta=0,15.3
XS Rating Curve= 0
Exp/Cntr=.3,.1

Type RM Length L Ch R = 1 ,650.00  ,50,50,50
BEGIN DESCRIPTION:
13
END DESCRIPTION:
#Sta/Elev= 13
   -13.2  133.82    -3.2  133.82      -3  134.02       0  134.02       0  131.72
       9  131.72      10  132.72    11.8  132.72    14.3  134.12    15.3  134.42
      16  134.42    16.3  134.22    26.3  134.22
#Mann= 3 , 0 , 0
   -13.2    .035       0       0    .035       0    15.3    .035       0
#XS Ineff= 2 , 0
               0  134.02    15.3          134.42
Permanent Ineff=
       F       F
Bank Sta=0,15.3
XS Rating Curve= 0
Exp/Cntr=.3,.1

Type RM Length L Ch R = 1 ,600.00  ,50,50,50
BEGIN DESCRIPTION:
12
END DESCRIPTION:
#Sta/Elev= 15
     -14  131.88      -4  131.88      -1  133.38       0  133.38       3  133.08
       3  130.98     8.1  130.98     8.9  130.58    11.9  130.38    15.9  130.38
    18.4  130.98    18.6  131.88    21.6  132.68    24.6  133.88    27.6  135.08
#Mann= 3 , 0 , 0
     -14    .035       0       0    .035       0    24.6    .035       0
#XS Ineff= 2 , 0
               0  133.38    24.6          133.88
Permanent Ineff=
       F       F
Bank Sta=0,24.6
XS Rating Curve= 0
Exp/Cntr=.3,.1

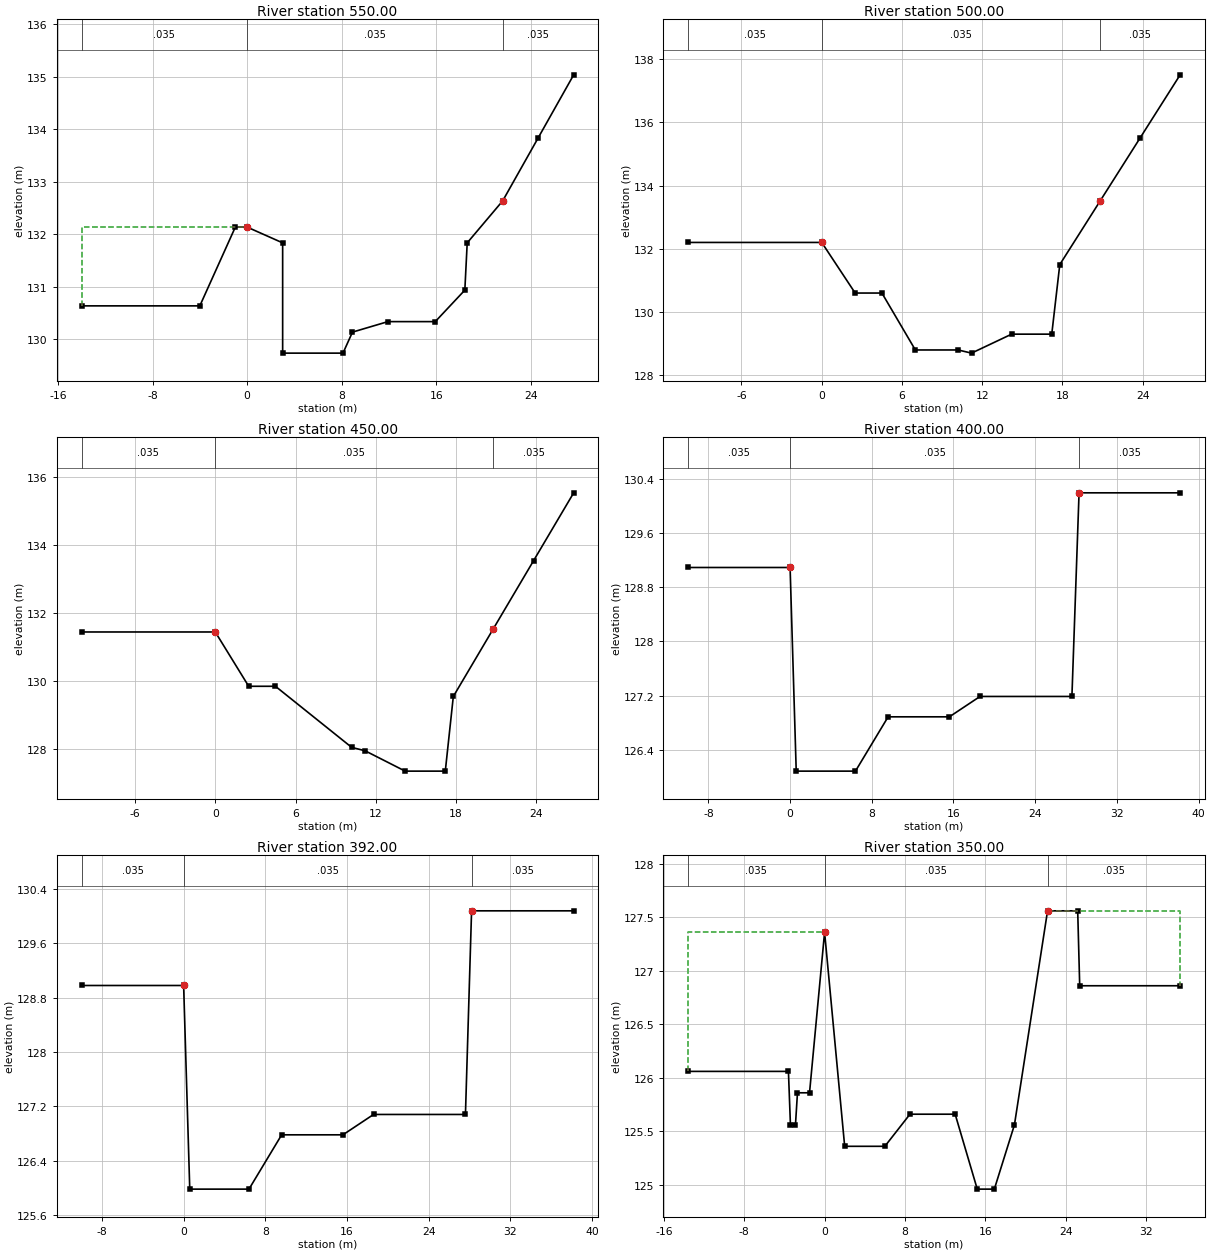
Type RM Length L Ch R = 1 ,550.00  ,50,50,50
BEGIN DESCRIPTION:
11
END DESCRIPTION:
#Sta/Elev= 15
     -14  130.64      -4  130.64      -1  132.14       0  132.14       3  131.84
       3  129.74     8.1  129.74     8.9  130.14    11.9  130.34    15.9  130.34
    18.4  130.94    18.6  131.84    21.6  132.64    24.6  133.84    27.6  135.04
#Mann= 3 , 0 , 0
     -14    .035       0       0    .035       0    21.6    .035       0
#XS Ineff= 2 , 0
               0  132.14    21.6          132.64
Permanent Ineff=
       F       F
Bank Sta=0,21.6
XS Rating Curve= 0
Exp/Cntr=.3,.1

Type RM Length L Ch R = 1 ,500.00  ,50,50,50
BEGIN DESCRIPTION:
10
END DESCRIPTION:
#Sta/Elev= 13
     -10   132.2       0   132.2     2.5   130.6     4.5   130.6       7   128.8
    10.2   128.8    11.2   128.7    14.2   129.3    17.2   129.3    17.8   131.5
    20.8   133.5    23.8   135.5    26.8   137.5
#Mann= 3 , 0 , 0
     -10    .035       0       0    .035       0    20.8    .035       0
#XS Ineff= 2 , 0
               0   132.2    20.8           133.5
Permanent Ineff=
       F       F
Bank Sta=0,20.8
XS Rating Curve= 0
Exp/Cntr=.3,.1

Type RM Length L Ch R = 1 ,450.00  ,50,50,50
BEGIN DESCRIPTION:
9
END DESCRIPTION:
#Sta/Elev= 12
     -10  131.44       0  131.44     2.5  129.84     4.5  129.84    10.2  128.04
    11.2  127.94    14.2  127.34    17.2  127.34    17.8  129.54    20.8  131.54
    23.8  133.54    26.8  135.54
#Mann= 3 , 0 , 0
     -10    .035       0       0    .035       0    20.8    .035       0
#XS Ineff= 2 , 0
               0  131.44    20.8          131.54
Permanent Ineff=
       F       F
Bank Sta=0,20.8
XS Rating Curve= 0
Exp/Cntr=.3,.1

Type RM Length L Ch R = 1 ,400.00  ,8,8,8
BEGIN DESCRIPTION:
8
END DESCRIPTION:
#Sta/Elev= 10
     -10  129.09       0  129.09      .6  126.09     6.4  126.09     9.6  126.89
    15.6  126.89    18.6  127.19    27.6  127.19    28.3  130.19    38.2  130.19
#Mann= 3 , 0 , 0
     -10    .035       0       0    .035       0    28.3    .035       0
#XS Ineff= 2 , 0
       0       0  129.09    28.3       0  130.19
Permanent Ineff=
       F       F
Bank Sta=0,28.3
XS Rating Curve= 0
Exp/Cntr=.3,.1

Type RM Length L Ch R = 1 ,392.00  ,42,42,42
BEGIN DESCRIPTION:
7.042
END DESCRIPTION:
#Sta/Elev= 10
     -10  128.98       0  128.98      .6  125.98     6.4  125.98     9.6  126.78
    15.6  126.78    18.6  127.08    27.6  127.08    28.2  130.08    38.2  130.08
#Mann= 3 , 0 , 0
     -10    .035       0       0    .035       0    28.2    .035       0
#XS Ineff= 2 , 0
               0  128.98    28.2          130.08
Permanent Ineff=
       F       F
Bank Sta=0,28.2
XS Rating Curve= 0
Exp/Cntr=.3,.1

Type RM Length L Ch R = 1 ,350.00  ,50,50,50
BEGIN DESCRIPTION:
7
END DESCRIPTION:
#Sta/Elev= 18
   -13.6  126.06    -3.6  126.06    -3.4  125.56    -2.9  125.56    -2.7  125.86
    -1.5  125.86       0  127.36       2  125.36       6  125.36     8.5  125.66
      13  125.66    15.2  124.96    16.9  124.96    18.9  125.56    22.2  127.56
    25.2  127.56    25.4  126.86    35.4  126.86
#Mann= 3 , 0 , 0
   -13.6    .035       0       0    .035       0    22.2    .035       0
#XS Ineff= 2 , 0
               0  127.36    22.2          127.56
Permanent Ineff=
       F       F
Bank Sta=0,22.2
XS Rating Curve= 0
Exp/Cntr=.3,.1

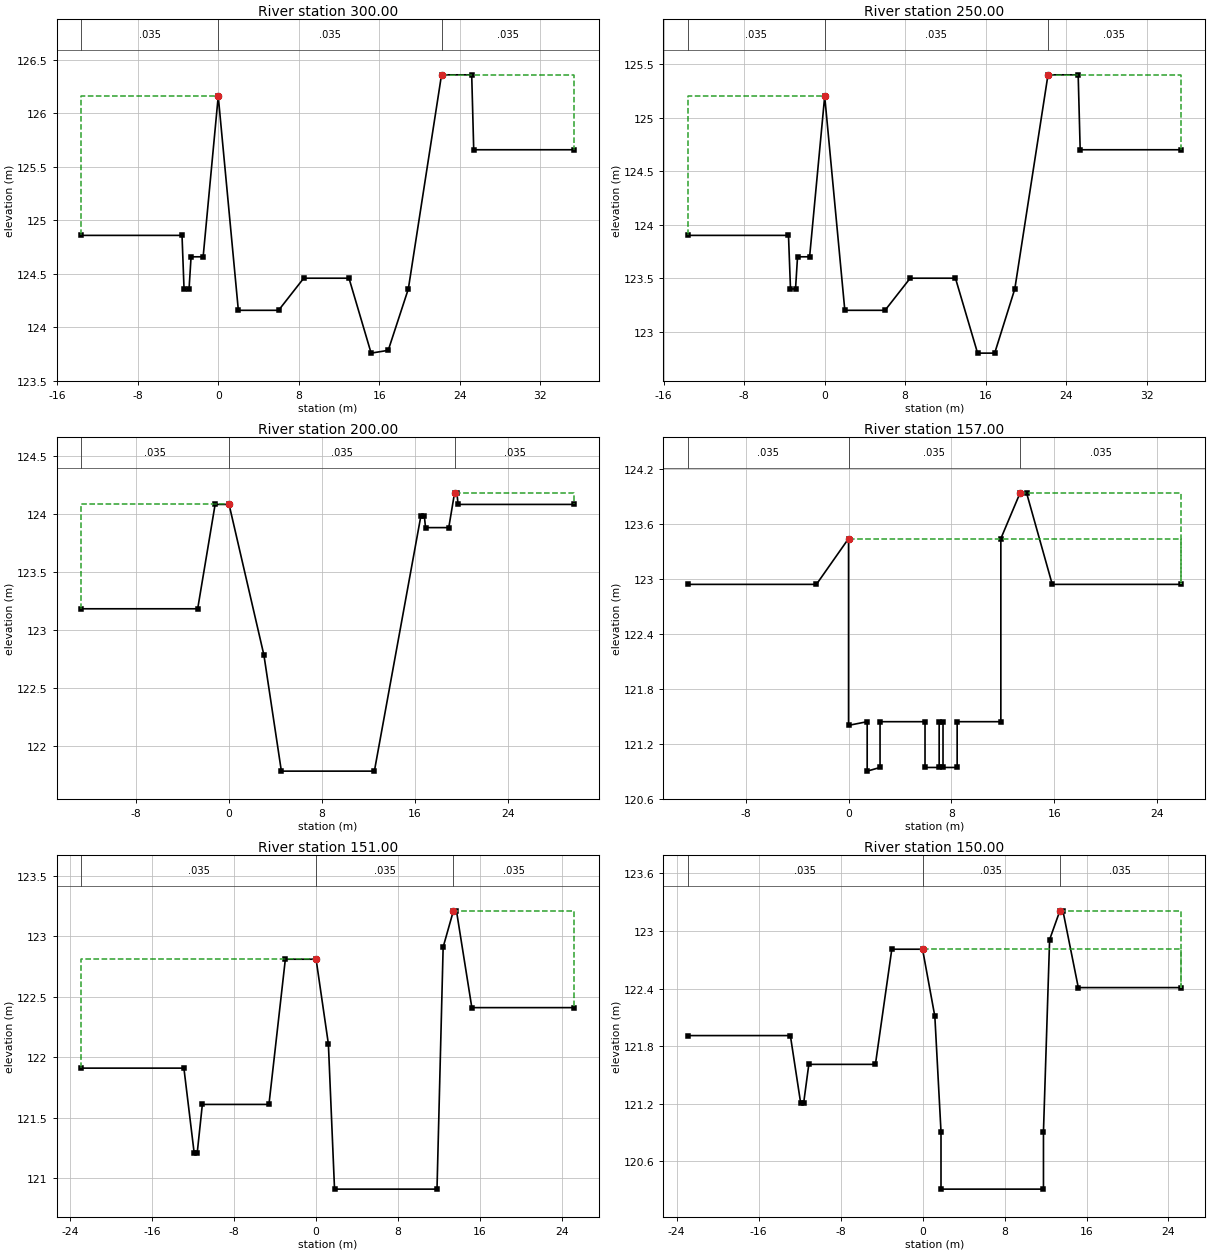
Type RM Length L Ch R = 1 ,300.00  ,50,50,50
BEGIN DESCRIPTION:
6
END DESCRIPTION:
#Sta/Elev= 18
   -13.6  124.86    -3.6  124.86    -3.4  124.36    -2.9  124.36    -2.7  124.66
    -1.5  124.66       0  126.16       2  124.16       6  124.16     8.5  124.46
      13  124.46    15.2  123.76    16.9 123.786    18.9  124.36    22.2  126.36
    25.2  126.36    25.4  125.66    35.4  125.66
#Mann= 3 , 0 , 0
   -13.6    .035       0       0    .035       0    22.2    .035       0
#XS Ineff= 2 , 0
               0  126.16    22.2          126.36
Permanent Ineff=
       F       F
Bank Sta=0,22.2
XS Rating Curve= 0
Exp/Cntr=.3,.1

Type RM Length L Ch R = 1 ,250.00  ,50,50,50
BEGIN DESCRIPTION:
5
END DESCRIPTION:
#Sta/Elev= 18
   -13.6   123.9    -3.6   123.9    -3.4   123.4    -2.9   123.4    -2.7   123.7
    -1.5   123.7       0   125.2       2   123.2       6   123.2     8.5   123.5
      13   123.5    15.2   122.8    16.9   122.8    18.9   123.4    22.2   125.4
    25.2   125.4    25.4   124.7    35.4   124.7
#Mann= 3 , 0 , 0
   -13.6    .035       0       0    .035       0    22.2    .035       0
#XS Ineff= 2 , 0
               0   125.2    22.2           125.4
Permanent Ineff=
       F       F
Bank Sta=0,22.2
XS Rating Curve= 0
Exp/Cntr=.3,.1

Type RM Length L Ch R = 1 ,200.00  ,43,43,43
BEGIN DESCRIPTION:
4
END DESCRIPTION:
#Sta/Elev= 15
   -12.7  123.18    -2.7  123.18    -1.2  124.08       0  124.08       3  122.78
     4.5  121.78    12.5  121.78    16.5  123.98    16.8  123.98    16.9  123.88
    18.9  123.88    19.4  124.18    19.6  124.18    19.7  124.08    29.7  124.08
#Mann= 3 , 0 , 0
   -12.7    .035       0       0    .035       0    19.4    .035       0
#XS Ineff= 2 , 0
               0  124.08    19.4          124.18
Permanent Ineff=
       F       F
Bank Sta=0,19.4
XS Rating Curve= 0
Exp/Cntr=.3,.1

Type RM Length L Ch R = 1 ,157.00  ,6,6,6
BEGIN DESCRIPTION:
3.007
END DESCRIPTION:
#Sta/Elev= 22
   -12.5  122.94    -2.5  122.94       0  123.44       0   121.4    1.45  121.44
    1.45   120.9    2.45  120.94    2.45  121.44    5.95  121.44    5.95  120.94
    7.05  120.94    7.05  121.44    7.35  121.44    7.35  120.94    8.45  120.94
    8.45  121.44   11.85  121.44   11.85  123.44   13.35  123.94   13.85  123.94
   15.85  122.94   25.85  122.94
#Mann= 3 , 0 , 0
   -12.5    .035       0       0    .035       0   13.35    .035       0
#XS Ineff= 2 , 0
       0       0  123.44   13.35       0  123.94
Permanent Ineff=
       F       F
Bank Sta=0,13.35
XS Rating Curve= 0
Exp/Cntr=.3,.1

Type RM Length L Ch R = 1 ,151.00  ,1,1,1
BEGIN DESCRIPTION:
3.001
END DESCRIPTION:
#Sta/Elev= 16
   -22.9  121.91   -12.9  121.91   -11.9  121.21   -11.6  121.21   -11.1  121.61
    -4.6  121.61      -3  122.81       0  122.81     1.2  122.11     1.8  120.91
    11.8  120.91    12.4  122.91    13.4  123.21    13.7  123.21    15.2  122.41
    25.2  122.41
#Mann= 3 , 0 , 0
   -22.9    .035       0       0    .035       0    13.4    .035       0
#XS Ineff= 2 , 0
               0  122.81    13.4          123.21
Permanent Ineff=
       F       F
Bank Sta=0,13.4
XS Rating Curve= 0
Exp/Cntr=.3,.1

Type RM Length L Ch R = 1 ,150.00  ,50,50,50
BEGIN DESCRIPTION:
3
END DESCRIPTION:
#Sta/Elev= 18
   -22.9  121.91   -12.9  121.91   -11.9  121.21   -11.6  121.21   -11.1  121.61
    -4.6  121.61      -3  122.81       0  122.81     1.2  122.11     1.8  120.91
     1.8  120.31    11.8  120.31    11.8  120.91    12.4  122.91    13.4  123.21
    13.7  123.21    15.2  122.41    25.2  122.41
#Mann= 3 , 0 , 0
   -22.9    .035       0       0    .035       0    13.4    .035       0
#XS Ineff= 2 , 0
       0       0  122.81    13.4       0  123.21
Permanent Ineff=
       F       F
Bank Sta=0,13.4
XS Rating Curve= 0
Exp/Cntr=.3,.1

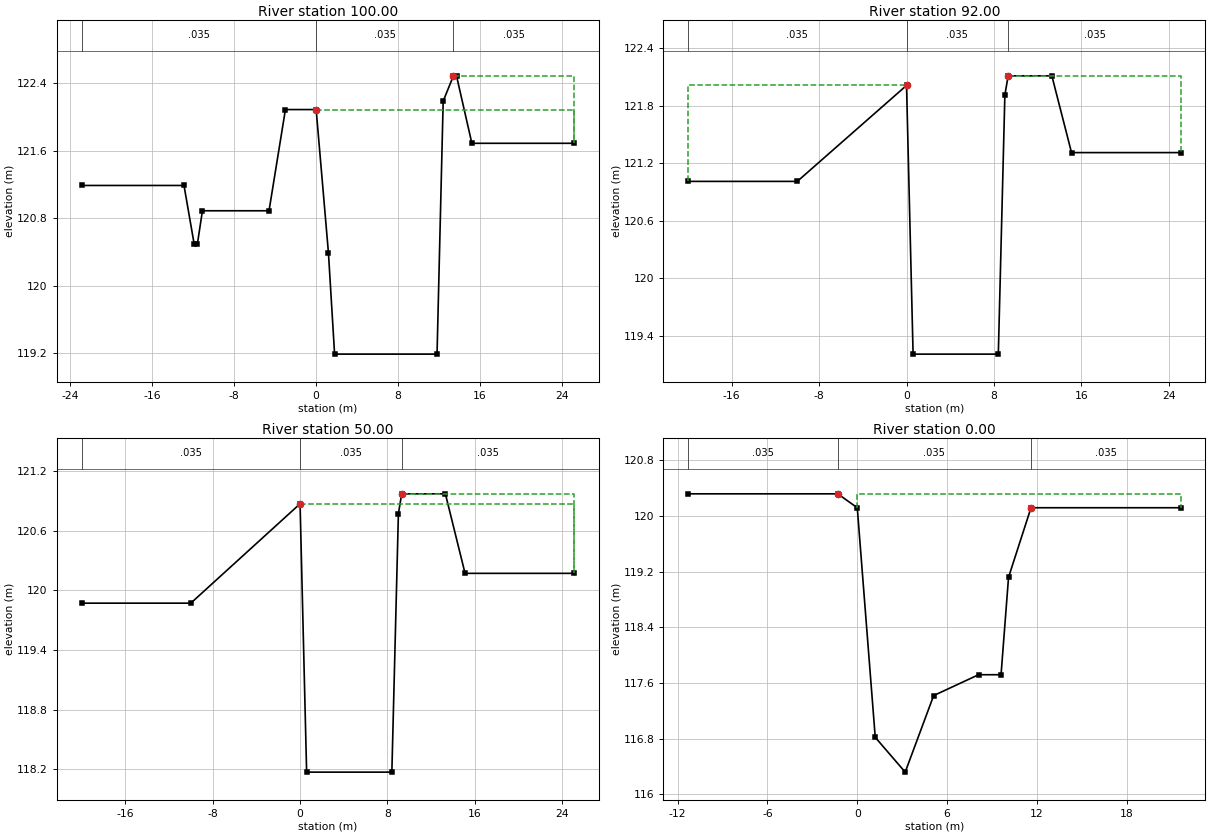
Type RM Length L Ch R = 1 ,100.00  ,8,8,8
BEGIN DESCRIPTION:
2
END DESCRIPTION:
#Sta/Elev= 16
   -22.9  121.19   -12.9  121.19   -11.9  120.49   -11.6  120.49   -11.1  120.89
    -4.6  120.89      -3  122.09       0  122.09     1.2  120.39     1.8  119.19
    11.8  119.19    12.4  122.19    13.4  122.49    13.7  122.49    15.2  121.69
    25.2  121.69
#Mann= 3 , 0 , 0
   -22.9    .035       0       0    .035       0    13.4    .035       0
#XS Ineff= 2 , 0
       0       0  122.09    13.4       0  122.49
Permanent Ineff=
       F       F
Bank Sta=0,13.4
XS Rating Curve= 0
Exp/Cntr=.3,.1

Type RM Length L Ch R = 1 ,92.00   ,42,42,42
BEGIN DESCRIPTION:
1.042
END DESCRIPTION:
#Sta/Elev= 10
     -20  121.01     -10  121.01       0  122.01      .6  119.21     8.4  119.21
       9  121.91     9.3  122.11    13.3  122.11    15.1  121.31    25.1  121.31
#Mann= 3 , 0 , 0
     -20    .035       0       0    .035       0     9.3    .035       0
#XS Ineff= 2 , 0
               0  122.01     9.3          122.11
Permanent Ineff=
       F       F
Bank Sta=0,9.3
XS Rating Curve= 0
Exp/Cntr=.3,.1

Type RM Length L Ch R = 1 ,50.00   ,50,50,50
BEGIN DESCRIPTION:
1
END DESCRIPTION:
#Sta/Elev= 10
     -20  119.87     -10  119.87       0  120.87      .6  118.17     8.4  118.17
       9  120.77     9.3  120.97    13.3  120.97    15.1  120.17    25.1  120.17
#Mann= 3 , 0 , 0
     -20    .035       0       0    .035       0     9.3    .035       0
#XS Ineff= 2 , 0
       0       0  120.87     9.3       0  120.97
Permanent Ineff=
       F       F
Bank Sta=0,9.3
XS Rating Curve= 0
Exp/Cntr=.3,.1

Type RM Length L Ch R = 1 ,0.00    ,0,0,0
BEGIN DESCRIPTION:
0
END DESCRIPTION:
#Sta/Elev= 11
   -11.3  120.32    -1.3  120.32       0  120.12     1.2  116.82     3.2  116.32
     5.1  117.42     8.1  117.72     9.6  117.72    10.1  119.12    11.6  120.12
    21.6  120.12
#Mann= 3 , 0 , 0
   -11.3    .035       0    -1.3    .035       0    11.6    .035       0
#XS Ineff= 2 , 0
       0    -1.3  120.32    11.6       0  120.12
Permanent Ineff=
       F       F
Bank Sta=-1.3,11.6
XS Rating Curve= 0
Exp/Cntr=.3,.1

Chan Stop Cuts=-1