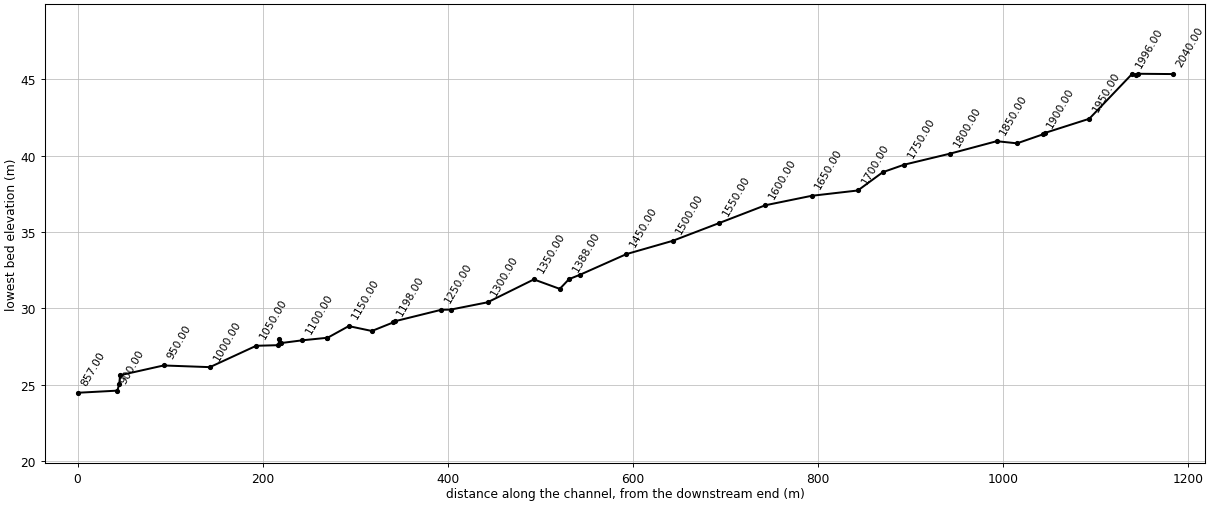
--- DKC.prj (project) ---

Proj Title=DKC
Current Plan=p01
Default Exp/Contr=.3,.1
SI Units
Geom File=g01
Flow File=f01
Plan File=p01
Y Axis Title=Elevation
X Axis Title(PF)=Main Channel Distance
X Axis Title(XS)=Station
BEGIN DESCRIPTION:
           BACK WATER COMPUTATION
      APPLICATION OF HEC-2 BY Samju Construction Engineering
      DAEGOK-STREEM : 30 YR
END DESCRIPTION:
DSS Export Rating Curves= 0
DSS Export Rating Curve Sorted= 0
DSS Export Volume Flow Curves= 0
DXF OffsetX= 0
DXF OffsetY= 0
DXF ScaleX= 1
DXF ScaleY= 10

--- DKC.p01 (plan) ---

Plan Title=Imported Plan 01
Version=Version 3.0.1  Mar 2001
Short Identifier=Imported Pla
Geom File=g01
Flow File=f01
Subcritical Flow
K Sum by GR= 0
Std Step Tol= 0.003
Critical Tol= 0.003
Num of Std Step Trials= 20
Max Error Tol= 0.1
Flow Tol Ratio= 0.001
Split Flow NTrial= 30
Split Flow Tol= 0.02
Split Flow Ratio= 0.02
Log Output Level= 0
Friction Slope Method= 1
Unsteady Friction Slope Method= 2
Parabolic Critical Depth
Global Vel Dist= 0 , 0 , 0
Global Log Level= 0
CheckData=True
Encroach Param=-1 ,0,0, 0
Computation Interval=1HOUR
Output Interval=1HOUR
Run HTab= 0
Run UNet= 0
Run PostProcess= 0
UNET Theta= 1
UNET ZTol= 0.02
UNET ZSATol= 0.1
UNET MxIter= 20
UNET MaxInSteps= 20
UNET DtIC= 0
UNET DtMin= 0
UNET MaxCRTS= 20
UNET WFStab= 2
UNET SFStab= 1
UNET WFX= 1
UNET SFX= 1
UNET Convert EG Bridges=-1
UNET Use Existing IB Tables=-1
Instantaneous Interval=1HOUR
Write IC File= 0
Write Velocity= 0
Write Detailed= 0

--- DKC.f01 (steady flow) ---

Flow Title=Imported Flow 01
Version=Version 3.0.1  Mar 2001
Number of Profiles= 5
Profile Names=10YR,20YR,30YR,50YR,80YR
River Rch & RM=RIVER-1,Reach-1         ,40.04
    29.8   32.84   34.61   36.85   38.91
River Rch & RM=DAEKOK,DAEKOK          ,2040.00
    29.8   32.84   34.61   36.85   38.91
Boundary for River Rch & Prof#=DAEKOK,DAEKOK          , 1
Up Type= 0
Dn Type= 3
Dn Slope=.02
Boundary for River Rch & Prof#=DAEKOK,DAEKOK          , 2
Up Type= 0
Dn Type= 3
Dn Slope=.02
Boundary for River Rch & Prof#=DAEKOK,DAEKOK          , 3
Up Type= 0
Dn Type= 3
Dn Slope=.02
Boundary for River Rch & Prof#=DAEKOK,DAEKOK          , 4
Up Type= 0
Dn Type= 3
Dn Slope=.02
Boundary for River Rch & Prof#=DAEKOK,DAEKOK          , 5
Up Type= 0
Dn Type= 3
Dn Slope=.02
DSS Import GetInterval= 0
DSS Import GetPeak= 0
DSS Import FillOption= 0

--- DKC.g01 (geometry) ---

Geom Title=Imported Geom 01
Version=Version 3.0.1  Mar 2001

River Reach=DAEKOK          ,DAEKOK
Reach XY= 2
              .5             .95              .5             .05

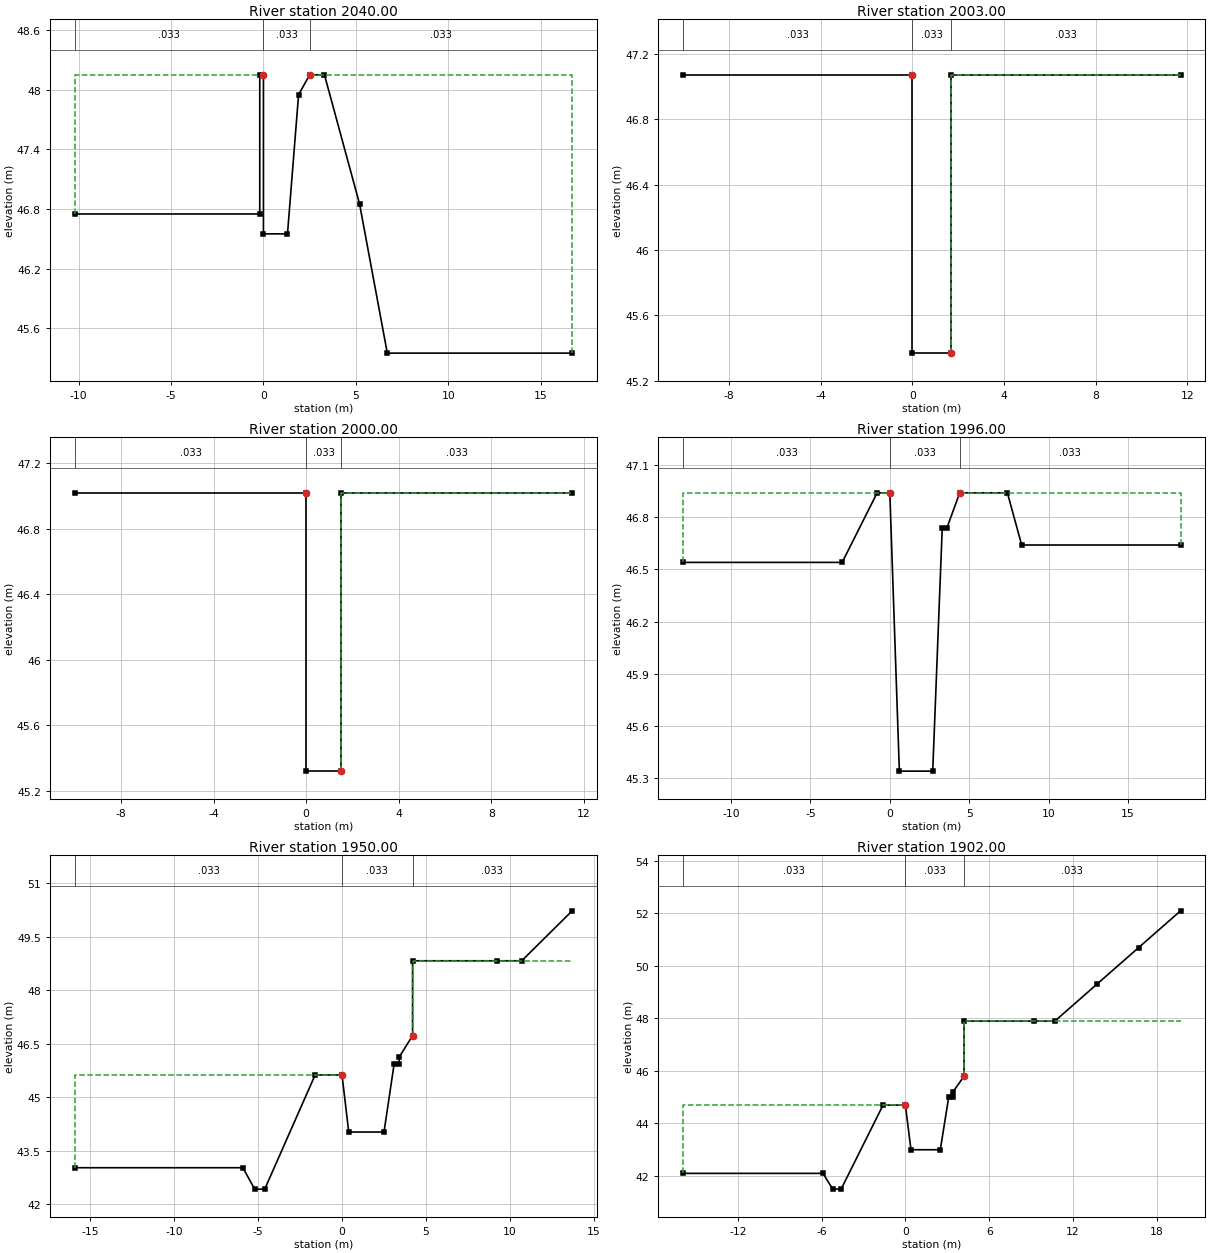
Type RM Length L Ch R = 1 ,2040.00 ,37,37,37
BEGIN DESCRIPTION:
40.04
END DESCRIPTION:
#Sta/Elev= 12
   -10.2   46.75     -.2   46.75     -.2   48.15       0   48.15       0   46.55
     1.3   46.55     1.9   47.95     2.5   48.15     3.3   48.15     5.2   46.85
     6.7   45.35    16.7   45.35
#Mann= 3 , 0 , 0
   -10.2    .033       0       0    .033       0     2.5    .033       0
#XS Ineff= 2 , 0
               0   48.15     2.5           48.15
Permanent Ineff=
       F       F
Bank Sta=0,2.5
XS Rating Curve= 0
Exp/Cntr=.3,.1

Type RM Length L Ch R = 1 ,2003.00 ,3,3,3
BEGIN DESCRIPTION:
40.003
END DESCRIPTION:
#Sta/Elev= 6
     -10   47.07       0   47.07       0   45.37     1.7   45.37     1.7   47.07
    11.7   47.07
#Mann= 3 , 0 , 0
     -10    .033       0       0    .033       0     1.7    .033       0
#XS Ineff= 2 , 0
               0   47.07     1.7           47.07
Permanent Ineff=
       F       F
Bank Sta=0,1.7
XS Rating Curve= 0
Exp/Cntr=.3,.1

Type RM Length L Ch R = 1 ,2000.00 ,4,4,4
BEGIN DESCRIPTION:
40
END DESCRIPTION:
#Sta/Elev= 6
     -10   47.02       0   47.02       0   45.32     1.5   45.32     1.5   47.02
    11.5   47.02
#Mann= 3 , 0 , 0
     -10    .033       0       0    .033       0     1.5    .033       0
#XS Ineff= 2 , 0
               0   47.02     1.5           47.02
Permanent Ineff=
       F       F
Bank Sta=0,1.5
XS Rating Curve= 0
Exp/Cntr=.3,.1

Type RM Length L Ch R = 1 ,1996.00 ,46,46,46
BEGIN DESCRIPTION:
39.046
END DESCRIPTION:
#Sta/Elev= 12
     -13   46.54      -3   46.54     -.8   46.94       0   46.94      .6   45.34
     2.7   45.34     3.3   46.74     3.6   46.74     4.4   46.94     7.4   46.94
     8.3   46.64    18.3   46.64
#Mann= 3 , 0 , 0
     -13    .033       0       0    .033       0     4.4    .033       0
#XS Ineff= 2 , 0
               0   46.94     4.4           46.94
Permanent Ineff=
       F       F
Bank Sta=0,4.4
XS Rating Curve= 0
Exp/Cntr=.3,.1

Type RM Length L Ch R = 1 ,1950.00 ,48,48,48
BEGIN DESCRIPTION:
39
END DESCRIPTION:
#Sta/Elev= 16
   -15.9   43.02    -5.9   43.02    -5.2   42.42    -4.6   42.42    -1.6   45.62
       0   45.62      .4   44.02     2.5   44.02     3.1   45.92     3.4   45.92
     3.4   46.12     4.2   46.72     4.2   48.82     9.2   48.82    10.7   48.82
    13.7   50.22
#Mann= 3 , 0 , 0
   -15.9    .033       0       0    .033       0     4.2    .033       0
#XS Ineff= 2 , 0
               0   45.62     4.2           48.82
Permanent Ineff=
       F       F
Bank Sta=0,4.2
XS Rating Curve= 0
Exp/Cntr=.3,.1

Type RM Length L Ch R = 1 ,1902.00 ,2,2,2
BEGIN DESCRIPTION:
38.002
END DESCRIPTION:
#Sta/Elev= 18
   -15.9   42.09    -5.9   42.09    -5.2   41.49    -4.6   41.49    -1.6   44.69
       0   44.69      .4   42.99     2.5   42.99     3.1   44.99     3.4   44.99
     3.4   45.19     4.2   45.79     4.2   47.89     9.2   47.89    10.7   47.89
    13.7   49.29    16.7   50.69    19.7   52.09
#Mann= 3 , 0 , 0
   -15.9    .033       0       0    .033       0     4.2    .033       0
#XS Ineff= 2 , 0
               0   44.69     4.2           47.89
Permanent Ineff=
       F       F
Bank Sta=0,4.2
XS Rating Curve= 0
Exp/Cntr=.3,.1

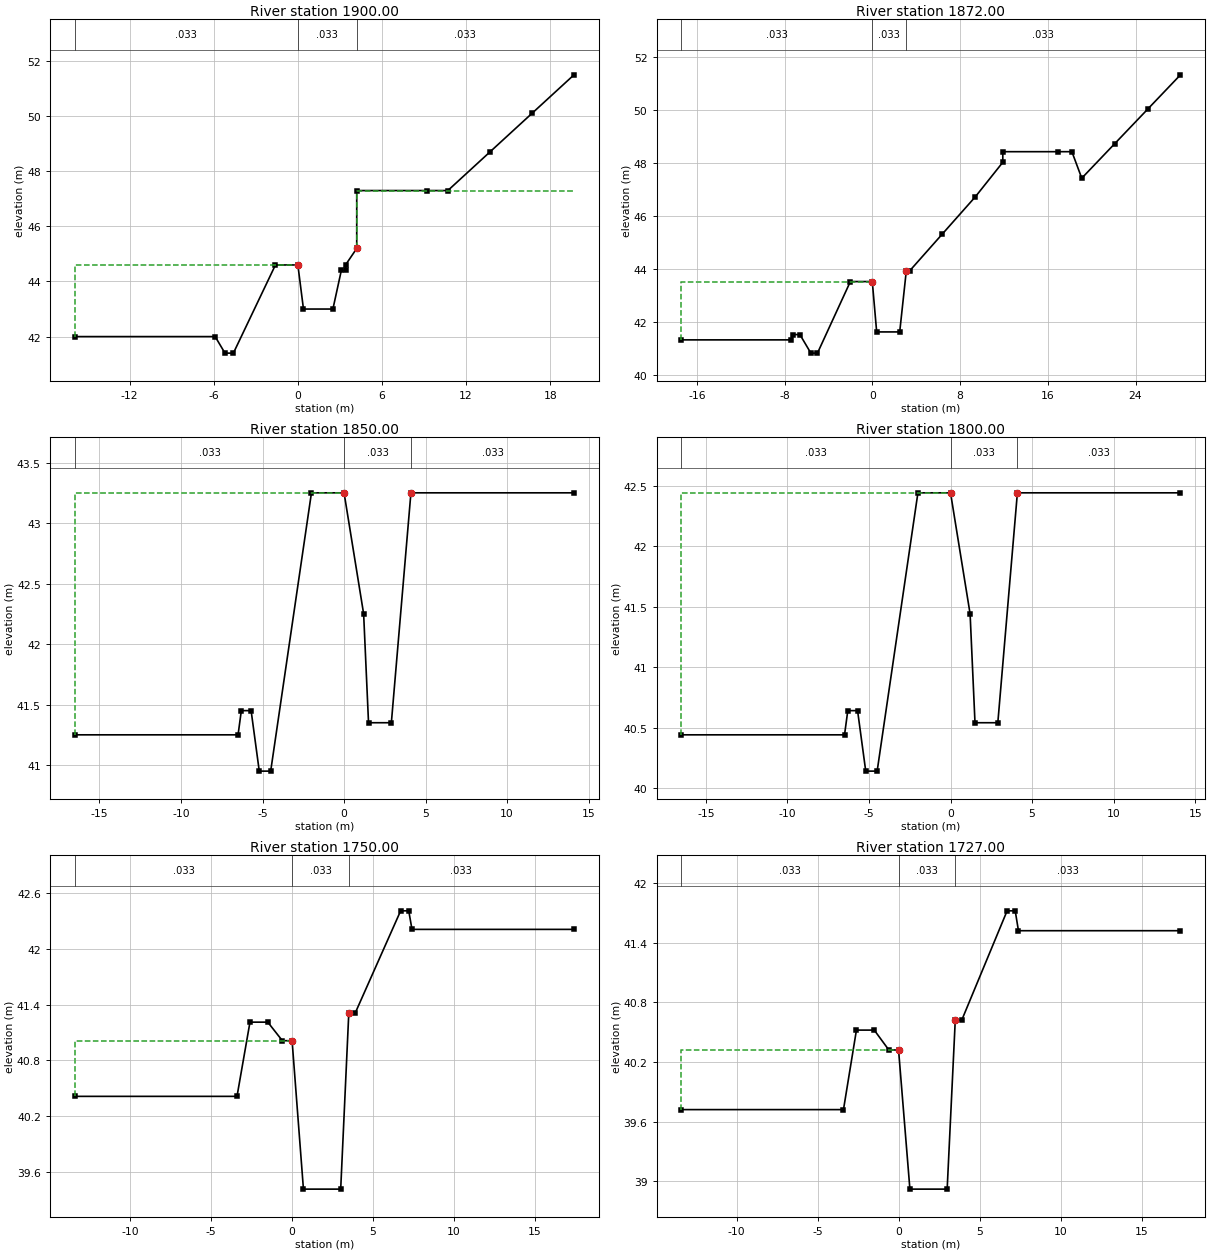
Type RM Length L Ch R = 1 ,1900.00 ,28,28,28
BEGIN DESCRIPTION:
38
END DESCRIPTION:
#Sta/Elev= 18
   -15.9      42    -5.9      42    -5.2    41.4    -4.6    41.4    -1.6    44.6
       0    44.6      .4      43     2.5      43     3.1    44.4     3.4    44.4
     3.4    44.6     4.2    45.2     4.2    47.3     9.2    47.3    10.7    47.3
    13.7    48.7    16.7    50.1    19.7    51.5
#Mann= 3 , 0 , 0
   -15.9    .033       0       0    .033       0     4.2    .033       0
#XS Ineff= 2 , 0
               0    44.6     4.2            47.3
Permanent Ineff=
       F       F
Bank Sta=0,4.2
XS Rating Curve= 0
Exp/Cntr=.3,.1

Type RM Length L Ch R = 1 ,1872.00 ,22,22,22
BEGIN DESCRIPTION:
37.022
END DESCRIPTION:
#Sta/Elev= 22
   -17.4   41.31    -7.4   41.31    -7.2   41.51    -6.6   41.51    -5.6   40.81
      -5   40.81      -2   43.51       0   43.51      .4   41.61     2.5   41.61
     3.1   43.91     3.4   43.91     6.4   45.31     9.4   46.71    11.9   48.01
    11.9   48.41    16.9   48.41    18.2   48.41    19.1   47.41    22.1   48.71
    25.1   50.01    28.1   51.31
#Mann= 3 , 0 , 0
   -17.4    .033       0       0    .033       0     3.1    .033       0
#XS Ineff= 2 , 0
               0   43.51     3.1           43.91
Permanent Ineff=
       F       F
Bank Sta=0,3.1
XS Rating Curve= 0
Exp/Cntr=.3,.1

Type RM Length L Ch R = 1 ,1850.00 ,50,50,50
BEGIN DESCRIPTION:
37
END DESCRIPTION:
#Sta/Elev= 13
   -16.5   41.25    -6.5   41.25    -6.3   41.45    -5.7   41.45    -5.2   40.95
    -4.5   40.95      -2   43.25       0   43.25     1.2   42.25     1.5   41.35
     2.9   41.35     4.1   43.25    14.1   43.25
#Mann= 3 , 0 , 0
   -16.5    .033       0       0    .033       0     4.1    .033       0
#XS Ineff= 2 , 0
               0   43.25     4.1           43.25
Permanent Ineff=
       F       F
Bank Sta=0,4.1
XS Rating Curve= 0
Exp/Cntr=.3,.1

Type RM Length L Ch R = 1 ,1800.00 ,50,50,50
BEGIN DESCRIPTION:
36
END DESCRIPTION:
#Sta/Elev= 13
   -16.5   40.44    -6.5   40.44    -6.3   40.64    -5.7   40.64    -5.2   40.14
    -4.5   40.14      -2   42.44       0   42.44     1.2   41.44     1.5   40.54
     2.9   40.54     4.1   42.44    14.1   42.44
#Mann= 3 , 0 , 0
   -16.5    .033       0       0    .033       0     4.1    .033       0
#XS Ineff= 2 , 0
               0   42.44     4.1           42.44
Permanent Ineff=
       F       F
Bank Sta=0,4.1
XS Rating Curve= 0
Exp/Cntr=.3,.1

Type RM Length L Ch R = 1 ,1750.00 ,23,23,23
BEGIN DESCRIPTION:
35
END DESCRIPTION:
#Sta/Elev= 14
   -13.4   40.41    -3.4   40.41    -2.6   41.21    -1.5   41.21     -.6   41.01
       0   41.01      .7   39.41       3   39.41     3.5   41.31     3.9   41.31
     6.7   42.41     7.2   42.41     7.4   42.21    17.4   42.21
#Mann= 3 , 0 , 0
   -13.4    .033       0       0    .033       0     3.5    .033       0
#XS Ineff= 2 , 0
               0   41.01     3.5           41.31
Permanent Ineff=
       F       F
Bank Sta=0,3.5
XS Rating Curve= 0
Exp/Cntr=.3,.1

Type RM Length L Ch R = 1 ,1727.00 ,27,27,27
BEGIN DESCRIPTION:
34.027
END DESCRIPTION:
#Sta/Elev= 14
   -13.4   39.72    -3.4   39.72    -2.6   40.52    -1.5   40.52     -.6   40.32
       0   40.32      .7   38.92       3   38.92     3.5   40.62     3.9   40.62
     6.7   41.72     7.2   41.72     7.4   41.52    17.4   41.52
#Mann= 3 , 0 , 0
   -13.4    .033       0       0    .033       0     3.5    .033       0
#XS Ineff= 2 , 0
               0   40.32     3.5           40.62
Permanent Ineff=
       F       F
Bank Sta=0,3.5
XS Rating Curve= 0
Exp/Cntr=.3,.1

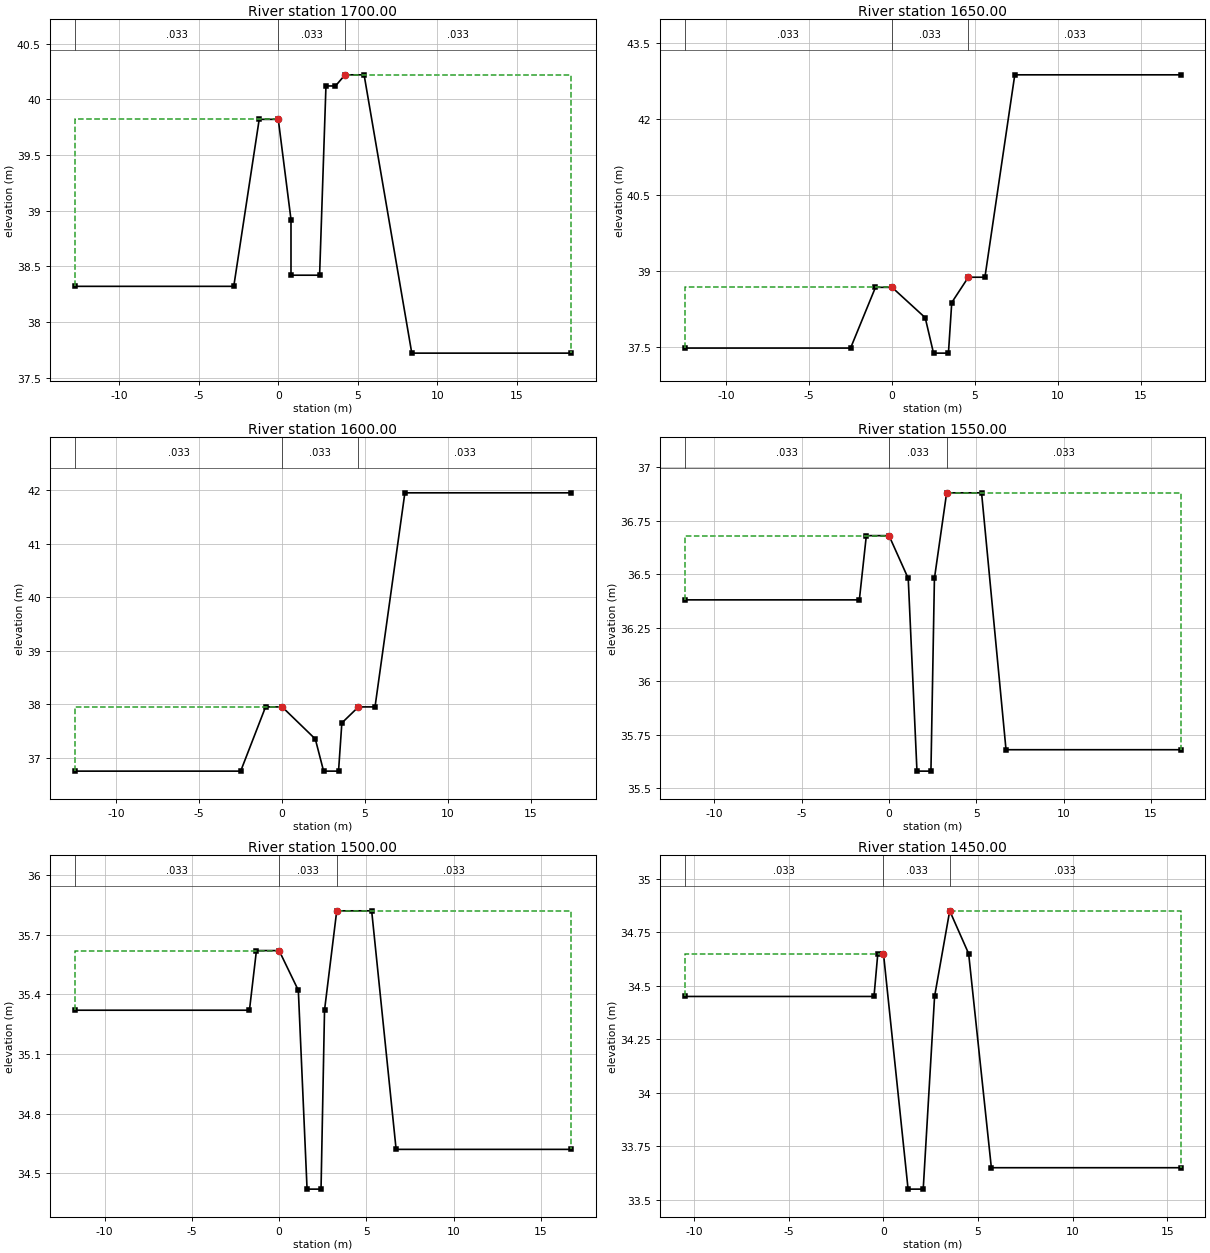
Type RM Length L Ch R = 1 ,1700.00 ,50,50,50
BEGIN DESCRIPTION:
34
END DESCRIPTION:
#Sta/Elev= 13
   -12.8   38.32    -2.8   38.32    -1.2   39.82       0   39.82      .8   38.92
      .8   38.42     2.6   38.42       3   40.12     3.6   40.12     4.2   40.22
     5.4   40.22     8.4   37.72    18.4   37.72
#Mann= 3 , 0 , 0
   -12.8    .033       0       0    .033       0     4.2    .033       0
#XS Ineff= 2 , 0
               0   39.82     4.2           40.22
Permanent Ineff=
       F       F
Bank Sta=0,4.2
XS Rating Curve= 0
Exp/Cntr=.3,.1

Type RM Length L Ch R = 1 ,1650.00 ,50,50,50
BEGIN DESCRIPTION:
33
END DESCRIPTION:
#Sta/Elev= 12
   -12.5   37.47    -2.5   37.47      -1   38.67       0   38.67       2   38.07
     2.5   37.37     3.4   37.37     3.6   38.37     4.6   38.87     5.6   38.87
     7.4   42.87    17.4   42.87
#Mann= 3 , 0 , 0
   -12.5    .033       0       0    .033       0     4.6    .033       0
#XS Ineff= 2 , 0
               0   38.67     4.6           38.87
Permanent Ineff=
       F       F
Bank Sta=0,4.6
XS Rating Curve= 0
Exp/Cntr=.3,.1

Type RM Length L Ch R = 1 ,1600.00 ,50,50,50
BEGIN DESCRIPTION:
32
END DESCRIPTION:
#Sta/Elev= 12
   -12.5   36.75    -2.5   36.75      -1   37.95       0   37.95       2   37.35
     2.5   36.75     3.4   36.75     3.6   37.65     4.6   37.95     5.6   37.95
     7.4   41.95    17.4   41.95
#Mann= 3 , 0 , 0
   -12.5    .033       0       0    .033       0     4.6    .033       0
#XS Ineff= 2 , 0
               0   37.95     4.6           37.95
Permanent Ineff=
       F       F
Bank Sta=0,4.6
XS Rating Curve= 0
Exp/Cntr=.3,.1

Type RM Length L Ch R = 1 ,1550.00 ,50,50,50
BEGIN DESCRIPTION:
31
END DESCRIPTION:
#Sta/Elev= 12
   -11.7   36.38    -1.7   36.38    -1.3   36.68       0   36.68     1.1   36.48
     1.6   35.58     2.4   35.58     2.6   36.48     3.3   36.88     5.3   36.88
     6.7   35.68    16.7   35.68
#Mann= 3 , 0 , 0
   -11.7    .033       0       0    .033       0     3.3    .033       0
#XS Ineff= 2 , 0
               0   36.68     3.3           36.88
Permanent Ineff=
       F       F
Bank Sta=0,3.3
XS Rating Curve= 0
Exp/Cntr=.3,.1

Type RM Length L Ch R = 1 ,1500.00 ,50,50,50
BEGIN DESCRIPTION:
30
END DESCRIPTION:
#Sta/Elev= 12
   -11.7   35.32    -1.7   35.32    -1.3   35.62       0   35.62     1.1   35.42
     1.6   34.42     2.4   34.42     2.6   35.32     3.3   35.82     5.3   35.82
     6.7   34.62    16.7   34.62
#Mann= 3 , 0 , 0
   -11.7    .033       0       0    .033       0     3.3    .033       0
#XS Ineff= 2 , 0
               0   35.62     3.3           35.82
Permanent Ineff=
       F       F
Bank Sta=0,3.3
XS Rating Curve= 0
Exp/Cntr=.3,.1

Type RM Length L Ch R = 1 ,1450.00 ,50,50,50
BEGIN DESCRIPTION:
29
END DESCRIPTION:
#Sta/Elev= 11
   -10.5   34.45     -.5   34.45     -.3   34.65       0   34.65     1.3   33.55
     2.1   33.55     2.7   34.45     3.5   34.85     4.5   34.65     5.7   33.65
    15.7   33.65
#Mann= 3 , 0 , 0
   -10.5    .033       0       0    .033       0     3.5    .033       0
#XS Ineff= 2 , 0
               0   34.65     3.5           34.85
Permanent Ineff=
       F       F
Bank Sta=0,3.5
XS Rating Curve= 0
Exp/Cntr=.3,.1

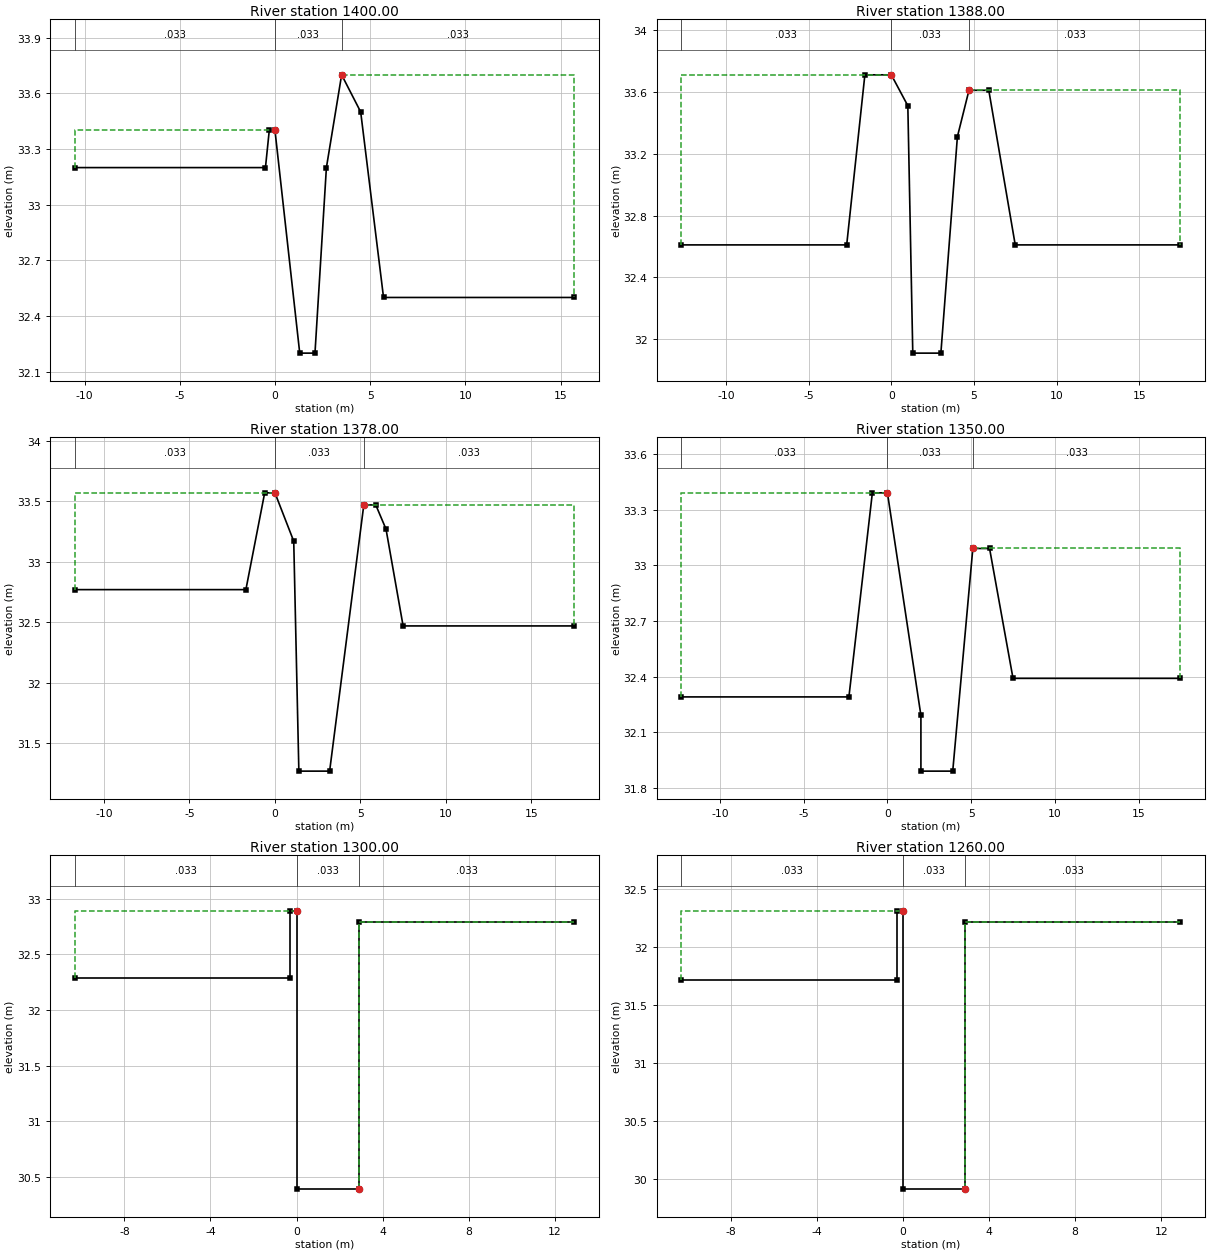
Type RM Length L Ch R = 1 ,1400.00 ,12,12,12
BEGIN DESCRIPTION:
28
END DESCRIPTION:
#Sta/Elev= 11
   -10.5    33.2     -.5    33.2     -.3    33.4       0    33.4     1.3    32.2
     2.1    32.2     2.7    33.2     3.5    33.7     4.5    33.5     5.7    32.5
    15.7    32.5
#Mann= 3 , 0 , 0
   -10.5    .033       0       0    .033       0     3.5    .033       0
#XS Ineff= 2 , 0
               0    33.4     3.5            33.7
Permanent Ineff=
       F       F
Bank Sta=0,3.5
XS Rating Curve= 0
Exp/Cntr=.3,.1

Type RM Length L Ch R = 1 ,1388.00 ,10,10,10
BEGIN DESCRIPTION:
27.038
END DESCRIPTION:
#Sta/Elev= 12
   -12.7   32.61    -2.7   32.61    -1.6   33.71       0   33.71       1   33.51
     1.3   31.91       3   31.91       4   33.31     4.7   33.61     5.9   33.61
     7.5   32.61    17.5   32.61
#Mann= 3 , 0 , 0
   -12.7    .033       0       0    .033       0     4.7    .033       0
#XS Ineff= 2 , 0
               0   33.71     4.7           33.61
Permanent Ineff=
       F       F
Bank Sta=0,4.7
XS Rating Curve= 0
Exp/Cntr=.3,.1

Type RM Length L Ch R = 1 ,1378.00 ,28,28,28
BEGIN DESCRIPTION:
27.028
END DESCRIPTION:
#Sta/Elev= 12
   -11.7   32.77    -1.7   32.77     -.6   33.57       0   33.57     1.1   33.17
     1.4   31.27     3.2   31.27     5.2   33.47     5.9   33.47     6.5   33.27
     7.5   32.47    17.5   32.47
#Mann= 3 , 0 , 0
   -11.7    .033       0       0    .033       0     5.2    .033       0
#XS Ineff= 2 , 0
               0   33.57     5.2           33.47
Permanent Ineff=
       F       F
Bank Sta=0,5.2
XS Rating Curve= 0
Exp/Cntr=.3,.1

Type RM Length L Ch R = 1 ,1350.00 ,50,50,50
BEGIN DESCRIPTION:
27
END DESCRIPTION:
#Sta/Elev= 11
   -12.3   32.29    -2.3   32.29     -.9   33.39       0   33.39       2   32.19
       2   31.89     3.9   31.89     5.1   33.09     6.1   33.09     7.5   32.39
    17.5   32.39
#Mann= 3 , 0 , 0
   -12.3    .033       0       0    .033       0     5.1    .033       0
#XS Ineff= 2 , 0
               0   33.39     5.1           33.09
Permanent Ineff=
       F       F
Bank Sta=0,5.1
XS Rating Curve= 0
Exp/Cntr=.3,.1

Type RM Length L Ch R = 1 ,1300.00 ,40,40,40
BEGIN DESCRIPTION:
26
END DESCRIPTION:
#Sta/Elev= 8
   -10.3   32.29     -.3   32.29     -.3   32.89       0   32.89       0   30.39
     2.9   30.39     2.9   32.79    12.9   32.79
#Mann= 3 , 0 , 0
   -10.3    .033       0       0    .033       0     2.9    .033       0
#XS Ineff= 2 , 0
               0   32.89     2.9           32.79
Permanent Ineff=
       F       F
Bank Sta=0,2.9
XS Rating Curve= 0
Exp/Cntr=.3,.1

Type RM Length L Ch R = 1 ,1260.00 ,10,10,10
BEGIN DESCRIPTION:
25.01
END DESCRIPTION:
#Sta/Elev= 8
   -10.3   31.71     -.3   31.71     -.3   32.31       0   32.31       0   29.91
     2.9   29.91     2.9   32.21    12.9   32.21
#Mann= 3 , 0 , 0
   -10.3    .033       0       0    .033       0     2.9    .033       0
#XS Ineff= 2 , 0
               0   32.31     2.9           32.21
Permanent Ineff=
       F       F
Bank Sta=0,2.9
XS Rating Curve= 0
Exp/Cntr=.3,.1

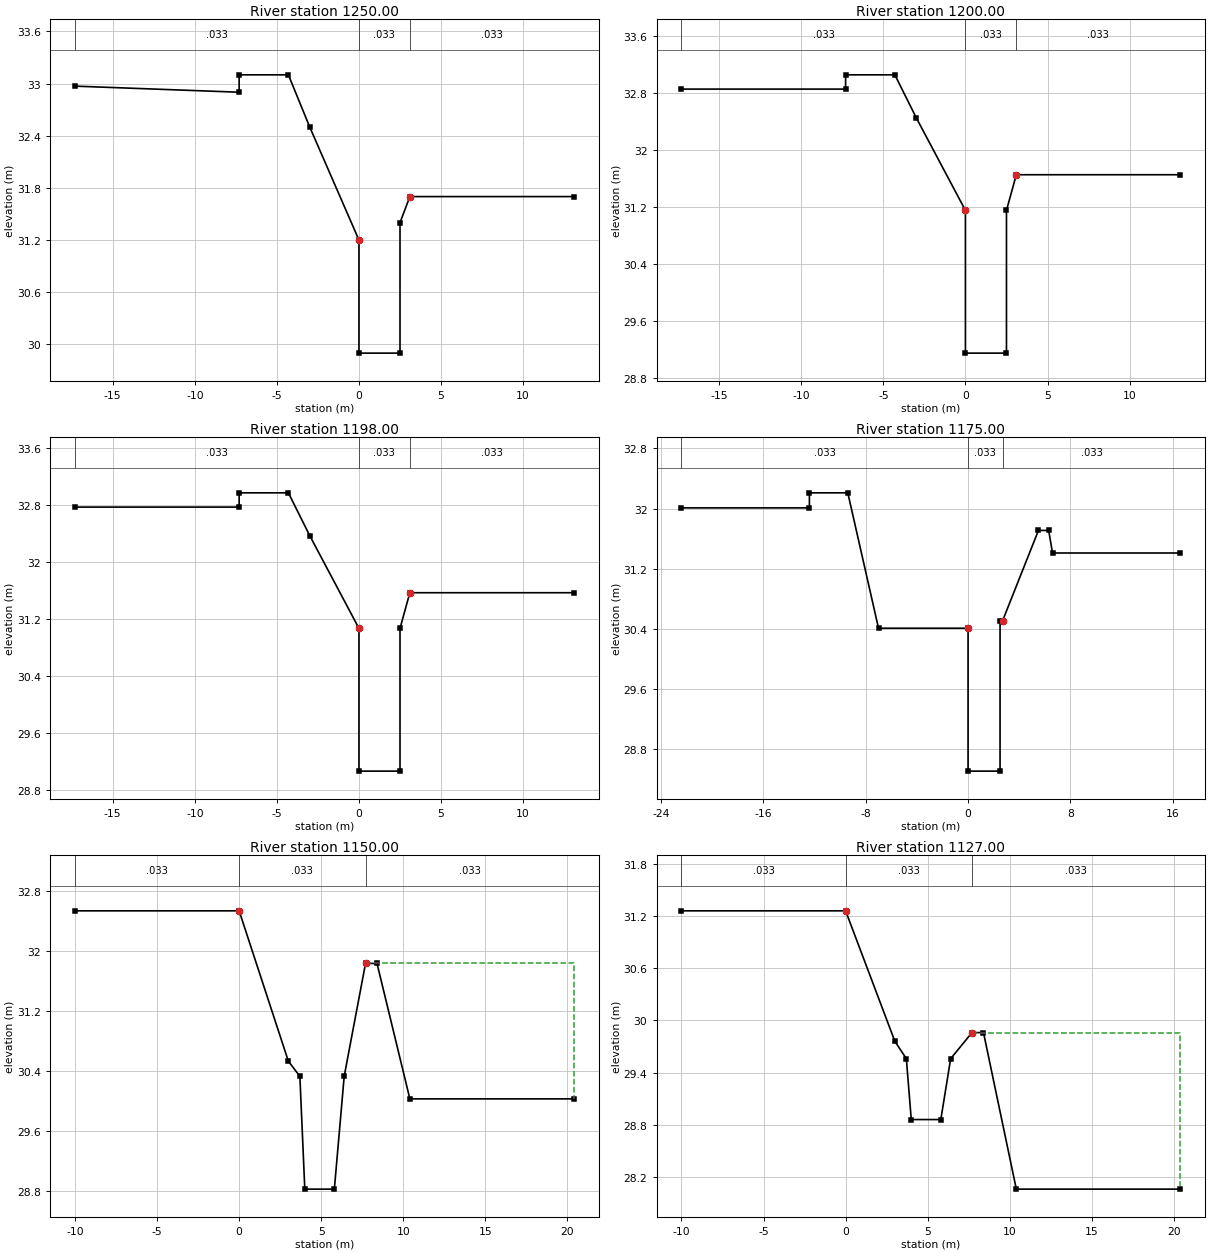
Type RM Length L Ch R = 1 ,1250.00 ,50,50,50
BEGIN DESCRIPTION:
25
END DESCRIPTION:
#Sta/Elev= 11
   -17.3   32.97    -7.3    32.9    -7.3    33.1    -4.3    33.1      -3    32.5
       0    31.2       0    29.9     2.5    29.9     2.5    31.4     3.1    31.7
    13.1    31.7
#Mann= 3 , 0 , 0
   -17.3    .033       0       0    .033       0     3.1    .033       0
#XS Ineff= 2 , 0
               0    31.2     3.1            31.7
Permanent Ineff=
       F       F
Bank Sta=0,3.1
XS Rating Curve= 0
Exp/Cntr=.3,.1

Type RM Length L Ch R = 1 ,1200.00 ,2,2,2
BEGIN DESCRIPTION:
24
END DESCRIPTION:
#Sta/Elev= 11
   -17.3   32.85    -7.3   32.85    -7.3   33.05    -4.3   33.05      -3   32.45
       0   31.15       0   29.15     2.5   29.15     2.5   31.15     3.1   31.65
    13.1   31.65
#Mann= 3 , 0 , 0
   -17.3    .033       0       0    .033       0     3.1    .033       0
#XS Ineff= 2 , 0
               0   31.15     3.1           31.65
Permanent Ineff=
       F       F
Bank Sta=0,3.1
XS Rating Curve= 0
Exp/Cntr=.3,.1

Type RM Length L Ch R = 1 ,1198.00 ,23,23,23
BEGIN DESCRIPTION:
23.048
END DESCRIPTION:
#Sta/Elev= 11
   -17.3   32.77    -7.3   32.77    -7.3   32.97    -4.3   32.97      -3   32.37
       0   31.07       0   29.07     2.5   29.07     2.5   31.07     3.1   31.57
    13.1   31.57
#Mann= 3 , 0 , 0
   -17.3    .033       0       0    .033       0     3.1    .033       0
#XS Ineff= 2 , 0
               0   31.07     3.1           31.57
Permanent Ineff=
       F       F
Bank Sta=0,3.1
XS Rating Curve= 0
Exp/Cntr=.3,.1

Type RM Length L Ch R = 1 ,1175.00 ,25,25,25
BEGIN DESCRIPTION:
23.025
END DESCRIPTION:
#Sta/Elev= 14
   -22.4   32.01   -12.4   32.01   -12.4   32.21    -9.4   32.21      -7   30.41
       0   30.41       0   28.51     2.5   28.51     2.5   30.51     2.7   30.51
     5.5   31.71     6.3   31.71     6.6   31.41    16.6   31.41
#Mann= 3 , 0 , 0
   -22.4    .033       0       0    .033       0     2.7    .033       0
#XS Ineff= 2 , 0
               0   30.41     2.7           30.51
Permanent Ineff=
       F       F
Bank Sta=0,2.7
XS Rating Curve= 0
Exp/Cntr=.3,.1

Type RM Length L Ch R = 1 ,1150.00 ,23,23,23
BEGIN DESCRIPTION:
23
END DESCRIPTION:
#Sta/Elev= 11
     -10   32.53       0   32.53       3   30.53     3.7   30.33       4   28.83
     5.8   28.83     6.4   30.33     7.7   31.83     8.4   31.83    10.4   30.03
    20.4   30.03
#Mann= 3 , 0 , 0
     -10    .033       0       0    .033       0     7.7    .033       0
#XS Ineff= 2 , 0
               0   32.53     7.7           31.83
Permanent Ineff=
       F       F
Bank Sta=0,7.7
XS Rating Curve= 0
Exp/Cntr=.3,.1

Type RM Length L Ch R = 1 ,1127.00 ,1,1,1
BEGIN DESCRIPTION:
22.027
END DESCRIPTION:
#Sta/Elev= 11
     -10   31.26       0   31.26       3   29.76     3.7   29.56       4   28.86
     5.8   28.86     6.4   29.56     7.7   29.86     8.4   29.86    10.4   28.06
    20.4   28.06
#Mann= 3 , 0 , 0
     -10    .033       0       0    .033       0     7.7    .033       0
#XS Ineff= 2 , 0
               0   31.26     7.7           29.86
Permanent Ineff=
       F       F
Bank Sta=0,7.7
XS Rating Curve= 0
Exp/Cntr=.3,.1

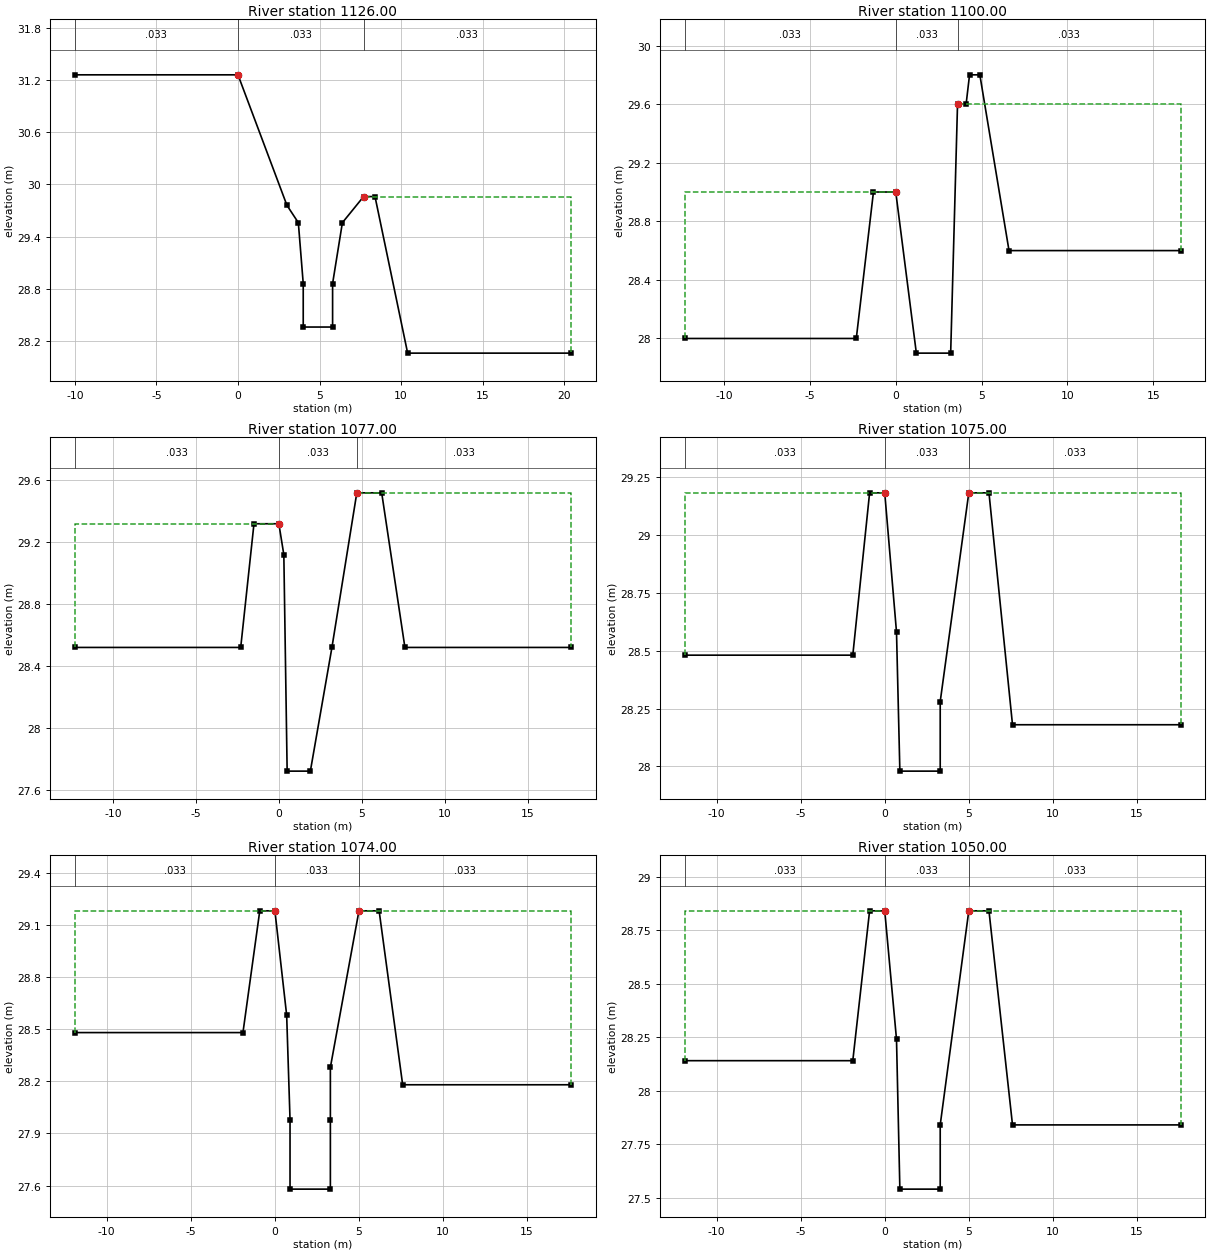
Type RM Length L Ch R = 1 ,1126.00 ,26,26,26
BEGIN DESCRIPTION:
22.026
END DESCRIPTION:
#Sta/Elev= 13
     -10   31.26       0   31.26       3   29.76     3.7   29.56       4   28.86
       4   28.36     5.8   28.36     5.8   28.86     6.4   29.56     7.7   29.86
     8.4   29.86    10.4   28.06    20.4   28.06
#Mann= 3 , 0 , 0
     -10    .033       0       0    .033       0     7.7    .033       0
#XS Ineff= 2 , 0
               0   31.26     7.7           29.86
Permanent Ineff=
       F       F
Bank Sta=0,7.7
XS Rating Curve= 0
Exp/Cntr=.3,.1

Type RM Length L Ch R = 1 ,1100.00 ,23,23,23
BEGIN DESCRIPTION:
22
END DESCRIPTION:
#Sta/Elev= 12
   -12.3      28    -2.3      28    -1.3      29       0      29     1.2    27.9
     3.2    27.9     3.6    29.6     4.1    29.6     4.3    29.8     4.9    29.8
     6.6    28.6    16.6    28.6
#Mann= 3 , 0 , 0
   -12.3    .033       0       0    .033       0     3.6    .033       0
#XS Ineff= 2 , 0
               0      29     3.6            29.6
Permanent Ineff=
       F       F
Bank Sta=0,3.6
XS Rating Curve= 0
Exp/Cntr=.3,.1

Type RM Length L Ch R = 1 ,1077.00 ,2,2,2
BEGIN DESCRIPTION:
21.027
END DESCRIPTION:
#Sta/Elev= 12
   -12.3   28.52    -2.3   28.52    -1.5   29.32       0   29.32      .3   29.12
      .5   27.72     1.9   27.72     3.2   28.52     4.7   29.52     6.2   29.52
     7.6   28.52    17.6   28.52
#Mann= 3 , 0 , 0
   -12.3    .033       0       0    .033       0     4.7    .033       0
#XS Ineff= 2 , 0
               0   29.32     4.7           29.52
Permanent Ineff=
       F       F
Bank Sta=0,4.7
XS Rating Curve= 0
Exp/Cntr=.3,.1

Type RM Length L Ch R = 1 ,1075.00 ,1,1,1
BEGIN DESCRIPTION:
21.025
END DESCRIPTION:
#Sta/Elev= 12
   -11.9   28.48    -1.9   28.48     -.9   29.18       0   29.18      .7   28.58
      .9   27.98     3.3   27.98     3.3   28.28       5   29.18     6.2   29.18
     7.6   28.18    17.6   28.18
#Mann= 3 , 0 , 0
   -11.9    .033       0       0    .033       0       5    .033       0
#XS Ineff= 2 , 0
               0   29.18       5           29.18
Permanent Ineff=
       F       F
Bank Sta=0,5
XS Rating Curve= 0
Exp/Cntr=.3,.1

Type RM Length L Ch R = 1 ,1074.00 ,24,24,24
BEGIN DESCRIPTION:
21.024
END DESCRIPTION:
#Sta/Elev= 14
   -11.9   28.48    -1.9   28.48     -.9   29.18       0   29.18      .7   28.58
      .9   27.98      .9   27.58     3.3   27.58     3.3   27.98     3.3   28.28
       5   29.18     6.2   29.18     7.6   28.18    17.6   28.18
#Mann= 3 , 0 , 0
   -11.9    .033       0       0    .033       0       5    .033       0
#XS Ineff= 2 , 0
               0   29.18       5           29.18
Permanent Ineff=
       F       F
Bank Sta=0,5
XS Rating Curve= 0
Exp/Cntr=.3,.1

Type RM Length L Ch R = 1 ,1050.00 ,50,50,50
BEGIN DESCRIPTION:
21
END DESCRIPTION:
#Sta/Elev= 12
   -11.9   28.14    -1.9   28.14     -.9   28.84       0   28.84      .7   28.24
      .9   27.54     3.3   27.54     3.3   27.84       5   28.84     6.2   28.84
     7.6   27.84    17.6   27.84
#Mann= 3 , 0 , 0
   -11.9    .033       0       0    .033       0       5    .033       0
#XS Ineff= 2 , 0
               0   28.84       5           28.84
Permanent Ineff=
       F       F
Bank Sta=0,5
XS Rating Curve= 0
Exp/Cntr=.3,.1

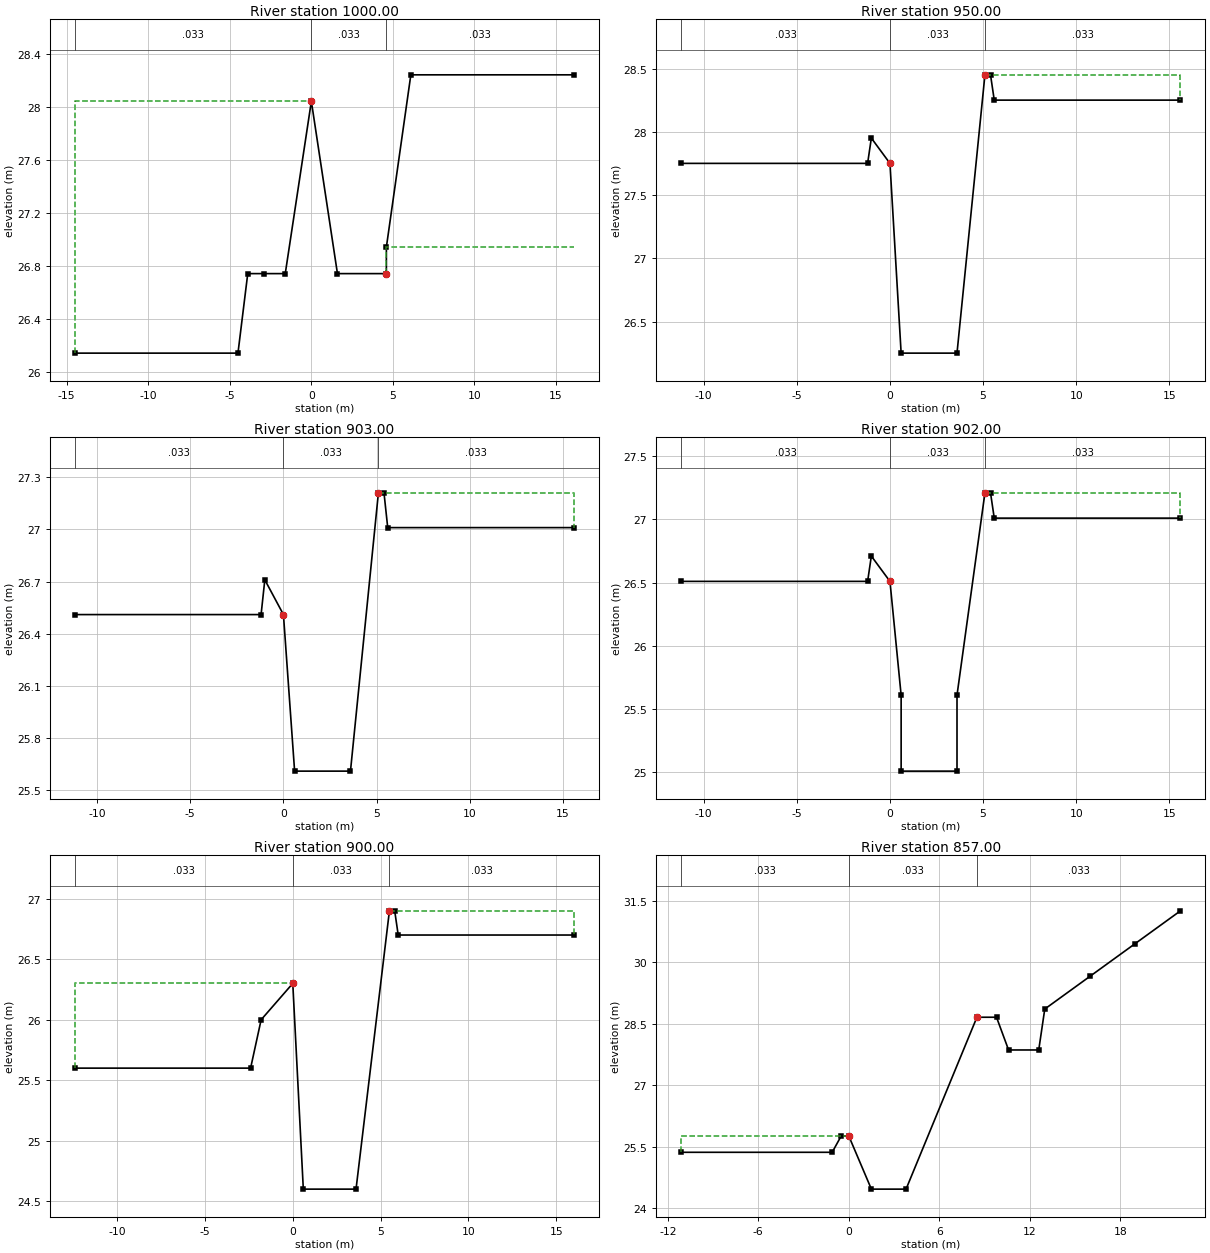
Type RM Length L Ch R = 1 ,1000.00 ,50,50,50
BEGIN DESCRIPTION:
20
END DESCRIPTION:
#Sta/Elev= 11
   -14.5   26.14    -4.5   26.14    -3.9   26.74    -2.9   26.74    -1.6   26.74
       0   28.04     1.6   26.74     4.6   26.74     4.6   26.94     6.1   28.24
    16.1   28.24
#Mann= 3 , 0 , 0
   -14.5    .033       0       0    .033       0     4.6    .033       0
#XS Ineff= 2 , 0
               0   28.04     4.6           26.94
Permanent Ineff=
       F       F
Bank Sta=0,4.6
XS Rating Curve= 0
Exp/Cntr=.3,.1

Type RM Length L Ch R = 1 ,950.00  ,47,47,47
BEGIN DESCRIPTION:
19
END DESCRIPTION:
#Sta/Elev= 10
   -11.2   27.75    -1.2   27.75      -1   27.95       0   27.75      .6   26.25
     3.6   26.25     5.1   28.45     5.4   28.45     5.6   28.25    15.6   28.25
#Mann= 3 , 0 , 0
   -11.2    .033       0       0    .033       0     5.1    .033       0
#XS Ineff= 2 , 0
               0   27.75     5.1           28.45
Permanent Ineff=
       F       F
Bank Sta=0,5.1
XS Rating Curve= 0
Exp/Cntr=.3,.1

Type RM Length L Ch R = 1 ,903.00  ,1,1,1
BEGIN DESCRIPTION:
18.003
END DESCRIPTION:
#Sta/Elev= 10
   -11.2   26.51    -1.2   26.51      -1   26.71       0   26.51      .6   25.61
     3.6   25.61     5.1   27.21     5.4   27.21     5.6   27.01    15.6   27.01
#Mann= 3 , 0 , 0
   -11.2    .033       0       0    .033       0     5.1    .033       0
#XS Ineff= 2 , 0
               0   26.51     5.1           27.21
Permanent Ineff=
       F       F
Bank Sta=0,5.1
XS Rating Curve= 0
Exp/Cntr=.3,.1

Type RM Length L Ch R = 1 ,902.00  ,2,2,2
BEGIN DESCRIPTION:
18.002
END DESCRIPTION:
#Sta/Elev= 12
   -11.2   26.51    -1.2   26.51      -1   26.71       0   26.51      .6   25.61
      .6   25.01     3.6   25.01     3.6   25.61     5.1   27.21     5.4   27.21
     5.6   27.01    15.6   27.01
#Mann= 3 , 0 , 0
   -11.2    .033       0       0    .033       0     5.1    .033       0
#XS Ineff= 2 , 0
               0   26.51     5.1           27.21
Permanent Ineff=
       F       F
Bank Sta=0,5.1
XS Rating Curve= 0
Exp/Cntr=.3,.1

Type RM Length L Ch R = 1 ,900.00  ,43,43,43
BEGIN DESCRIPTION:
18
END DESCRIPTION:
#Sta/Elev= 10
   -12.4    25.6    -2.4    25.6    -1.8      26       0    26.3      .6    24.6
     3.6    24.6     5.5    26.9     5.8    26.9       6    26.7      16    26.7
#Mann= 3 , 0 , 0
   -12.4    .033       0       0    .033       0     5.5    .033       0
#XS Ineff= 2 , 0
               0    26.3     5.5            26.9
Permanent Ineff=
       F       F
Bank Sta=0,5.5
XS Rating Curve= 0
Exp/Cntr=.3,.1

Type RM Length L Ch R = 1 ,857.00  ,1,1,1
BEGIN DESCRIPTION:
17.007
END DESCRIPTION:
#Sta/Elev= 14
   -11.1   25.36    -1.1   25.36     -.5   25.76       0   25.76     1.5   24.46
     3.8   24.46     8.5   28.66     9.8   28.66    10.6   27.86    12.6   27.86
      13   28.86      16   29.66      19   30.46      22   31.26
#Mann= 3 , 0 , 0
   -11.1    .033       0       0    .033       0     8.5    .033       0
#XS Ineff= 2 , 0
               0   25.76     8.5           28.66
Permanent Ineff=
       F       F
Bank Sta=0,8.5
XS Rating Curve= 0
Exp/Cntr=.3,.1