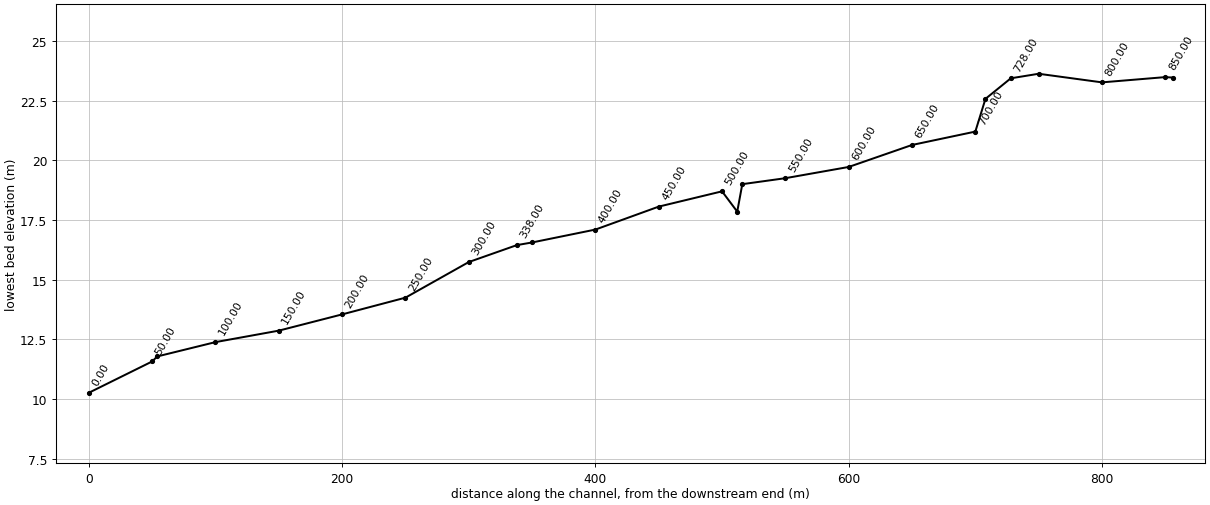
HEC-RAS study DKC.prj: DKC

--- DKC.g01 (geometry) --- (continued)

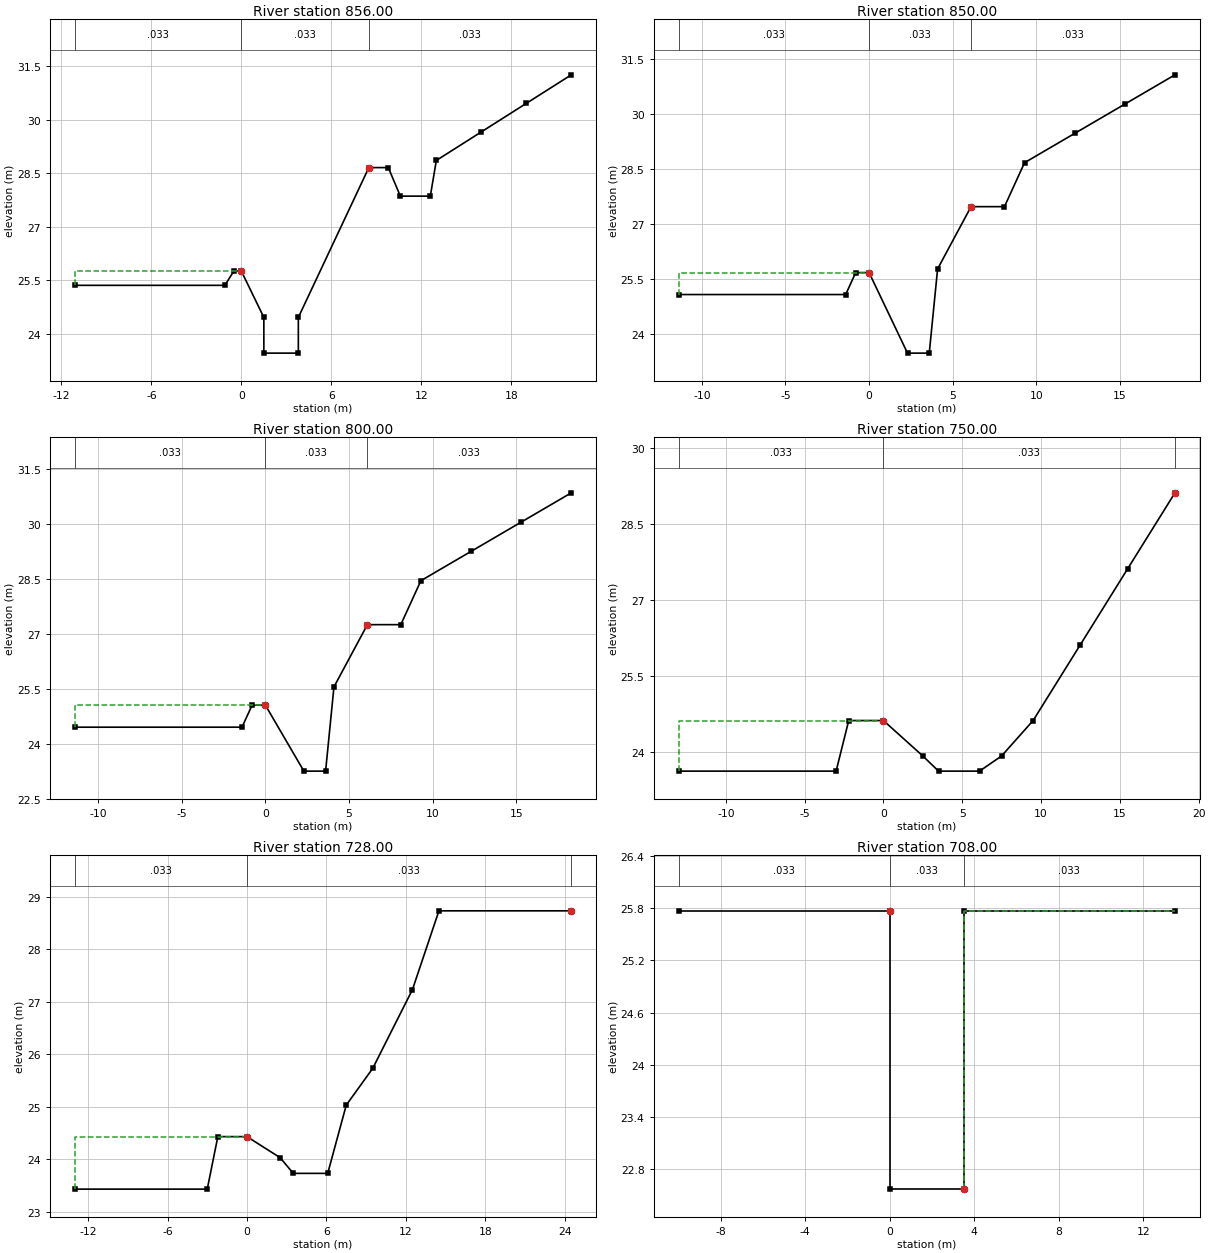
Type RM Length L Ch R = 1 ,856.00  ,6,6,6
BEGIN DESCRIPTION:
17.006
END DESCRIPTION:
#Sta/Elev= 16
   -11.1   25.36    -1.1   25.36     -.5   25.76       0   25.76     1.5   24.46
     1.5   23.46     3.8   23.46     3.8   24.46     8.5   28.66     9.8   28.66
    10.6   27.86    12.6   27.86      13   28.86      16   29.66      19   30.46
      22   31.26
#Mann= 3 , 0 , 0
   -11.1    .033       0       0    .033       0     8.5    .033       0
#XS Ineff= 2 , 0
               0   25.76     8.5           28.66
Permanent Ineff=
       F       F
Bank Sta=0,8.5
XS Rating Curve= 0
Exp/Cntr=.3,.1

Type RM Length L Ch R = 1 ,850.00  ,50,50,50
BEGIN DESCRIPTION:
17
END DESCRIPTION:
#Sta/Elev= 13
   -11.4   25.08    -1.4   25.08     -.8   25.68       0   25.68     2.3   23.48
     3.6   23.48     4.1   25.78     6.1   27.48     8.1   27.48     9.3   28.68
    12.3   29.48    15.3   30.28    18.3   31.08
#Mann= 3 , 0 , 0
   -11.4    .033       0       0    .033       0     6.1    .033       0
#XS Ineff= 2 , 0
               0   25.68     6.1           27.48
Permanent Ineff=
       F       F
Bank Sta=0,6.1
XS Rating Curve= 0
Exp/Cntr=.3,.1

Type RM Length L Ch R = 1 ,800.00  ,50,50,50
BEGIN DESCRIPTION:
16
END DESCRIPTION:
#Sta/Elev= 13
   -11.4   24.46    -1.4   24.46     -.8   25.06       0   25.06     2.3   23.26
     3.6   23.26     4.1   25.56     6.1   27.26     8.1   27.26     9.3   28.46
    12.3   29.26    15.3   30.06    18.3   30.86
#Mann= 3 , 0 , 0
   -11.4    .033       0       0    .033       0     6.1    .033       0
#XS Ineff= 2 , 0
               0   25.06     6.1           27.26
Permanent Ineff=
       F       F
Bank Sta=0,6.1
XS Rating Curve= 0
Exp/Cntr=.3,.1

Type RM Length L Ch R = 1 ,750.00  ,22,22,22
BEGIN DESCRIPTION:
15
END DESCRIPTION:
#Sta/Elev= 12
     -13   23.62      -3   23.62    -2.2   24.62       0   24.62     2.5   23.92
     3.5   23.62     6.1   23.62     7.5   23.92     9.5   24.62    12.5   26.12
    15.5   27.62    18.5   29.12
#Mann= 3 , 0 , 0
     -13    .033       0       0    .033       0    18.5    .033       0
#XS Ineff= 2 , 0
               0   24.62    18.5           29.12
Permanent Ineff=
       F       F
Bank Sta=0,18.5
XS Rating Curve= 0
Exp/Cntr=.3,.1

Type RM Length L Ch R = 1 ,728.00  ,20,20,20
BEGIN DESCRIPTION:
14.028
END DESCRIPTION:
#Sta/Elev= 12
     -13   23.43      -3   23.43    -2.2   24.43       0   24.43     2.5   24.03
     3.5   23.73     6.1   23.73     7.5   25.03     9.5   25.73    12.5   27.23
    14.5   28.73    24.5   28.73
#Mann= 3 , 0 , 0
     -13    .033       0       0    .033       0    24.5    .033       0
#XS Ineff= 2 , 0
               0   24.43    24.5           28.73
Permanent Ineff=
       F       F
Bank Sta=0,24.5
XS Rating Curve= 0
Exp/Cntr=.3,.1

Type RM Length L Ch R = 1 ,708.00  ,8,8,8
BEGIN DESCRIPTION:
14.008
END DESCRIPTION:
#Sta/Elev= 6
     -10   25.77       0   25.77       0   22.57     3.5   22.57     3.5   25.77
    13.5   25.77
#Mann= 3 , 0 , 0
     -10    .033       0       0    .033       0     3.5    .033       0
#XS Ineff= 2 , 0
               0   25.77     3.5           25.77
Permanent Ineff=
       F       F
Bank Sta=0,3.5
XS Rating Curve= 0
Exp/Cntr=.3,.1

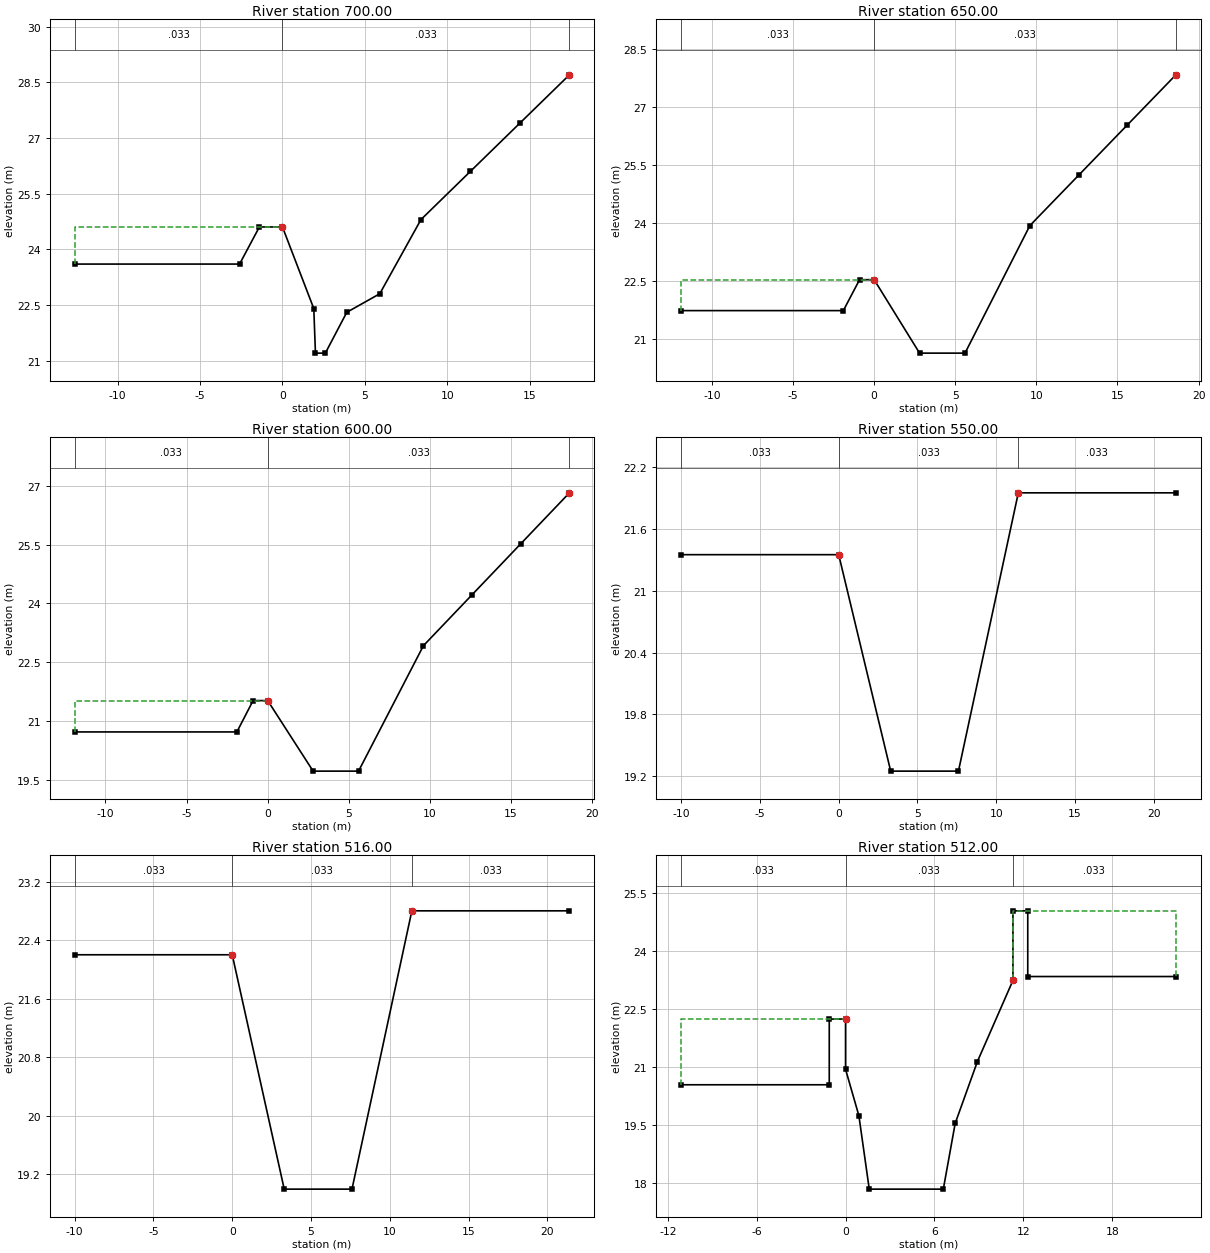
Type RM Length L Ch R = 1 ,700.00  ,50,50,50
BEGIN DESCRIPTION:
14
END DESCRIPTION:
#Sta/Elev= 13
   -12.6    23.6    -2.6    23.6    -1.4    24.6       0    24.6     1.9    22.4
       2    21.2     2.6    21.2     3.9    22.3     5.9    22.8     8.4    24.8
    11.4    26.1    14.4    27.4    17.4    28.7
#Mann= 3 , 0 , 0
   -12.6    .033       0       0    .033       0    17.4    .033       0
#XS Ineff= 2 , 0
               0    24.6    17.4            28.7
Permanent Ineff=
       F       F
Bank Sta=0,17.4
XS Rating Curve= 0
Exp/Cntr=.3,.1

Type RM Length L Ch R = 1 ,650.00  ,50,50,50
BEGIN DESCRIPTION:
13
END DESCRIPTION:
#Sta/Elev= 10
   -11.9   21.74    -1.9   21.74     -.9   22.54       0   22.54     2.8   20.64
     5.6   20.64     9.6   23.94    12.6   25.24    15.6   26.54    18.6   27.84
#Mann= 3 , 0 , 0
   -11.9    .033       0       0    .033       0    18.6    .033       0
#XS Ineff= 2 , 0
               0   22.54    18.6           27.84
Permanent Ineff=
       F       F
Bank Sta=0,18.6
XS Rating Curve= 0
Exp/Cntr=.3,.1

Type RM Length L Ch R = 1 ,600.00  ,50,50,50
BEGIN DESCRIPTION:
12
END DESCRIPTION:
#Sta/Elev= 10
   -11.9   20.72    -1.9   20.72     -.9   21.52       0   21.52     2.8   19.72
     5.6   19.72     9.6   22.92    12.6   24.22    15.6   25.52    18.6   26.82
#Mann= 3 , 0 , 0
   -11.9    .033       0       0    .033       0    18.6    .033       0
#XS Ineff= 2 , 0
               0   21.52    18.6           26.82
Permanent Ineff=
       F       F
Bank Sta=0,18.6
XS Rating Curve= 0
Exp/Cntr=.3,.1

Type RM Length L Ch R = 1 ,550.00  ,34,34,34
BEGIN DESCRIPTION:
11
END DESCRIPTION:
#Sta/Elev= 6
     -10   21.35       0   21.35     3.3   19.25     7.6   19.25    11.4   21.95
    21.4   21.95
#Mann= 3 , 0 , 0
     -10    .033       0       0    .033       0    11.4    .033       0
#XS Ineff= 2 , 0
               0   21.35    11.4           21.95
Permanent Ineff=
       F       F
Bank Sta=0,11.4
XS Rating Curve= 0
Exp/Cntr=.3,.1

Type RM Length L Ch R = 1 ,516.00  ,4,4,4
BEGIN DESCRIPTION:
10.016
END DESCRIPTION:
#Sta/Elev= 6
     -10    22.2       0    22.2     3.3      19     7.6      19    11.4    22.8
    21.4    22.8
#Mann= 3 , 0 , 0
     -10    .033       0       0    .033       0    11.4    .033       0
#XS Ineff= 2 , 0
               0    22.2    11.4            22.8
Permanent Ineff=
       F       F
Bank Sta=0,11.4
XS Rating Curve= 0
Exp/Cntr=.3,.1

Type RM Length L Ch R = 1 ,512.00  ,12,12,12
BEGIN DESCRIPTION:
10.012
END DESCRIPTION:
#Sta/Elev= 15
   -11.1   20.55    -1.1   20.55    -1.1   22.25       0   22.25       0   20.95
      .9   19.75     1.6   17.85     6.6   17.85     7.4   19.55     8.9   21.15
    11.3   23.25    11.3   25.05    12.3   25.05    12.3   23.35    22.3   23.35
#Mann= 3 , 0 , 0
   -11.1    .033       0       0    .033       0    11.3    .033       0
#XS Ineff= 2 , 0
               0   22.25    11.3           25.05
Permanent Ineff=
       F       F
Bank Sta=0,11.3
XS Rating Curve= 0
Exp/Cntr=.3,.1

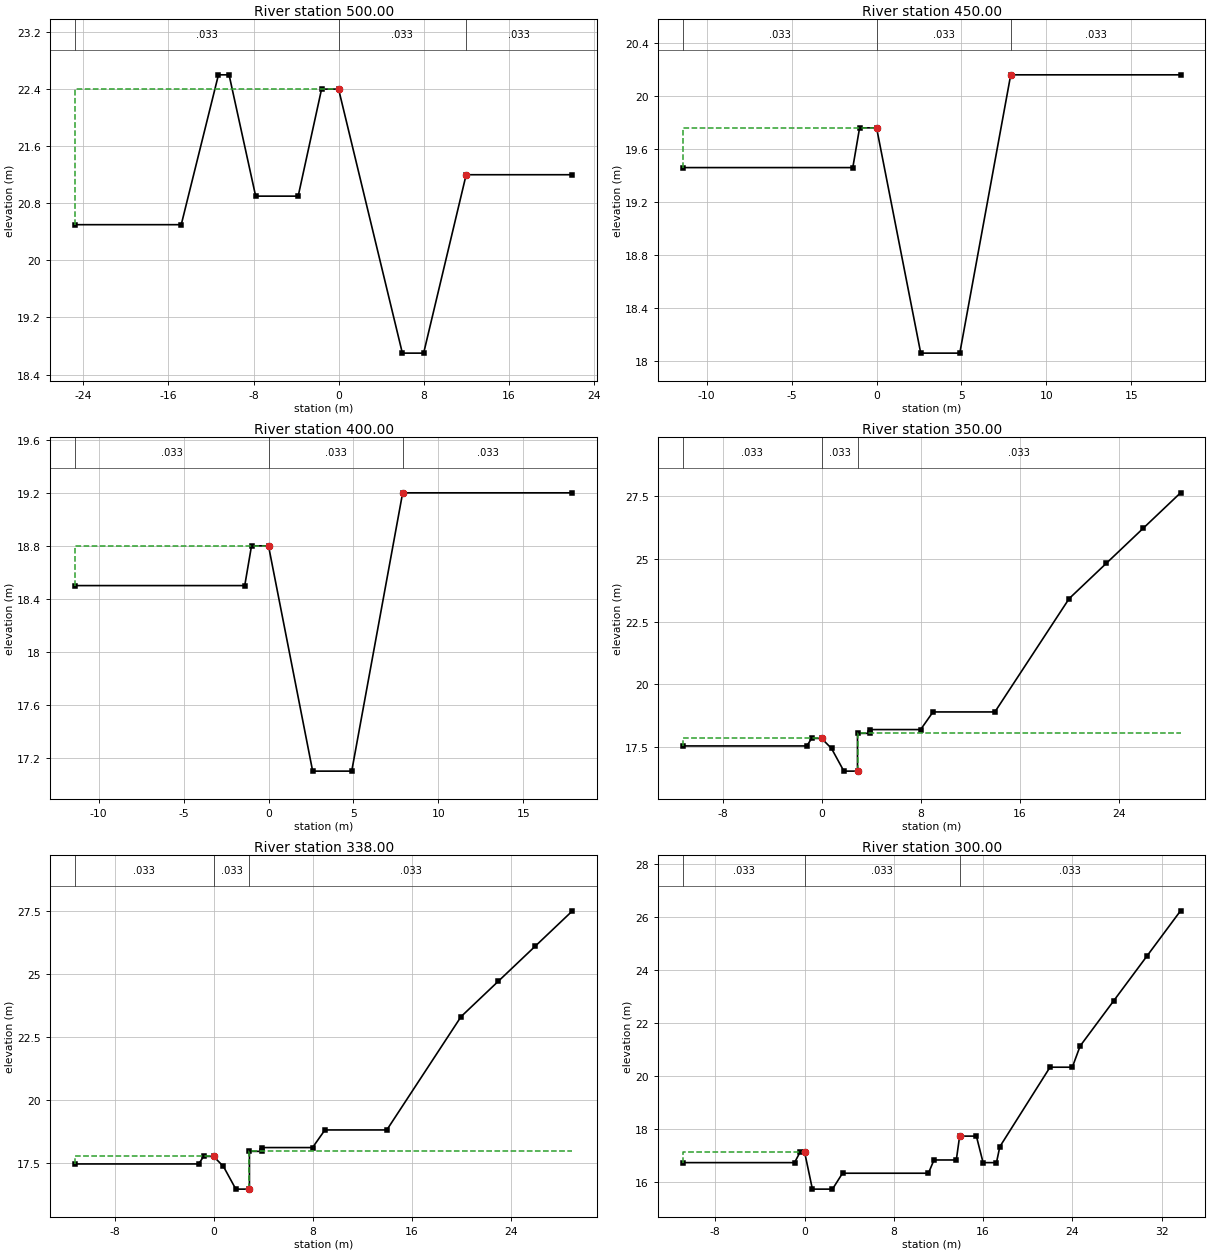
Type RM Length L Ch R = 1 ,500.00  ,50,50,50
BEGIN DESCRIPTION:
10
END DESCRIPTION:
#Sta/Elev= 12
   -24.8    20.5   -14.8    20.5   -11.3    22.6   -10.3    22.6    -7.8    20.9
    -3.8    20.9    -1.6    22.4       0    22.4       6    18.7       8    18.7
      12    21.2      22    21.2
#Mann= 3 , 0 , 0
   -24.8    .033       0       0    .033       0      12    .033       0
#XS Ineff= 2 , 0
               0    22.4      12            21.2
Permanent Ineff=
       F       F
Bank Sta=0,12
XS Rating Curve= 0
Exp/Cntr=.3,.1

Type RM Length L Ch R = 1 ,450.00  ,50,50,50
BEGIN DESCRIPTION:
9
END DESCRIPTION:
#Sta/Elev= 8
   -11.4   19.46    -1.4   19.46      -1   19.76       0   19.76     2.6   18.06
     4.9   18.06     7.9   20.16    17.9   20.16
#Mann= 3 , 0 , 0
   -11.4    .033       0       0    .033       0     7.9    .033       0
#XS Ineff= 2 , 0
               0   19.76     7.9           20.16
Permanent Ineff=
       F       F
Bank Sta=0,7.9
XS Rating Curve= 0
Exp/Cntr=.3,.1

Type RM Length L Ch R = 1 ,400.00  ,50,50,50
BEGIN DESCRIPTION:
8
END DESCRIPTION:
#Sta/Elev= 8
   -11.4    18.5    -1.4    18.5      -1    18.8       0    18.8     2.6    17.1
     4.9    17.1     7.9    19.2    17.9    19.2
#Mann= 3 , 0 , 0
   -11.4    .033       0       0    .033       0     7.9    .033       0
#XS Ineff= 2 , 0
               0    18.8     7.9            19.2
Permanent Ineff=
       F       F
Bank Sta=0,7.9
XS Rating Curve= 0
Exp/Cntr=.3,.1

Type RM Length L Ch R = 1 ,350.00  ,12,12,12
BEGIN DESCRIPTION:
7
END DESCRIPTION:
#Sta/Elev= 17
   -11.2   17.56    -1.2   17.56     -.8   17.86       0   17.86      .8   17.46
     1.8   16.56     2.9   16.56     2.9   18.06     3.9   18.06     3.9   18.21
       8   18.21       9   18.91      14   18.91      20   23.41      23   24.81
      26   26.21      29   27.61
#Mann= 3 , 0 , 0
   -11.2    .033       0       0    .033       0     2.9    .033       0
#XS Ineff= 2 , 0
               0   17.86     2.9           18.06
Permanent Ineff=
       F       F
Bank Sta=0,2.9
XS Rating Curve= 0
Exp/Cntr=.3,.1

Type RM Length L Ch R = 1 ,338.00  ,38,38,38
BEGIN DESCRIPTION:
6.038
END DESCRIPTION:
#Sta/Elev= 17
   -11.2   17.45    -1.2   17.45     -.8   17.75       0   17.75      .8   17.35
     1.8   16.45     2.9   16.45     2.9   17.95     3.9   17.95     3.9    18.1
       8    18.1       9    18.8      14    18.8      20    23.3      23    24.7
      26    26.1      29    27.5
#Mann= 3 , 0 , 0
   -11.2    .033       0       0    .033       0     2.9    .033       0
#XS Ineff= 2 , 0
               0   17.75     2.9           17.95
Permanent Ineff=
       F       F
Bank Sta=0,2.9
XS Rating Curve= 0
Exp/Cntr=.3,.1

Type RM Length L Ch R = 1 ,300.00  ,50,50,50
BEGIN DESCRIPTION:
6
END DESCRIPTION:
#Sta/Elev= 21
   -10.9   16.74     -.9   16.74     -.4   17.14       0   17.14      .7   15.74
     2.5   15.74     3.4   16.34    11.1   16.34    11.6   16.84    13.6   16.84
    13.9   17.74    15.4   17.74      16   16.74    17.2   16.74    17.5   17.34
      22   20.34      24   20.34    24.7   21.14    27.7   22.84    30.7   24.54
    33.7   26.24
#Mann= 3 , 0 , 0
   -10.9    .033       0       0    .033       0    13.9    .033       0
#XS Ineff= 2 , 0
               0   17.14    13.9           17.74
Permanent Ineff=
       F       F
Bank Sta=0,13.9
XS Rating Curve= 0
Exp/Cntr=.3,.1

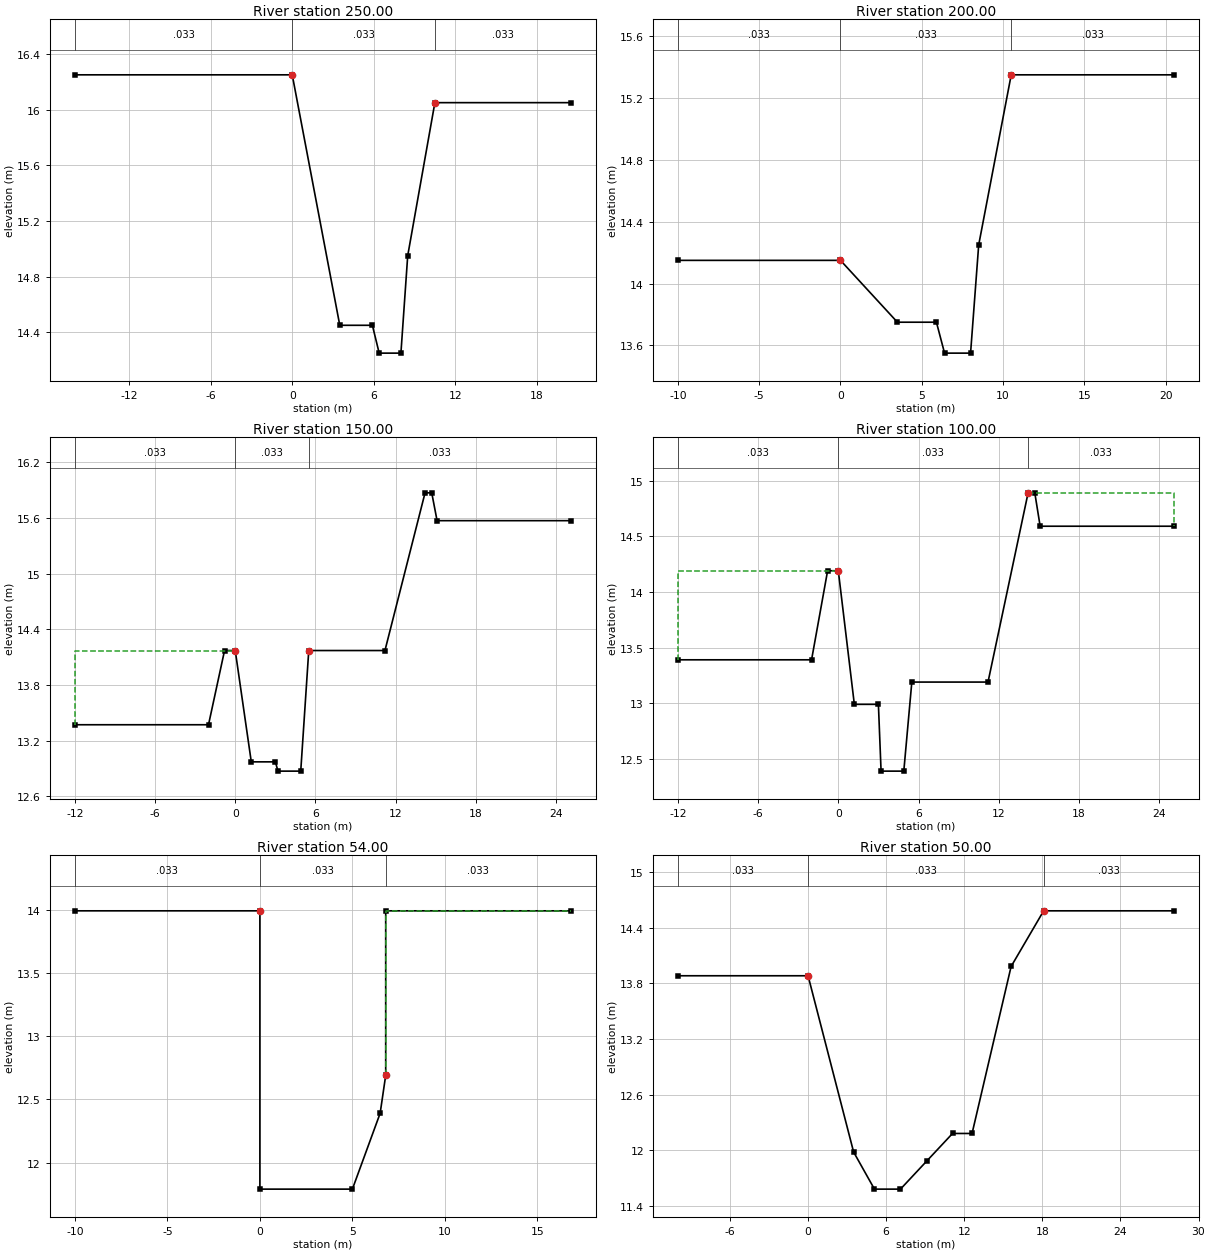
Type RM Length L Ch R = 1 ,250.00  ,50,50,50
BEGIN DESCRIPTION:
5
END DESCRIPTION:
#Sta/Elev= 9
     -16   16.25       0   16.25     3.5   14.45     5.9   14.45     6.4   14.25
       8   14.25     8.5   14.95    10.5   16.05    20.5   16.05
#Mann= 3 , 0 , 0
     -16    .033       0       0    .033       0    10.5    .033       0
#XS Ineff= 2 , 0
               0   16.25    10.5           16.05
Permanent Ineff=
       F       F
Bank Sta=0,10.5
XS Rating Curve= 0
Exp/Cntr=.3,.1

Type RM Length L Ch R = 1 ,200.00  ,50,50,50
BEGIN DESCRIPTION:
4
END DESCRIPTION:
#Sta/Elev= 9
     -10   14.15       0   14.15     3.5   13.75     5.9   13.75     6.4   13.55
       8   13.55     8.5   14.25    10.5   15.35    20.5   15.35
#Mann= 3 , 0 , 0
     -10    .033       0       0    .033       0    10.5    .033       0
#XS Ineff= 2 , 0
               0   14.15    10.5           15.35
Permanent Ineff=
       F       F
Bank Sta=0,10.5
XS Rating Curve= 0
Exp/Cntr=.3,.1

Type RM Length L Ch R = 1 ,150.00  ,50,50,50
BEGIN DESCRIPTION:
3
END DESCRIPTION:
#Sta/Elev= 14
     -12   13.37      -2   13.37     -.8   14.17       0   14.17     1.2   12.97
       3   12.97     3.2   12.87     4.9   12.87     5.5   14.17    11.2   14.17
    14.2   15.87    14.7   15.87    15.1   15.57    25.1   15.57
#Mann= 3 , 0 , 0
     -12    .033       0       0    .033       0     5.5    .033       0
#XS Ineff= 2 , 0
               0   14.17     5.5           14.17
Permanent Ineff=
       F       F
Bank Sta=0,5.5
XS Rating Curve= 0
Exp/Cntr=.3,.1

Type RM Length L Ch R = 1 ,100.00  ,46,46,46
BEGIN DESCRIPTION:
2
END DESCRIPTION:
#Sta/Elev= 14
     -12   13.39      -2   13.39     -.8   14.19       0   14.19     1.2   12.99
       3   12.99     3.2   12.39     4.9   12.39     5.5   13.19    11.2   13.19
    14.2   14.89    14.7   14.89    15.1   14.59    25.1   14.59
#Mann= 3 , 0 , 0
     -12    .033       0       0    .033       0    14.2    .033       0
#XS Ineff= 2 , 0
               0   14.19    14.2           14.89
Permanent Ineff=
       F       F
Bank Sta=0,14.2
XS Rating Curve= 0
Exp/Cntr=.3,.1

Type RM Length L Ch R = 1 ,54.00   ,4,4,4
BEGIN DESCRIPTION:
1.004
END DESCRIPTION:
#Sta/Elev= 8
     -10   13.99       0   13.99       0   11.79       5   11.79     6.5   12.39
     6.8   12.69     6.8   13.99    16.8   13.99
#Mann= 3 , 0 , 0
     -10    .033       0       0    .033       0     6.8    .033       0
#XS Ineff= 2 , 0
               0   13.99     6.8           13.99
Permanent Ineff=
       F       F
Bank Sta=0,6.8
XS Rating Curve= 0
Exp/Cntr=.3,.1

Type RM Length L Ch R = 1 ,50.00   ,50,50,50
BEGIN DESCRIPTION:
1
END DESCRIPTION:
#Sta/Elev= 11
     -10   13.88       0   13.88     3.5   11.98     5.1   11.58     7.1   11.58
     9.1   11.88    11.1   12.18    12.6   12.18    15.6   13.98    18.1   14.58
    28.1   14.58
#Mann= 3 , 0 , 0
     -10    .033       0       0    .033       0    18.1    .033       0
#XS Ineff= 2 , 0
               0   13.88    18.1           14.58
Permanent Ineff=
       F       F
Bank Sta=0,18.1
XS Rating Curve= 0
Exp/Cntr=.3,.1

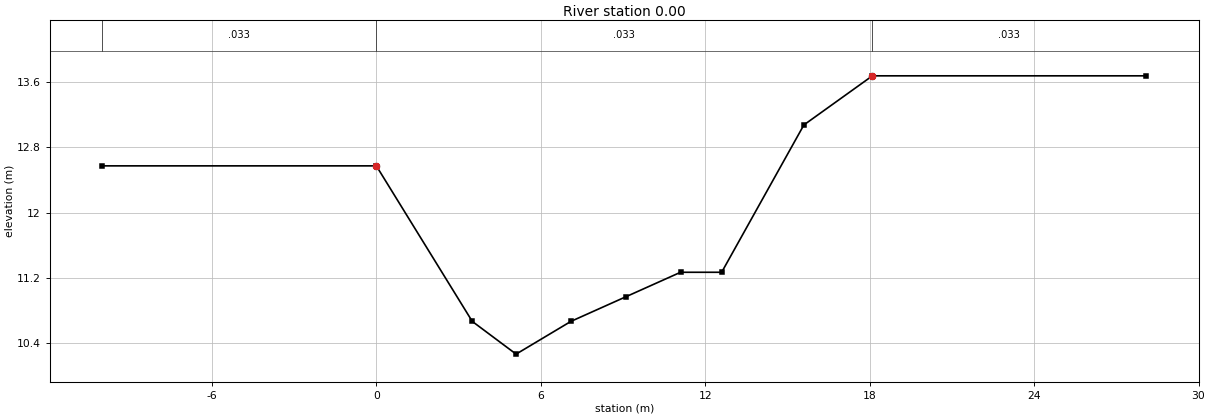
Type RM Length L Ch R = 1 ,0.00    ,0,0,0
BEGIN DESCRIPTION:
0
END DESCRIPTION:
#Sta/Elev= 11
     -10   12.57       0   12.57     3.5   10.67     5.1   10.27     7.1   10.67
     9.1   10.97    11.1   11.27    12.6   11.27    15.6   13.07    18.1   13.67
    28.1   13.67
#Mann= 3 , 0 , 0
     -10    .033       0       0    .033       0    18.1    .033       0
#XS Ineff= 2 , 0
               0   12.57    18.1           13.67
Permanent Ineff=
       F       F
Bank Sta=0,18.1
XS Rating Curve= 0
Exp/Cntr=.3,.1

Chan Stop Cuts=-1