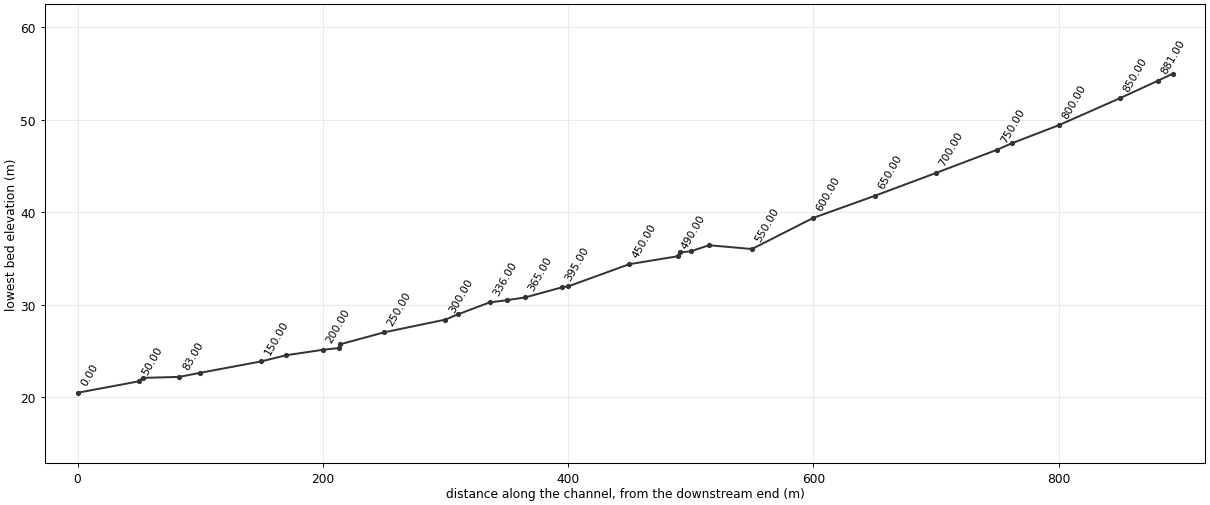
--- OYAT.prj (project) ---

Proj Title=OYAT
Current Plan=p01
Default Exp/Contr=.3,.1
SI Units
Geom File=g01
Flow File=f01
Plan File=p01
Y Axis Title=Elevation
X Axis Title(PF)=Main Channel Distance
X Axis Title(XS)=Station
BEGIN DESCRIPTION:
           BACK WATER COMPUTATION
      APPLICATION OF HEC-2 BY Samju Construction Engineering
      OYAT-STREEM : 30 YR
END DESCRIPTION:
DSS Export Rating Curves= 0
DSS Export Rating Curve Sorted= 0
DSS Export Volume Flow Curves= 0
DXF OffsetX= 0
DXF OffsetY= 0
DXF ScaleX= 1
DXF ScaleY= 10

--- OYAT.p01 (plan) ---

Plan Title=Imported Plan 01
Version=Version 3.0.1  Mar 2001
Short Identifier=Imported Pla
Geom File=g01
Flow File=f01
Subcritical Flow
K Sum by GR= 0
Std Step Tol= 0.003
Critical Tol= 0.003
Num of Std Step Trials= 20
Max Error Tol= 0.1
Flow Tol Ratio= 0.001
Split Flow NTrial= 30
Split Flow Tol= 0.02
Split Flow Ratio= 0.02
Log Output Level= 0
Friction Slope Method= 1
Unsteady Friction Slope Method= 2
Parabolic Critical Depth
Global Vel Dist= 0 , 0 , 0
Global Log Level= 0
CheckData=True
Encroach Param=-1 ,0,0, 0
Computation Interval=1HOUR
Output Interval=1HOUR
Run HTab= 0
Run UNet= 0
Run PostProcess= 0
UNET Theta= 1
UNET ZTol= 0.02
UNET ZSATol= 0.1
UNET MxIter= 20
UNET MaxInSteps= 20
UNET DtIC= 0
UNET DtMin= 0
UNET MaxCRTS= 20
UNET WFStab= 2
UNET SFStab= 1
UNET WFX= 1
UNET SFX= 1
UNET Convert EG Bridges=-1
UNET Use Existing IB Tables=-1
Instantaneous Interval=1HOUR
Write IC File= 0
Write Velocity= 0
Write Detailed= 0

--- OYAT.f01 (steady flow) ---

Flow Title=Imported Flow 01
Version=Version 3.0.1  Mar 2001
Number of Profiles= 5
Profile Names=10YR,20YR,30YR,50YR,80YR
River Rch & RM=RIVER-1,Reach-1         ,17.043
    5.61    6.19    6.52    6.94    7.33
River Rch & RM=OYAT,OYAT            ,893.00
    5.61    6.19    6.52    6.94    7.33
Boundary for River Rch & Prof#=OYAT,OYAT            , 1
Up Type= 0
Dn Type= 3
Dn Slope=.036
Boundary for River Rch & Prof#=OYAT,OYAT            , 2
Up Type= 0
Dn Type= 3
Dn Slope=.036
Boundary for River Rch & Prof#=OYAT,OYAT            , 3
Up Type= 0
Dn Type= 3
Dn Slope=.036
Boundary for River Rch & Prof#=OYAT,OYAT            , 4
Up Type= 0
Dn Type= 3
Dn Slope=.036
Boundary for River Rch & Prof#=OYAT,OYAT            , 5
Up Type= 0
Dn Type= 3
Dn Slope=.036
DSS Import GetInterval= 0
DSS Import GetPeak= 0
DSS Import FillOption= 0

--- OYAT.g01 (geometry) ---

Geom Title=Imported Geom 01
Version=Version 3.0.1  Mar 2001

River Reach=OYAT            ,OYAT
Reach XY= 2
              .5             .95              .5             .05

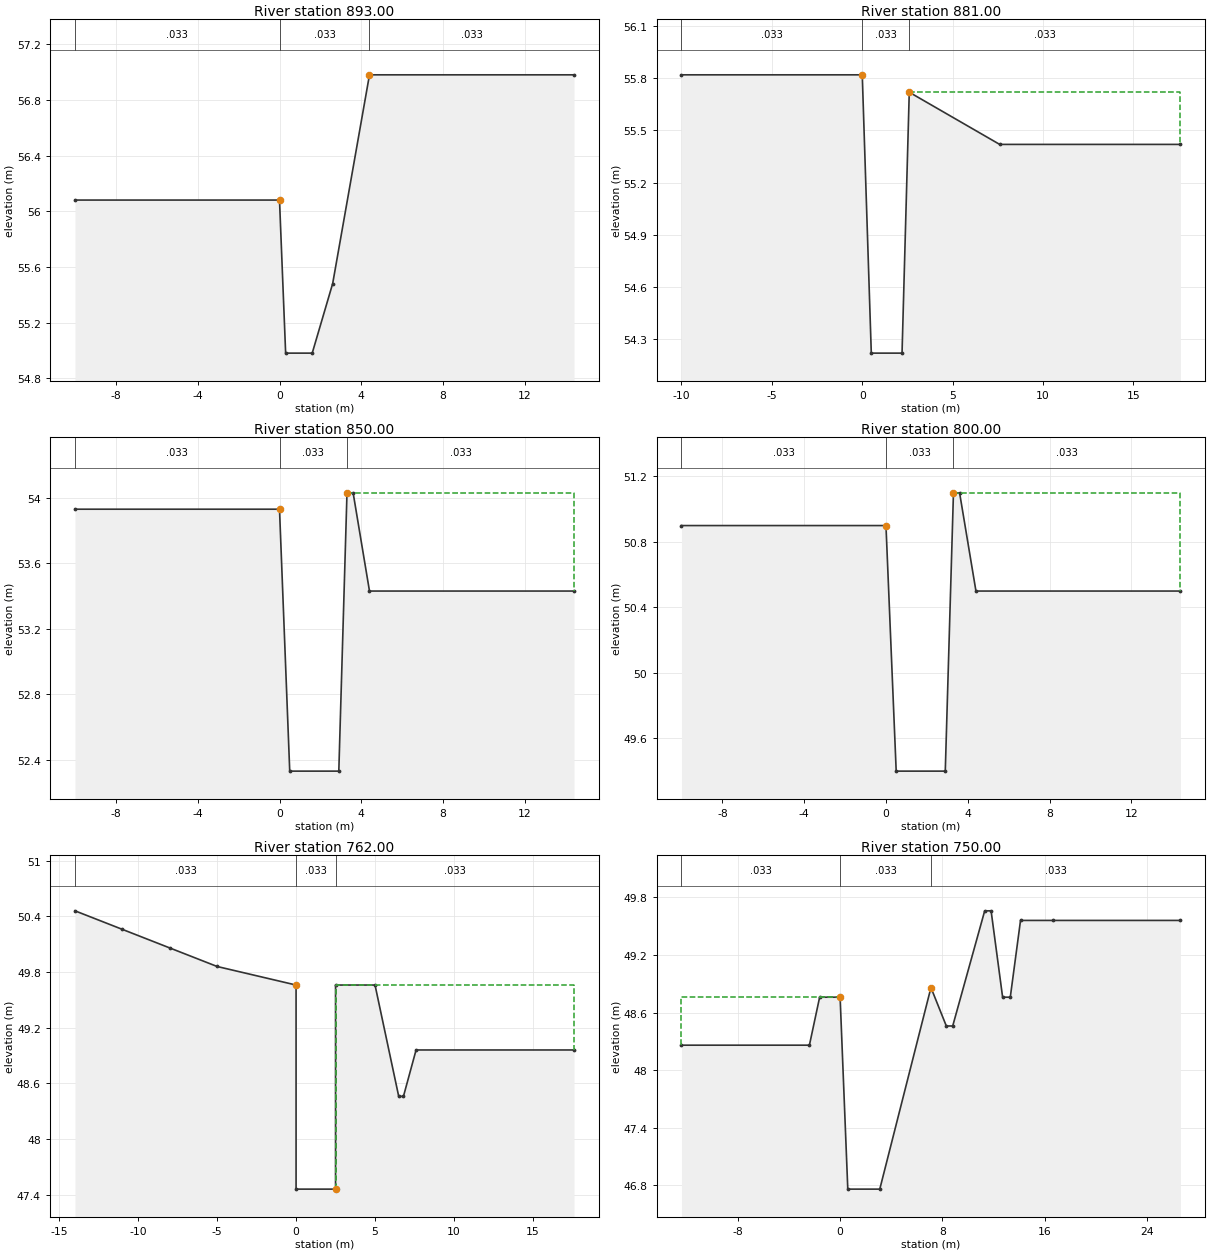
Type RM Length L Ch R = 1 ,893.00  ,12,12,12
BEGIN DESCRIPTION:
17.043
END DESCRIPTION:
#Sta/Elev= 7
     -10   56.08       0   56.08      .3   54.98     1.6   54.98     2.6   55.48
     4.4   56.98    14.4   56.98
#Mann= 3 , 0 , 0
     -10    .033       0       0    .033       0     4.4    .033       0
#XS Ineff= 2 , 0
               0   56.08     4.4           56.98
Permanent Ineff=
       F       F
Bank Sta=0,4.4
XS Rating Curve= 0
Exp/Cntr=.3,.1

Type RM Length L Ch R = 1 ,881.00  ,31,31,31
BEGIN DESCRIPTION:
17.031
END DESCRIPTION:
#Sta/Elev= 7
     -10   55.82       0   55.82      .5   54.22     2.2   54.22     2.6   55.72
     7.6   55.42    17.6   55.42
#Mann= 3 , 0 , 0
     -10    .033       0       0    .033       0     2.6    .033       0
#XS Ineff= 2 , 0
               0   55.82     2.6           55.72
Permanent Ineff=
       F       F
Bank Sta=0,2.6
XS Rating Curve= 0
Exp/Cntr=.3,.1

Type RM Length L Ch R = 1 ,850.00  ,50,50,50
BEGIN DESCRIPTION:
17
END DESCRIPTION:
#Sta/Elev= 8
     -10   53.93       0   53.93      .5   52.33     2.9   52.33     3.3   54.03
     3.6   54.03     4.4   53.43    14.4   53.43
#Mann= 3 , 0 , 0
     -10    .033       0       0    .033       0     3.3    .033       0
#XS Ineff= 2 , 0
               0   53.93     3.3           54.03
Permanent Ineff=
       F       F
Bank Sta=0,3.3
XS Rating Curve= 0
Exp/Cntr=.3,.1

Type RM Length L Ch R = 1 ,800.00  ,38,38,38
BEGIN DESCRIPTION:
16
END DESCRIPTION:
#Sta/Elev= 8
     -10    50.9       0    50.9      .5    49.4     2.9    49.4     3.3    51.1
     3.6    51.1     4.4    50.5    14.4    50.5
#Mann= 3 , 0 , 0
     -10    .033       0       0    .033       0     3.3    .033       0
#XS Ineff= 2 , 0
               0    50.9     3.3            51.1
Permanent Ineff=
       F       F
Bank Sta=0,3.3
XS Rating Curve= 0
Exp/Cntr=.3,.1

Type RM Length L Ch R = 1 ,762.00  ,12,12,12
BEGIN DESCRIPTION:
15.012
END DESCRIPTION:
#Sta/Elev= 13
     -14   50.46     -11   50.26      -8   50.06      -5   49.86       0   49.66
       0   47.46     2.5   47.46     2.5   49.66       5   49.66     6.5   48.46
     6.8   48.46     7.6   48.96    17.6   48.96
#Mann= 3 , 0 , 0
     -14    .033       0       0    .033       0     2.5    .033       0
#XS Ineff= 2 , 0
               0   49.66     2.5           49.66
Permanent Ineff=
       F       F
Bank Sta=0,2.5
XS Rating Curve= 0
Exp/Cntr=.3,.1

Type RM Length L Ch R = 1 ,750.00  ,50,50,50
BEGIN DESCRIPTION:
15
END DESCRIPTION:
#Sta/Elev= 16
   -12.4   48.26    -2.4   48.26    -1.6   48.76       0   48.76      .6   46.76
     3.1   46.76     7.1   48.86     8.3   48.46     8.8   48.46    11.3   49.66
    11.8   49.66    12.7   48.76    13.3   48.76    14.1   49.56    16.6   49.56
    26.6   49.56
#Mann= 3 , 0 , 0
   -12.4    .033       0       0    .033       0     7.1    .033       0
#XS Ineff= 2 , 0
               0   48.76     7.1           48.86
Permanent Ineff=
       F       F
Bank Sta=0,7.1
XS Rating Curve= 0
Exp/Cntr=.3,.1

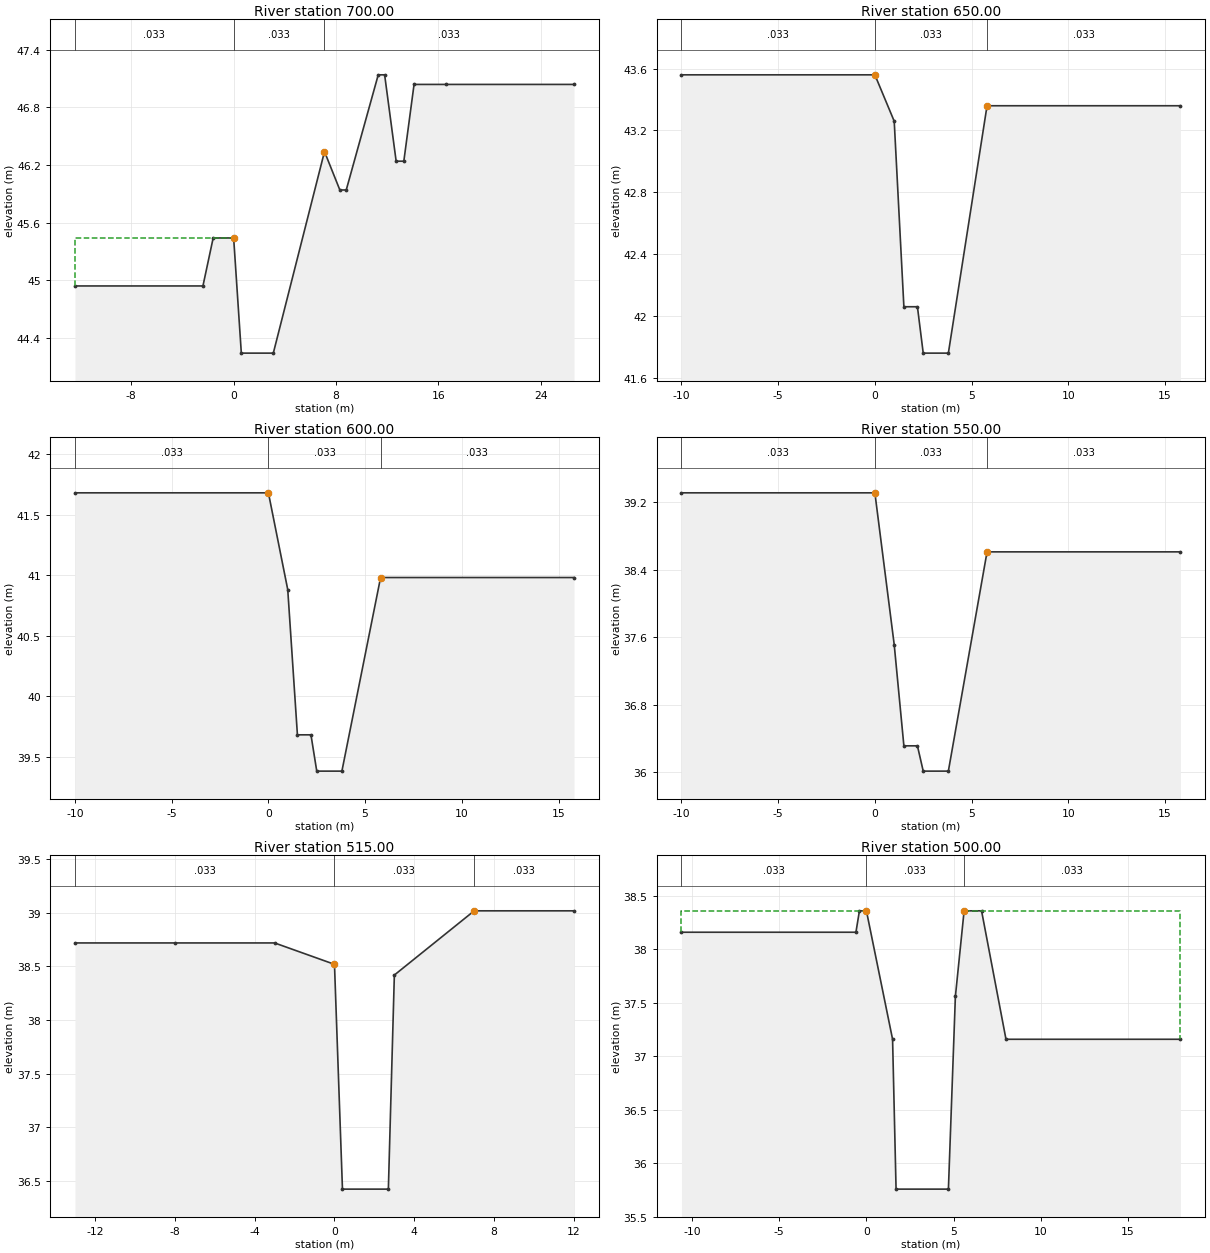
Type RM Length L Ch R = 1 ,700.00  ,50,50,50
BEGIN DESCRIPTION:
14
END DESCRIPTION:
#Sta/Elev= 16
   -12.4   44.94    -2.4   44.94    -1.6   45.44       0   45.44      .6   44.24
     3.1   44.24     7.1   46.34     8.3   45.94     8.8   45.94    11.3   47.14
    11.8   47.14    12.7   46.24    13.3   46.24    14.1   47.04    16.6   47.04
    26.6   47.04
#Mann= 3 , 0 , 0
   -12.4    .033       0       0    .033       0     7.1    .033       0
#XS Ineff= 2 , 0
               0   45.44     7.1           46.34
Permanent Ineff=
       F       F
Bank Sta=0,7.1
XS Rating Curve= 0
Exp/Cntr=.3,.1

Type RM Length L Ch R = 1 ,650.00  ,50,50,50
BEGIN DESCRIPTION:
13
END DESCRIPTION:
#Sta/Elev= 9
     -10   43.56       0   43.56       1   43.26     1.5   42.06     2.2   42.06
     2.5   41.76     3.8   41.76     5.8   43.36    15.8   43.36
#Mann= 3 , 0 , 0
     -10    .033       0       0    .033       0     5.8    .033       0
#XS Ineff= 2 , 0
               0   43.56     5.8           43.36
Permanent Ineff=
       F       F
Bank Sta=0,5.8
XS Rating Curve= 0
Exp/Cntr=.3,.1

Type RM Length L Ch R = 1 ,600.00  ,50,50,50
BEGIN DESCRIPTION:
12
END DESCRIPTION:
#Sta/Elev= 9
     -10   41.68       0   41.68       1   40.88     1.5   39.68     2.2   39.68
     2.5   39.38     3.8   39.38     5.8   40.98    15.8   40.98
#Mann= 3 , 0 , 0
     -10    .033       0       0    .033       0     5.8    .033       0
#XS Ineff= 2 , 0
               0   41.68     5.8           40.98
Permanent Ineff=
       F       F
Bank Sta=0,5.8
XS Rating Curve= 0
Exp/Cntr=.3,.1

Type RM Length L Ch R = 1 ,550.00  ,35,35,35
BEGIN DESCRIPTION:
11
END DESCRIPTION:
#Sta/Elev= 9
     -10   39.31       0   39.31       1   37.51     1.5   36.31     2.2   36.31
     2.5   36.01     3.8   36.01     5.8   38.61    15.8   38.61
#Mann= 3 , 0 , 0
     -10    .033       0       0    .033       0     5.8    .033       0
#XS Ineff= 2 , 0
               0   39.31     5.8           38.61
Permanent Ineff=
       F       F
Bank Sta=0,5.8
XS Rating Curve= 0
Exp/Cntr=.3,.1

Type RM Length L Ch R = 1 ,515.00  ,15,15,15
BEGIN DESCRIPTION:
10.015
END DESCRIPTION:
#Sta/Elev= 9
     -13   38.72      -8   38.72      -3   38.72       0   38.52      .4   36.42
     2.7   36.42       3   38.42       7   39.02      12   39.02
#Mann= 3 , 0 , 0
     -13    .033       0       0    .033       0       7    .033       0
#XS Ineff= 2 , 0
               0   38.52       7           39.02
Permanent Ineff=
       F       F
Bank Sta=0,7
XS Rating Curve= 0
Exp/Cntr=.3,.1

Type RM Length L Ch R = 1 ,500.00  ,9,9,9
BEGIN DESCRIPTION:
10
END DESCRIPTION:
#Sta/Elev= 12
   -10.6   38.16     -.6   38.16     -.4   38.36       0   38.36     1.5   37.16
     1.7   35.76     4.7   35.76     5.1   37.56     5.6   38.36     6.6   38.36
       8   37.16      18   37.16
#Mann= 3 , 0 , 0
   -10.6    .033       0       0    .033       0     5.6    .033       0
#XS Ineff= 2 , 0
               0   38.36     5.6           38.36
Permanent Ineff=
       F       F
Bank Sta=0,5.6
XS Rating Curve= 0
Exp/Cntr=.3,.1

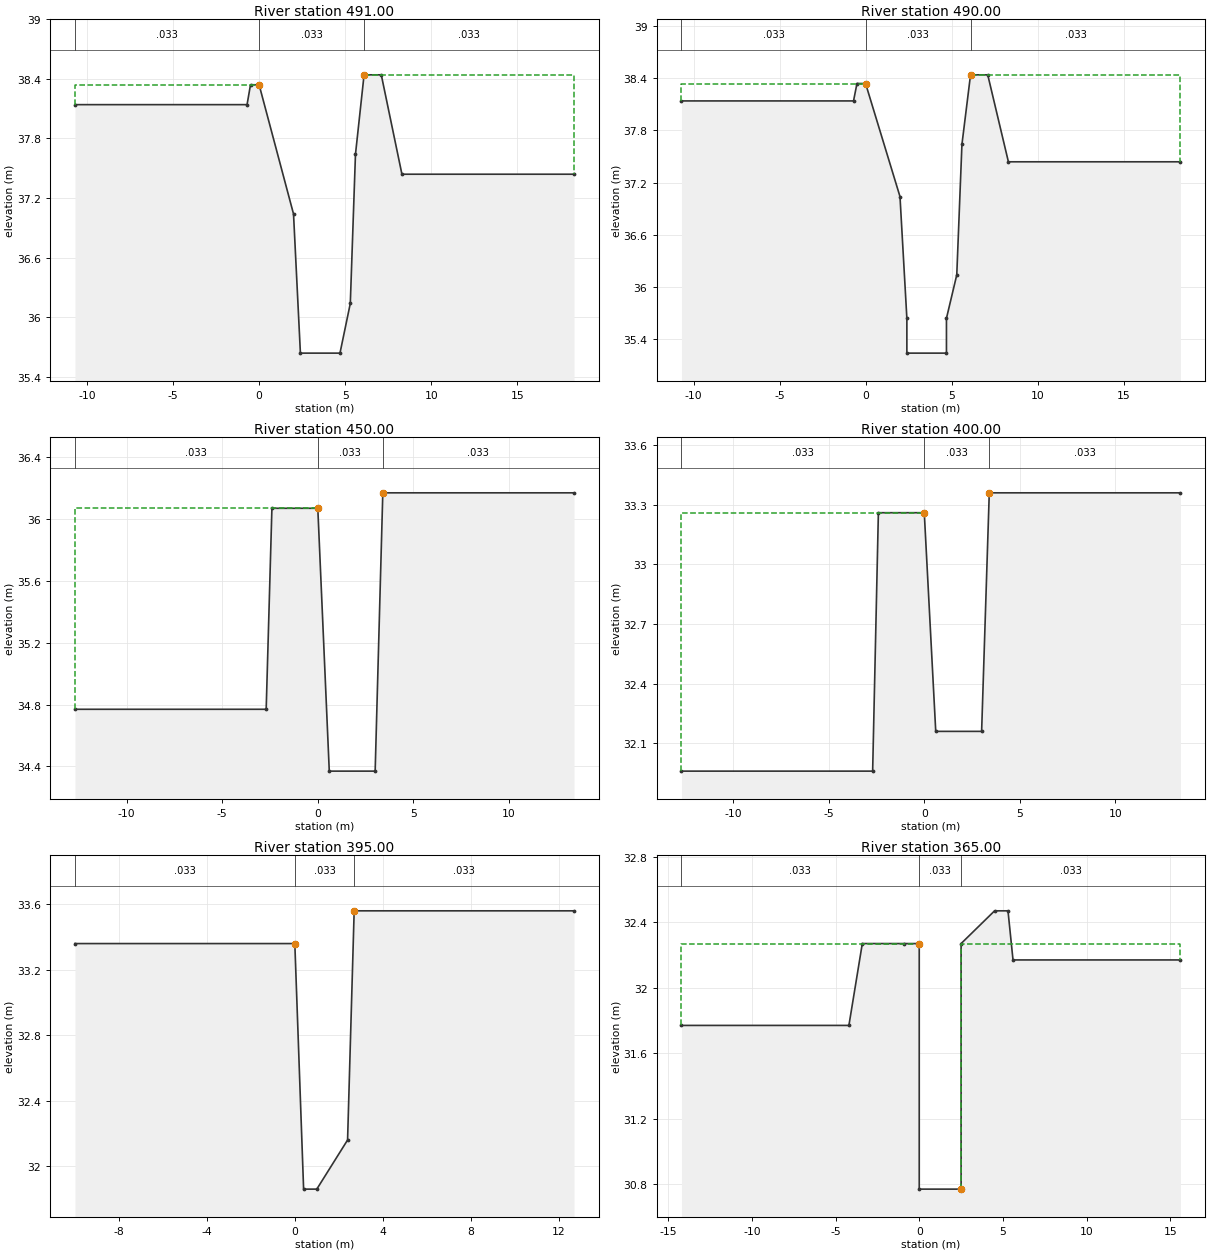
Type RM Length L Ch R = 1 ,491.00  ,1,1,1
BEGIN DESCRIPTION:
9.041
END DESCRIPTION:
#Sta/Elev= 13
   -10.7   38.14     -.7   38.14     -.5   38.34       0   38.34       2   37.04
     2.4   35.64     4.7   35.64     5.3   36.14     5.6   37.64     6.1   38.44
     7.1   38.44     8.3   37.44    18.3   37.44
#Mann= 3 , 0 , 0
   -10.7    .033       0       0    .033       0     6.1    .033       0
#XS Ineff= 2 , 0
               0   38.34     6.1           38.44
Permanent Ineff=
       F       F
Bank Sta=0,6.1
XS Rating Curve= 0
Exp/Cntr=.3,.1

Type RM Length L Ch R = 1 ,490.00  ,40,40,40
BEGIN DESCRIPTION:
9.04
END DESCRIPTION:
#Sta/Elev= 15
   -10.7   38.14     -.7   38.14     -.5   38.34       0   38.34       2   37.04
     2.4   35.64     2.4   35.24     4.7   35.24     4.7   35.64     5.3   36.14
     5.6   37.64     6.1   38.44     7.1   38.44     8.3   37.44    18.3   37.44
#Mann= 3 , 0 , 0
   -10.7    .033       0       0    .033       0     6.1    .033       0
#XS Ineff= 2 , 0
               0   38.34     6.1           38.44
Permanent Ineff=
       F       F
Bank Sta=0,6.1
XS Rating Curve= 0
Exp/Cntr=.3,.1

Type RM Length L Ch R = 1 ,450.00  ,50,50,50
BEGIN DESCRIPTION:
9
END DESCRIPTION:
#Sta/Elev= 8
   -12.7   34.77    -2.7   34.77    -2.4   36.07       0   36.07      .6   34.37
       3   34.37     3.4   36.17    13.4   36.17
#Mann= 3 , 0 , 0
   -12.7    .033       0       0    .033       0     3.4    .033       0
#XS Ineff= 2 , 0
               0   36.07     3.4           36.17
Permanent Ineff=
       F       F
Bank Sta=0,3.4
XS Rating Curve= 0
Exp/Cntr=.3,.1

Type RM Length L Ch R = 1 ,400.00  ,5,5,5
BEGIN DESCRIPTION:
8
END DESCRIPTION:
#Sta/Elev= 8
   -12.7   31.96    -2.7   31.96    -2.4   33.26       0   33.26      .6   32.16
       3   32.16     3.4   33.36    13.4   33.36
#Mann= 3 , 0 , 0
   -12.7    .033       0       0    .033       0     3.4    .033       0
#XS Ineff= 2 , 0
               0   33.26     3.4           33.36
Permanent Ineff=
       F       F
Bank Sta=0,3.4
XS Rating Curve= 0
Exp/Cntr=.3,.1

Type RM Length L Ch R = 1 ,395.00  ,30,30,30
BEGIN DESCRIPTION:
7.045
END DESCRIPTION:
#Sta/Elev= 7
     -10   33.36       0   33.36      .4   31.86       1   31.86     2.4   32.16
     2.7   33.56    12.7   33.56
#Mann= 3 , 0 , 0
     -10    .033       0       0    .033       0     2.7    .033       0
#XS Ineff= 2 , 0
               0   33.36     2.7           33.56
Permanent Ineff=
       F       F
Bank Sta=0,2.7
XS Rating Curve= 0
Exp/Cntr=.3,.1

Type RM Length L Ch R = 1 ,365.00  ,15,15,15
BEGIN DESCRIPTION:
7.015
END DESCRIPTION:
#Sta/Elev= 12
   -14.2   31.77    -4.2   31.77    -3.4   32.27     -.9   32.27       0   32.27
       0   30.77     2.5   30.77     2.5   32.27     4.5   32.47     5.3   32.47
     5.6   32.17    15.6   32.17
#Mann= 3 , 0 , 0
   -14.2    .033       0       0    .033       0     2.5    .033       0
#XS Ineff= 2 , 0
               0   32.27     2.5           32.27
Permanent Ineff=
       F       F
Bank Sta=0,2.5
XS Rating Curve= 0
Exp/Cntr=.3,.1

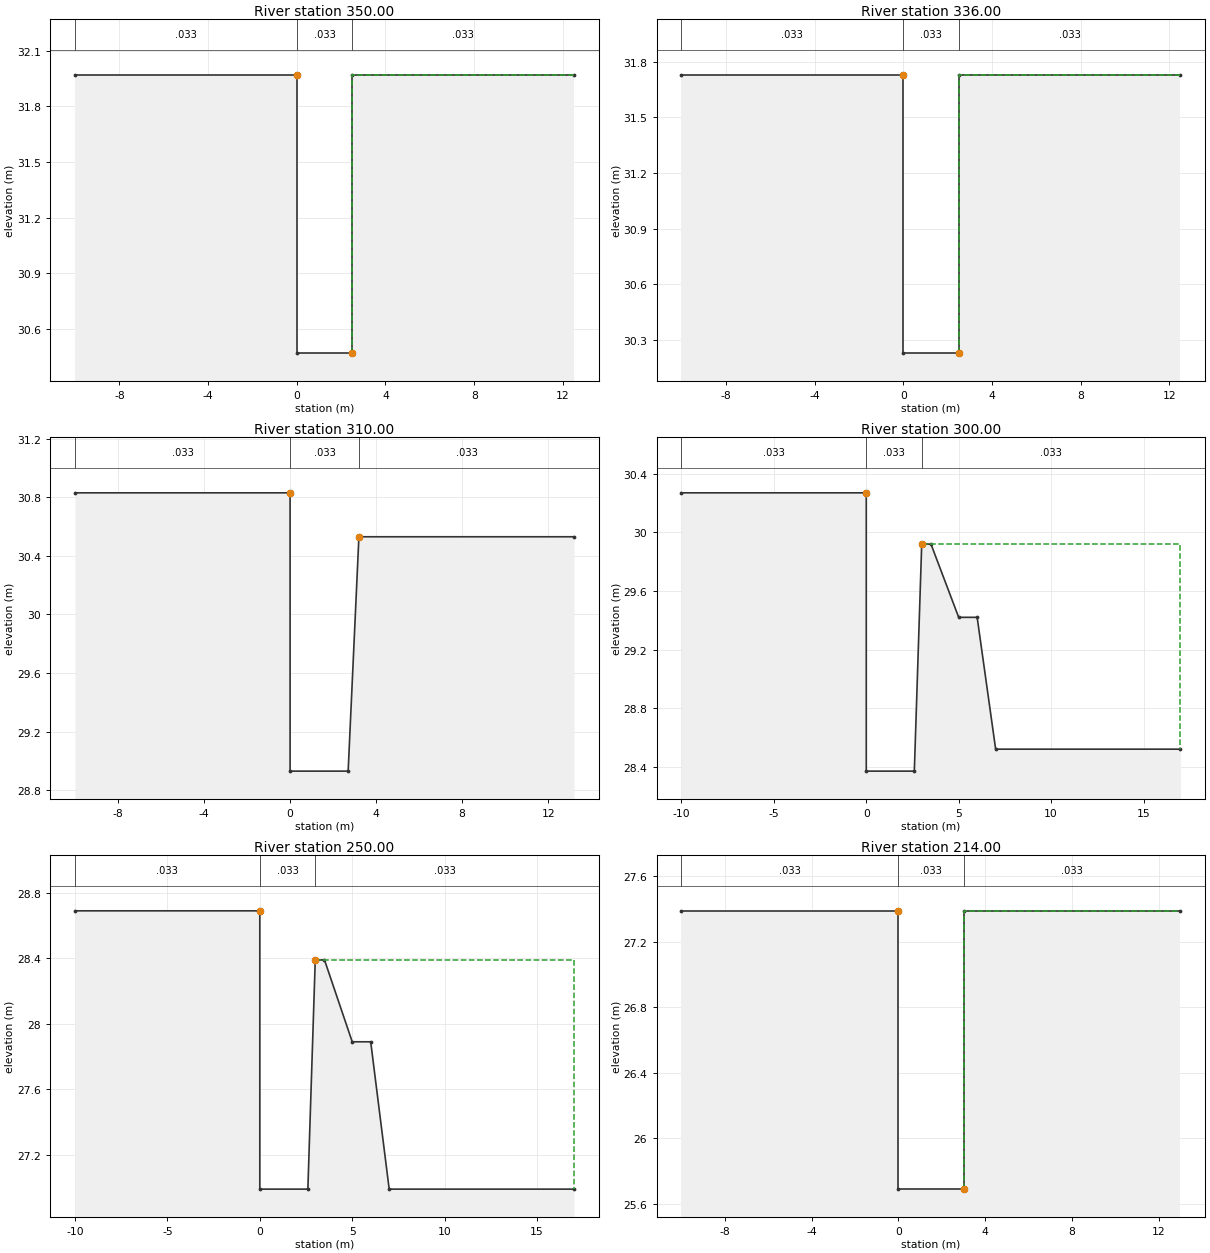
Type RM Length L Ch R = 1 ,350.00  ,14,14,14
BEGIN DESCRIPTION:
7
END DESCRIPTION:
#Sta/Elev= 6
     -10   31.97       0   31.97       0   30.47     2.5   30.47     2.5   31.97
    12.5   31.97
#Mann= 3 , 0 , 0
     -10    .033       0       0    .033       0     2.5    .033       0
#XS Ineff= 2 , 0
               0   31.97     2.5           31.97
Permanent Ineff=
       F       F
Bank Sta=0,2.5
XS Rating Curve= 0
Exp/Cntr=.3,.1

Type RM Length L Ch R = 1 ,336.00  ,26,26,26
BEGIN DESCRIPTION:
6.036
END DESCRIPTION:
#Sta/Elev= 6
     -10   31.73       0   31.73       0   30.23     2.5   30.23     2.5   31.73
    12.5   31.73
#Mann= 3 , 0 , 0
     -10    .033       0       0    .033       0     2.5    .033       0
#XS Ineff= 2 , 0
               0   31.73     2.5           31.73
Permanent Ineff=
       F       F
Bank Sta=0,2.5
XS Rating Curve= 0
Exp/Cntr=.3,.1

Type RM Length L Ch R = 1 ,310.00  ,10,10,10
BEGIN DESCRIPTION:
6.01
END DESCRIPTION:
#Sta/Elev= 6
     -10   30.83       0   30.83       0   28.93     2.7   28.93     3.2   30.53
    13.2   30.53
#Mann= 3 , 0 , 0
     -10    .033       0       0    .033       0     3.2    .033       0
#XS Ineff= 2 , 0
               0   30.83     3.2           30.53
Permanent Ineff=
       F       F
Bank Sta=0,3.2
XS Rating Curve= 0
Exp/Cntr=.3,.1

Type RM Length L Ch R = 1 ,300.00  ,50,50,50
BEGIN DESCRIPTION:
6
END DESCRIPTION:
#Sta/Elev= 10
     -10   30.27       0   30.27       0   28.37     2.6   28.37       3   29.92
     3.5   29.92       5   29.42       6   29.42       7   28.52      17   28.52
#Mann= 3 , 0 , 0
     -10    .033       0       0    .033       0       3    .033       0
#XS Ineff= 2 , 0
               0   30.27       3           29.92
Permanent Ineff=
       F       F
Bank Sta=0,3
XS Rating Curve= 0
Exp/Cntr=.3,.1

Type RM Length L Ch R = 1 ,250.00  ,36,36,36
BEGIN DESCRIPTION:
5
END DESCRIPTION:
#Sta/Elev= 10
     -10   28.69       0   28.69       0   26.99     2.6   26.99       3   28.39
     3.5   28.39       5   27.89       6   27.89       7   26.99      17   26.99
#Mann= 3 , 0 , 0
     -10    .033       0       0    .033       0       3    .033       0
#XS Ineff= 2 , 0
               0   28.69       3           28.39
Permanent Ineff=
       F       F
Bank Sta=0,3
XS Rating Curve= 0
Exp/Cntr=.3,.1

Type RM Length L Ch R = 1 ,214.00  ,1,1,1
BEGIN DESCRIPTION:
4.014
END DESCRIPTION:
#Sta/Elev= 6
     -10   27.39       0   27.39       0   25.69       3   25.69       3   27.39
      13   27.39
#Mann= 3 , 0 , 0
     -10    .033       0       0    .033       0       3    .033       0
#XS Ineff= 2 , 0
               0   27.39       3           27.39
Permanent Ineff=
       F       F
Bank Sta=0,3
XS Rating Curve= 0
Exp/Cntr=.3,.1

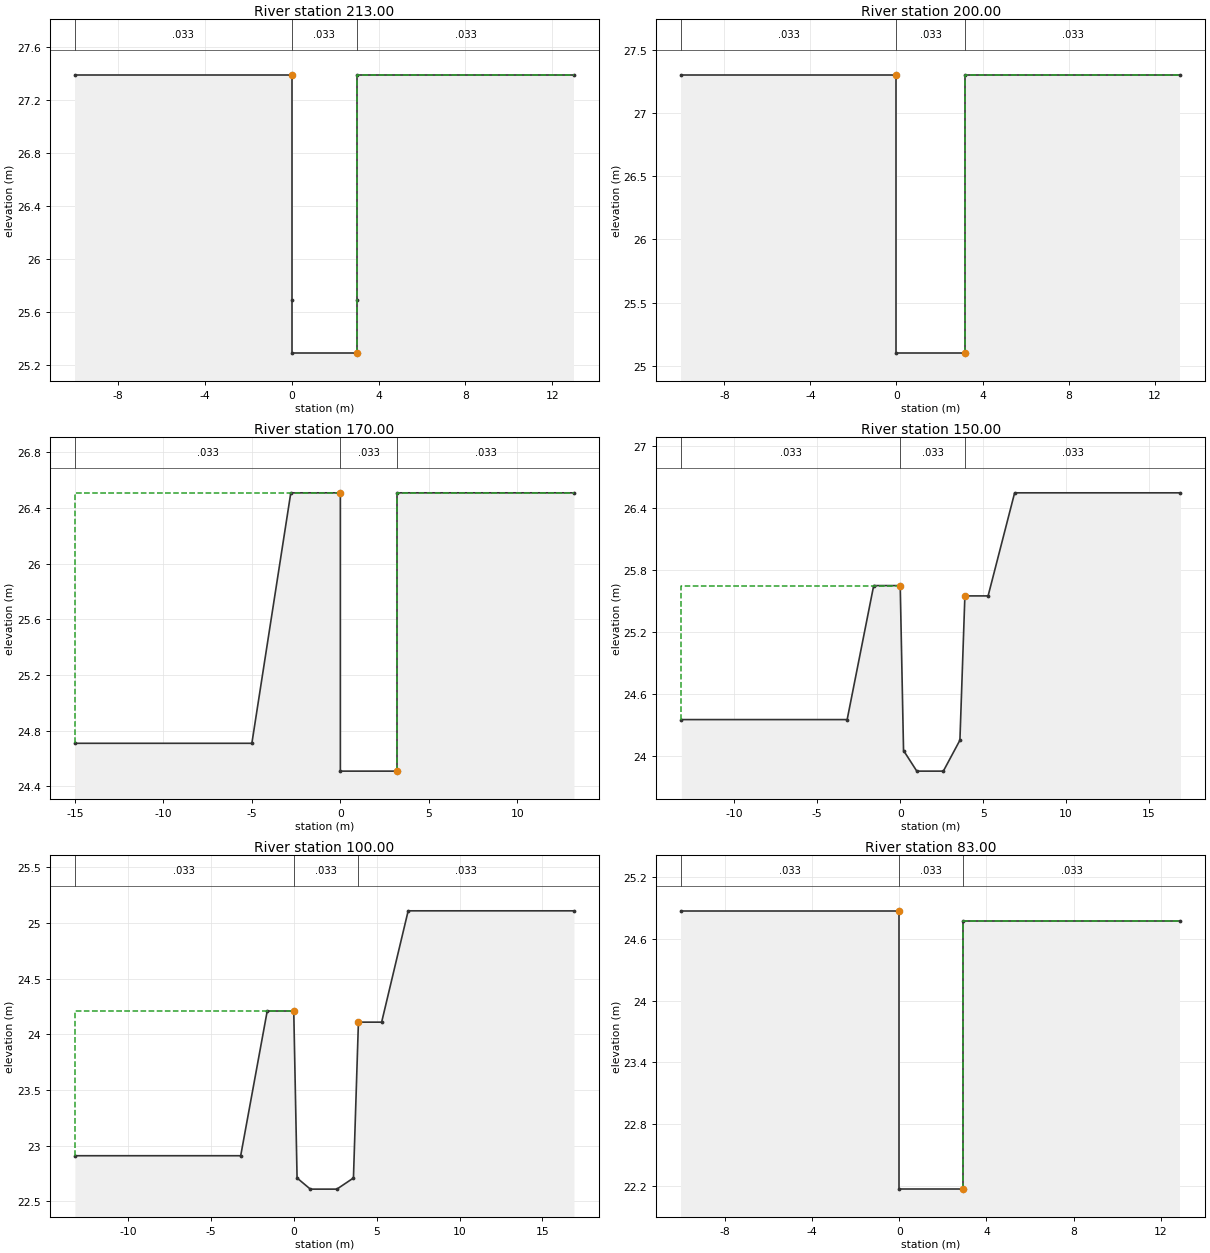
Type RM Length L Ch R = 1 ,213.00  ,13,13,13
BEGIN DESCRIPTION:
4.013
END DESCRIPTION:
#Sta/Elev= 8
     -10   27.39       0   27.39       0   25.69       0   25.29       3   25.29
       3   25.69       3   27.39      13   27.39
#Mann= 3 , 0 , 0
     -10    .033       0       0    .033       0       3    .033       0
#XS Ineff= 2 , 0
               0   27.39       3           27.39
Permanent Ineff=
       F       F
Bank Sta=0,3
XS Rating Curve= 0
Exp/Cntr=.3,.1

Type RM Length L Ch R = 1 ,200.00  ,30,30,30
BEGIN DESCRIPTION:
4
END DESCRIPTION:
#Sta/Elev= 6
     -10    27.3       0    27.3       0    25.1     3.2    25.1     3.2    27.3
    13.2    27.3
#Mann= 3 , 0 , 0
     -10    .033       0       0    .033       0     3.2    .033       0
#XS Ineff= 2 , 0
               0    27.3     3.2            27.3
Permanent Ineff=
       F       F
Bank Sta=0,3.2
XS Rating Curve= 0
Exp/Cntr=.3,.1

Type RM Length L Ch R = 1 ,170.00  ,20,20,20
BEGIN DESCRIPTION:
3.02
END DESCRIPTION:
#Sta/Elev= 8
     -15   24.71      -5   24.71    -2.8   26.51       0   26.51       0   24.51
     3.2   24.51     3.2   26.51    13.2   26.51
#Mann= 3 , 0 , 0
     -15    .033       0       0    .033       0     3.2    .033       0
#XS Ineff= 2 , 0
               0   26.51     3.2           26.51
Permanent Ineff=
       F       F
Bank Sta=0,3.2
XS Rating Curve= 0
Exp/Cntr=.3,.1

Type RM Length L Ch R = 1 ,150.00  ,50,50,50
BEGIN DESCRIPTION:
3
END DESCRIPTION:
#Sta/Elev= 12
   -13.2   24.35    -3.2   24.35    -1.6   25.65       0   25.65      .2   24.05
       1   23.85     2.6   23.85     3.6   24.15     3.9   25.55     5.3   25.55
     6.9   26.55    16.9   26.55
#Mann= 3 , 0 , 0
   -13.2    .033       0       0    .033       0     3.9    .033       0
#XS Ineff= 2 , 0
               0   25.65     3.9           25.55
Permanent Ineff=
       F       F
Bank Sta=0,3.9
XS Rating Curve= 0
Exp/Cntr=.3,.1

Type RM Length L Ch R = 1 ,100.00  ,17,17,17
BEGIN DESCRIPTION:
2
END DESCRIPTION:
#Sta/Elev= 12
   -13.2   22.91    -3.2   22.91    -1.6   24.21       0   24.21      .2   22.71
       1   22.61     2.6   22.61     3.6   22.71     3.9   24.11     5.3   24.11
     6.9   25.11    16.9   25.11
#Mann= 3 , 0 , 0
   -13.2    .033       0       0    .033       0     3.9    .033       0
#XS Ineff= 2 , 0
               0   24.21     3.9           24.11
Permanent Ineff=
       F       F
Bank Sta=0,3.9
XS Rating Curve= 0
Exp/Cntr=.3,.1

Type RM Length L Ch R = 1 ,83.00   ,30,30,30
BEGIN DESCRIPTION:
1.033
END DESCRIPTION:
#Sta/Elev= 6
     -10   24.87       0   24.87       0   22.17     2.9   22.17     2.9   24.77
    12.9   24.77
#Mann= 3 , 0 , 0
     -10    .033       0       0    .033       0     2.9    .033       0
#XS Ineff= 2 , 0
               0   24.87     2.9           24.77
Permanent Ineff=
       F       F
Bank Sta=0,2.9
XS Rating Curve= 0
Exp/Cntr=.3,.1

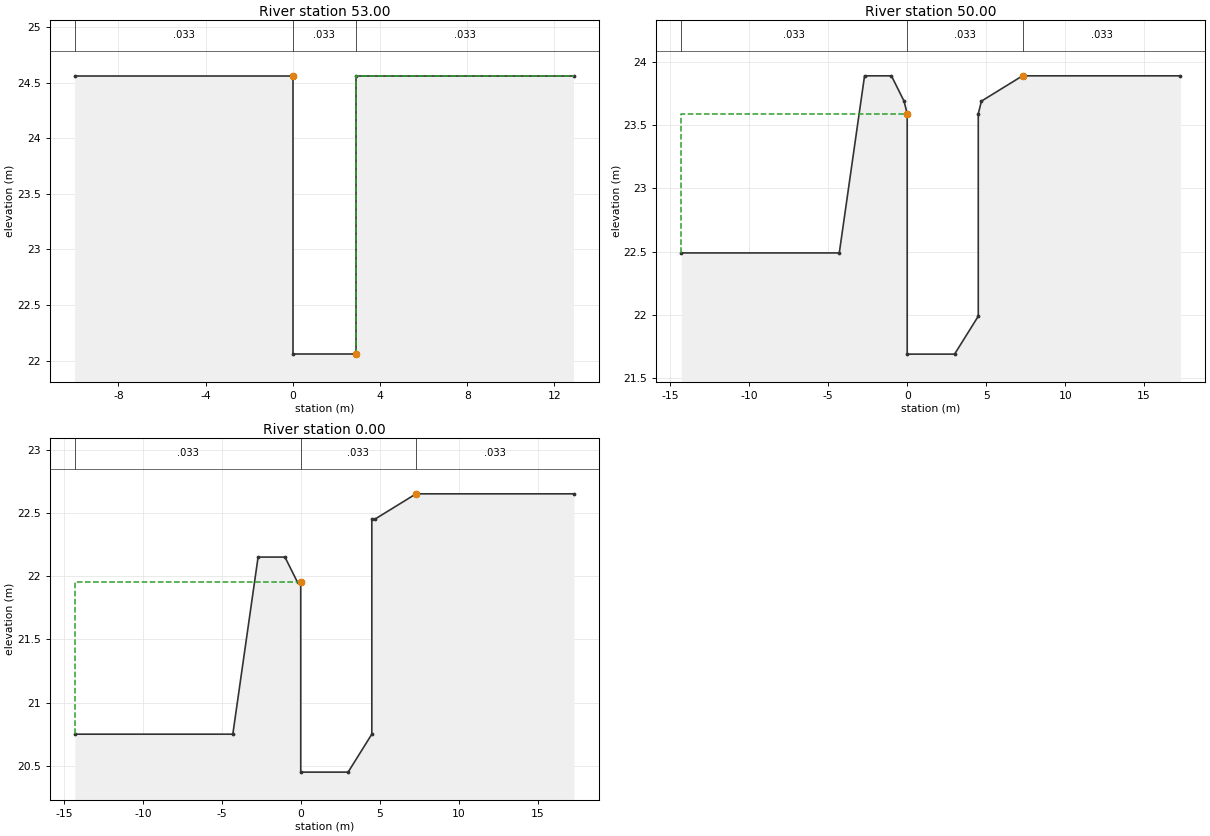
Type RM Length L Ch R = 1 ,53.00   ,3,3,3
BEGIN DESCRIPTION:
1.003
END DESCRIPTION:
#Sta/Elev= 6
     -10   24.56       0   24.56       0   22.06     2.9   22.06     2.9   24.56
    12.9   24.56
#Mann= 3 , 0 , 0
     -10    .033       0       0    .033       0     2.9    .033       0
#XS Ineff= 2 , 0
               0   24.56     2.9           24.56
Permanent Ineff=
       F       F
Bank Sta=0,2.9
XS Rating Curve= 0
Exp/Cntr=.3,.1

Type RM Length L Ch R = 1 ,50.00   ,50,50,50
BEGIN DESCRIPTION:
1
END DESCRIPTION:
#Sta/Elev= 13
   -14.3   22.49    -4.3   22.49    -2.7   23.89      -1   23.89     -.2   23.69
       0   23.59       0   21.69       3   21.69     4.5   21.99     4.5   23.59
     4.7   23.69     7.3   23.89    17.3   23.89
#Mann= 3 , 0 , 0
   -14.3    .033       0       0    .033       0     7.3    .033       0
#XS Ineff= 2 , 0
               0   23.59     7.3           23.89
Permanent Ineff=
       F       F
Bank Sta=0,7.3
XS Rating Curve= 0
Exp/Cntr=.3,.1

Type RM Length L Ch R = 1 ,0.00    ,0,0,0
BEGIN DESCRIPTION:
0
END DESCRIPTION:
#Sta/Elev= 13
   -14.3   20.75    -4.3   20.75    -2.7   22.15      -1   22.15     -.2   21.95
       0   21.95       0   20.45       3   20.45     4.5   20.75     4.5   22.45
     4.7   22.45     7.3   22.65    17.3   22.65
#Mann= 3 , 0 , 0
   -14.3    .033       0       0    .033       0     7.3    .033       0
#XS Ineff= 2 , 0
               0   21.95     7.3           22.65
Permanent Ineff=
       F       F
Bank Sta=0,7.3
XS Rating Curve= 0
Exp/Cntr=.3,.1

Chan Stop Cuts=-1