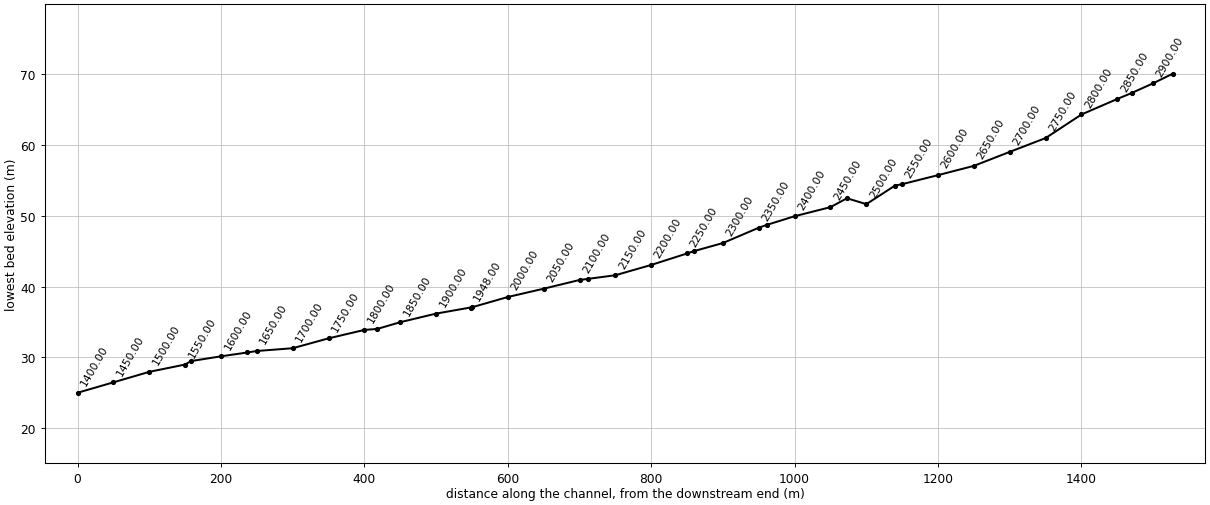
--- OKMA.prj (project) ---

Proj Title=OKMA
Current Plan=p01
Default Exp/Contr=.3,.1
SI Units
Geom File=g01
Flow File=f01
Plan File=p01
Y Axis Title=Elevation
X Axis Title(PF)=Main Channel Distance
X Axis Title(XS)=Station
BEGIN DESCRIPTION:
           BACK WATER COMPUTATION
      APPLICATION OF HEC-2 BY Samju Construction Engineering
      OKMA-STREEM : 30 YR
END DESCRIPTION:
DSS Export Rating Curves= 0
DSS Export Rating Curve Sorted= 0
DSS Export Volume Flow Curves= 0
DXF OffsetX= 0
DXF OffsetY= 0
DXF ScaleX= 1
DXF ScaleY= 10

--- OKMA.p01 (plan) ---

Plan Title=Imported Plan 01
Version=Version 3.0.1  Mar 2001
Short Identifier=Imported Pla
Geom File=g01
Flow File=f01
Subcritical Flow
K Sum by GR= 0
Std Step Tol= 0.003
Critical Tol= 0.003
Num of Std Step Trials= 20
Max Error Tol= 0.1
Flow Tol Ratio= 0.001
Split Flow NTrial= 30
Split Flow Tol= 0.02
Split Flow Ratio= 0.02
Log Output Level= 0
Friction Slope Method= 1
Unsteady Friction Slope Method= 2
Parabolic Critical Depth
Global Vel Dist= 0 , 0 , 0
Global Log Level= 0
CheckData=True
Encroach Param=-1 ,0,0, 0
Computation Interval=1HOUR
Output Interval=1HOUR
Run HTab= 0
Run UNet= 0
Run PostProcess= 0
UNET Theta= 1
UNET ZTol= 0.02
UNET ZSATol= 0.1
UNET MxIter= 20
UNET MaxInSteps= 20
UNET DtIC= 0
UNET DtMin= 0
UNET MaxCRTS= 20
UNET WFStab= 2
UNET SFStab= 1
UNET WFX= 1
UNET SFX= 1
UNET Convert EG Bridges=-1
UNET Use Existing IB Tables=-1
Instantaneous Interval=1HOUR
Write IC File= 0
Write Velocity= 0
Write Detailed= 0

--- OKMA.f01 (steady flow) ---

Flow Title=Imported Flow 01
Version=Version 3.0.1  Mar 2001
Number of Profiles= 5
Profile Names=10YR,20YR,30YR,50YR,80YR
River Rch & RM=RIVER-1,Reach-1         ,58.027
   16.24    17.9   18.87   20.09   21.21
River Rch & RM=RIVER-1,Reach-1         ,16.026
   18.87    20.8   21.93   23.36   24.67
River Rch & RM=OKMA,OKMA            ,2927.00
   16.24    17.9   18.87   20.09   21.21
River Rch & RM=OKMA,OKMA            ,826.00
   18.87    20.8   21.93   23.36   24.67
Boundary for River Rch & Prof#=OKMA,OKMA            , 1
Up Type= 0
Dn Type= 3
Dn Slope=.022
Boundary for River Rch & Prof#=OKMA,OKMA            , 2
Up Type= 0
Dn Type= 3
Dn Slope=.022
Boundary for River Rch & Prof#=OKMA,OKMA            , 3
Up Type= 0
Dn Type= 3
Dn Slope=.022
Boundary for River Rch & Prof#=OKMA,OKMA            , 4
Up Type= 0
Dn Type= 3
Dn Slope=.022
Boundary for River Rch & Prof#=OKMA,OKMA            , 5
Up Type= 0
Dn Type= 3
Dn Slope=.022
DSS Import GetInterval= 0
DSS Import GetPeak= 0
DSS Import FillOption= 0

--- OKMA.g01 (geometry) ---

Geom Title=Imported Geom 01
Version=Version 3.0.1  Mar 2001

River Reach=OKMA            ,OKMA
Reach XY= 2
              .5             .95              .5             .05

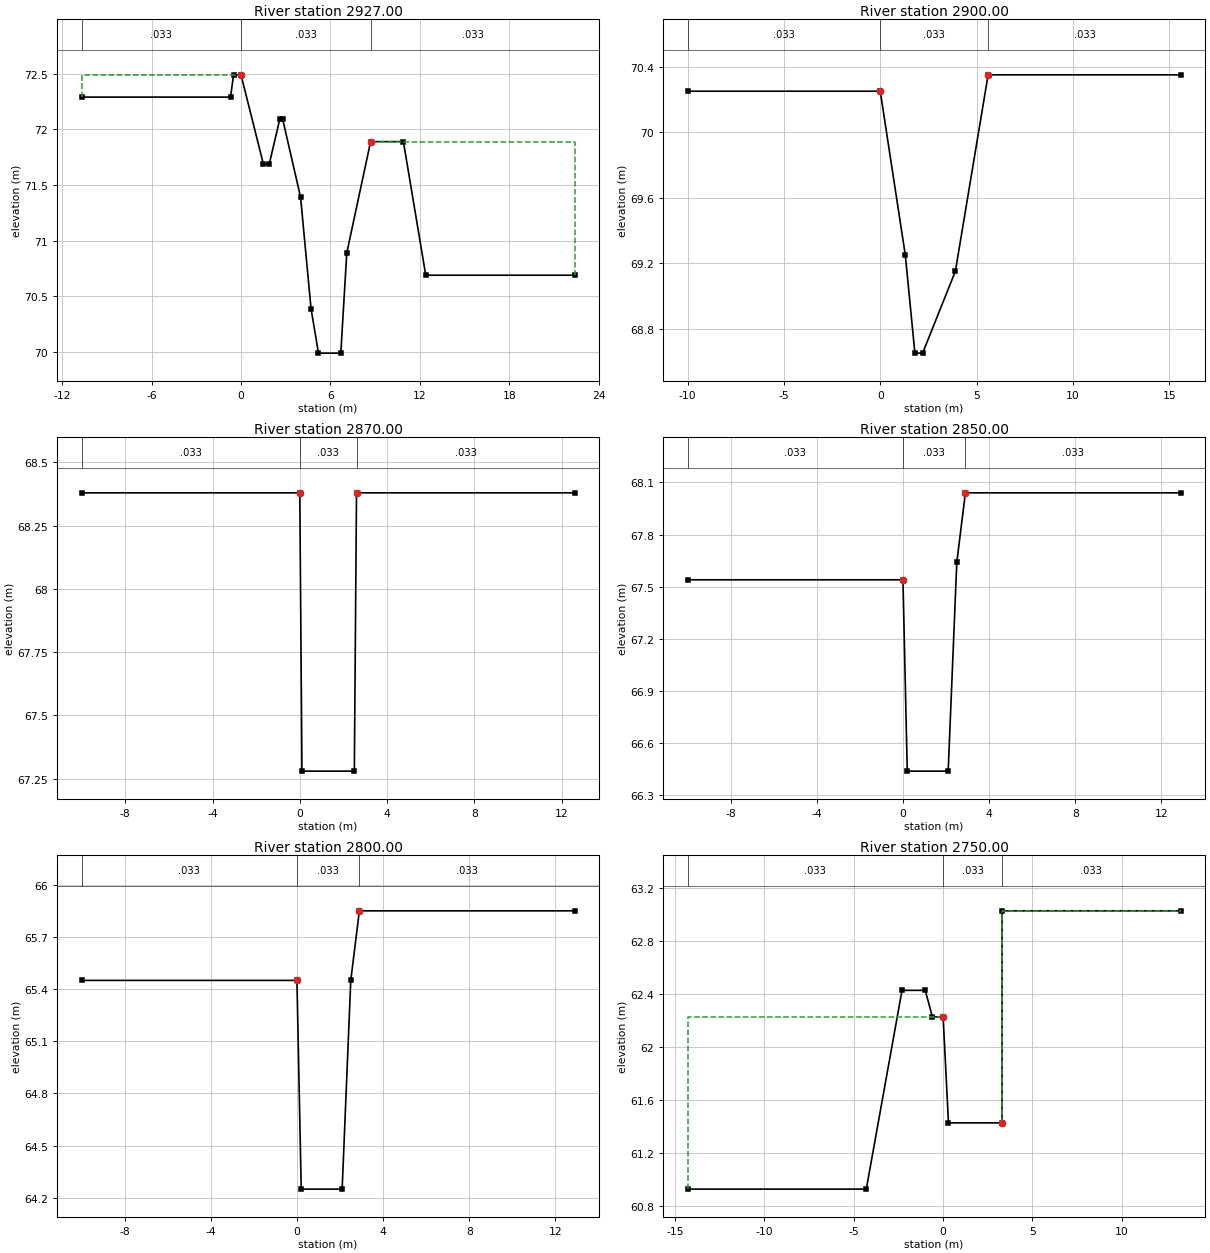
Type RM Length L Ch R = 1 ,2927.00 ,27,27,27
BEGIN DESCRIPTION:
58.027
END DESCRIPTION:
#Sta/Elev= 17
   -10.7   72.29     -.7   72.29     -.5   72.49       0   72.49     1.5   71.69
     1.9   71.69     2.6   72.09     2.8   72.09       4   71.39     4.7   70.39
     5.2   69.99     6.7   69.99     7.1   70.89     8.7   71.89    10.9   71.89
    12.4   70.69    22.4   70.69
#Mann= 3 , 0 , 0
   -10.7    .033       0       0    .033       0     8.7    .033       0
#XS Ineff= 2 , 0
               0   72.49     8.7           71.89
Permanent Ineff=
       F       F
Bank Sta=0,8.7
XS Rating Curve= 0
Exp/Cntr=.3,.1

Type RM Length L Ch R = 1 ,2900.00 ,30,30,30
BEGIN DESCRIPTION:
58
END DESCRIPTION:
#Sta/Elev= 8
     -10   70.25       0   70.25     1.3   69.25     1.8   68.65     2.2   68.65
     3.9   69.15     5.6   70.35    15.6   70.35
#Mann= 3 , 0 , 0
     -10    .033       0       0    .033       0     5.6    .033       0
#XS Ineff= 2 , 0
               0   70.25     5.6           70.35
Permanent Ineff=
       F       F
Bank Sta=0,5.6
XS Rating Curve= 0
Exp/Cntr=.3,.1

Type RM Length L Ch R = 1 ,2870.00 ,20,20,20
BEGIN DESCRIPTION:
57.02
END DESCRIPTION:
#Sta/Elev= 6
     -10   68.38       0   68.38      .1   67.28     2.5   67.28     2.6   68.38
    12.6   68.38
#Mann= 3 , 0 , 0
     -10    .033       0       0    .033       0     2.6    .033       0
#XS Ineff= 2 , 0
               0   68.38     2.6           68.38
Permanent Ineff=
       F       F
Bank Sta=0,2.6
XS Rating Curve= 0
Exp/Cntr=.3,.1

Type RM Length L Ch R = 1 ,2850.00 ,50,50,50
BEGIN DESCRIPTION:
57
END DESCRIPTION:
#Sta/Elev= 7
     -10   67.54       0   67.54      .2   66.44     2.1   66.44     2.5   67.64
     2.9   68.04    12.9   68.04
#Mann= 3 , 0 , 0
     -10    .033       0       0    .033       0     2.9    .033       0
#XS Ineff= 2 , 0
               0   67.54     2.9           68.04
Permanent Ineff=
       F       F
Bank Sta=0,2.9
XS Rating Curve= 0
Exp/Cntr=.3,.1

Type RM Length L Ch R = 1 ,2800.00 ,50,50,50
BEGIN DESCRIPTION:
56
END DESCRIPTION:
#Sta/Elev= 7
     -10   65.45       0   65.45      .2   64.25     2.1   64.25     2.5   65.45
     2.9   65.85    12.9   65.85
#Mann= 3 , 0 , 0
     -10    .033       0       0    .033       0     2.9    .033       0
#XS Ineff= 2 , 0
               0   65.45     2.9           65.85
Permanent Ineff=
       F       F
Bank Sta=0,2.9
XS Rating Curve= 0
Exp/Cntr=.3,.1

Type RM Length L Ch R = 1 ,2750.00 ,50,50,50
BEGIN DESCRIPTION:
55
END DESCRIPTION:
#Sta/Elev= 10
   -14.3   60.93    -4.3   60.93    -2.3   62.43      -1   62.43     -.6   62.23
       0   62.23      .3   61.43     3.3   61.43     3.3   63.03    13.3   63.03
#Mann= 3 , 0 , 0
   -14.3    .033       0       0    .033       0     3.3    .033       0
#XS Ineff= 2 , 0
               0   62.23     3.3           63.03
Permanent Ineff=
       F       F
Bank Sta=0,3.3
XS Rating Curve= 0
Exp/Cntr=.3,.1

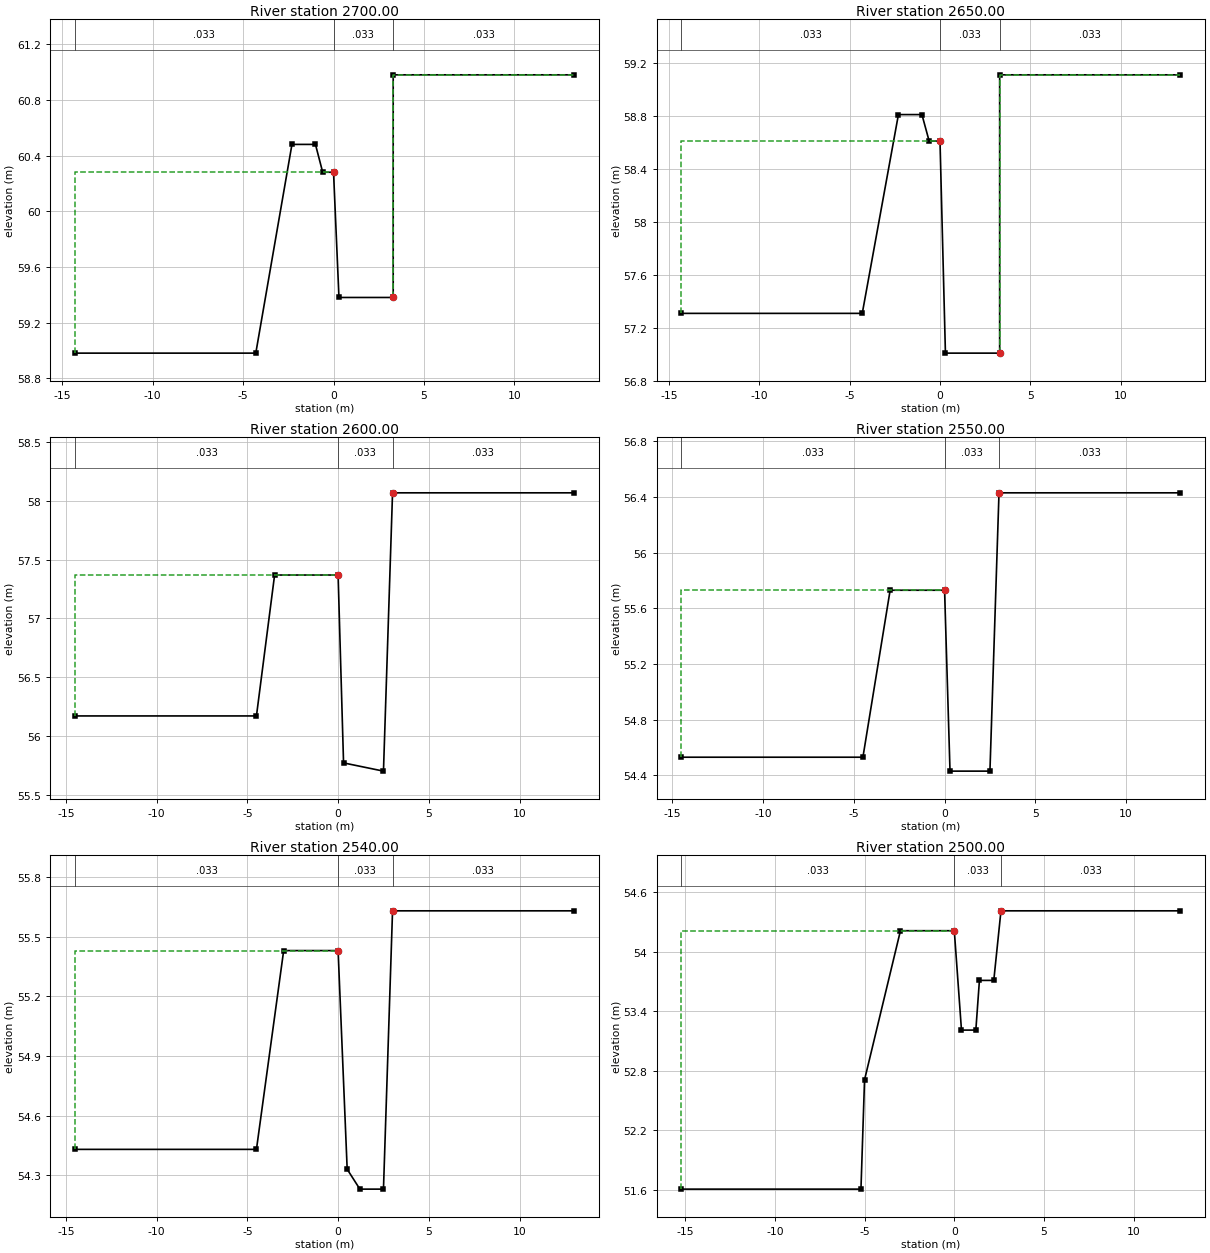
Type RM Length L Ch R = 1 ,2700.00 ,50,50,50
BEGIN DESCRIPTION:
54
END DESCRIPTION:
#Sta/Elev= 10
   -14.3   58.98    -4.3   58.98    -2.3   60.48      -1   60.48     -.6   60.28
       0   60.28      .3   59.38     3.3   59.38     3.3   60.98    13.3   60.98
#Mann= 3 , 0 , 0
   -14.3    .033       0       0    .033       0     3.3    .033       0
#XS Ineff= 2 , 0
               0   60.28     3.3           60.98
Permanent Ineff=
       F       F
Bank Sta=0,3.3
XS Rating Curve= 0
Exp/Cntr=.3,.1

Type RM Length L Ch R = 1 ,2650.00 ,50,50,50
BEGIN DESCRIPTION:
53
END DESCRIPTION:
#Sta/Elev= 10
   -14.3   57.31    -4.3   57.31    -2.3   58.81      -1   58.81     -.6   58.61
       0   58.61      .3   57.01     3.3   57.01     3.3   59.11    13.3   59.11
#Mann= 3 , 0 , 0
   -14.3    .033       0       0    .033       0     3.3    .033       0
#XS Ineff= 2 , 0
               0   58.61     3.3           59.11
Permanent Ineff=
       F       F
Bank Sta=0,3.3
XS Rating Curve= 0
Exp/Cntr=.3,.1

Type RM Length L Ch R = 1 ,2600.00 ,50,50,50
BEGIN DESCRIPTION:
52
END DESCRIPTION:
#Sta/Elev= 8
   -14.5   56.17    -4.5   56.17    -3.5   57.37       0   57.37      .3   55.77
     2.5    55.7       3   58.07      13   58.07
#Mann= 3 , 0 , 0
   -14.5    .033       0       0    .033       0       3    .033       0
#XS Ineff= 2 , 0
               0   57.37       3           58.07
Permanent Ineff=
       F       F
Bank Sta=0,3
XS Rating Curve= 0
Exp/Cntr=.3,.1

Type RM Length L Ch R = 1 ,2550.00 ,10,10,10
BEGIN DESCRIPTION:
51
END DESCRIPTION:
#Sta/Elev= 8
   -14.5   54.53    -4.5   54.53      -3   55.73       0   55.73      .3   54.43
     2.5   54.43       3   56.43      13   56.43
#Mann= 3 , 0 , 0
   -14.5    .033       0       0    .033       0       3    .033       0
#XS Ineff= 2 , 0
               0   55.73       3           56.43
Permanent Ineff=
       F       F
Bank Sta=0,3
XS Rating Curve= 0
Exp/Cntr=.3,.1

Type RM Length L Ch R = 1 ,2540.00 ,40,40,40
BEGIN DESCRIPTION:
50.04
END DESCRIPTION:
#Sta/Elev= 9
   -14.5   54.43    -4.5   54.43      -3   55.43       0   55.43      .5   54.33
     1.2   54.23     2.5   54.23       3   55.63      13   55.63
#Mann= 3 , 0 , 0
   -14.5    .033       0       0    .033       0       3    .033       0
#XS Ineff= 2 , 0
               0   55.43       3           55.63
Permanent Ineff=
       F       F
Bank Sta=0,3
XS Rating Curve= 0
Exp/Cntr=.3,.1

Type RM Length L Ch R = 1 ,2500.00 ,27,27,27
BEGIN DESCRIPTION:
50
END DESCRIPTION:
#Sta/Elev= 11
   -15.2   51.61    -5.2   51.61      -5   52.71      -3   54.21       0   54.21
      .4   53.21     1.2   53.21     1.4   53.71     2.2   53.71     2.6   54.41
    12.6   54.41
#Mann= 3 , 0 , 0
   -15.2    .033       0       0    .033       0     2.6    .033       0
#XS Ineff= 2 , 0
               0   54.21     2.6           54.41
Permanent Ineff=
       F       F
Bank Sta=0,2.6
XS Rating Curve= 0
Exp/Cntr=.3,.1

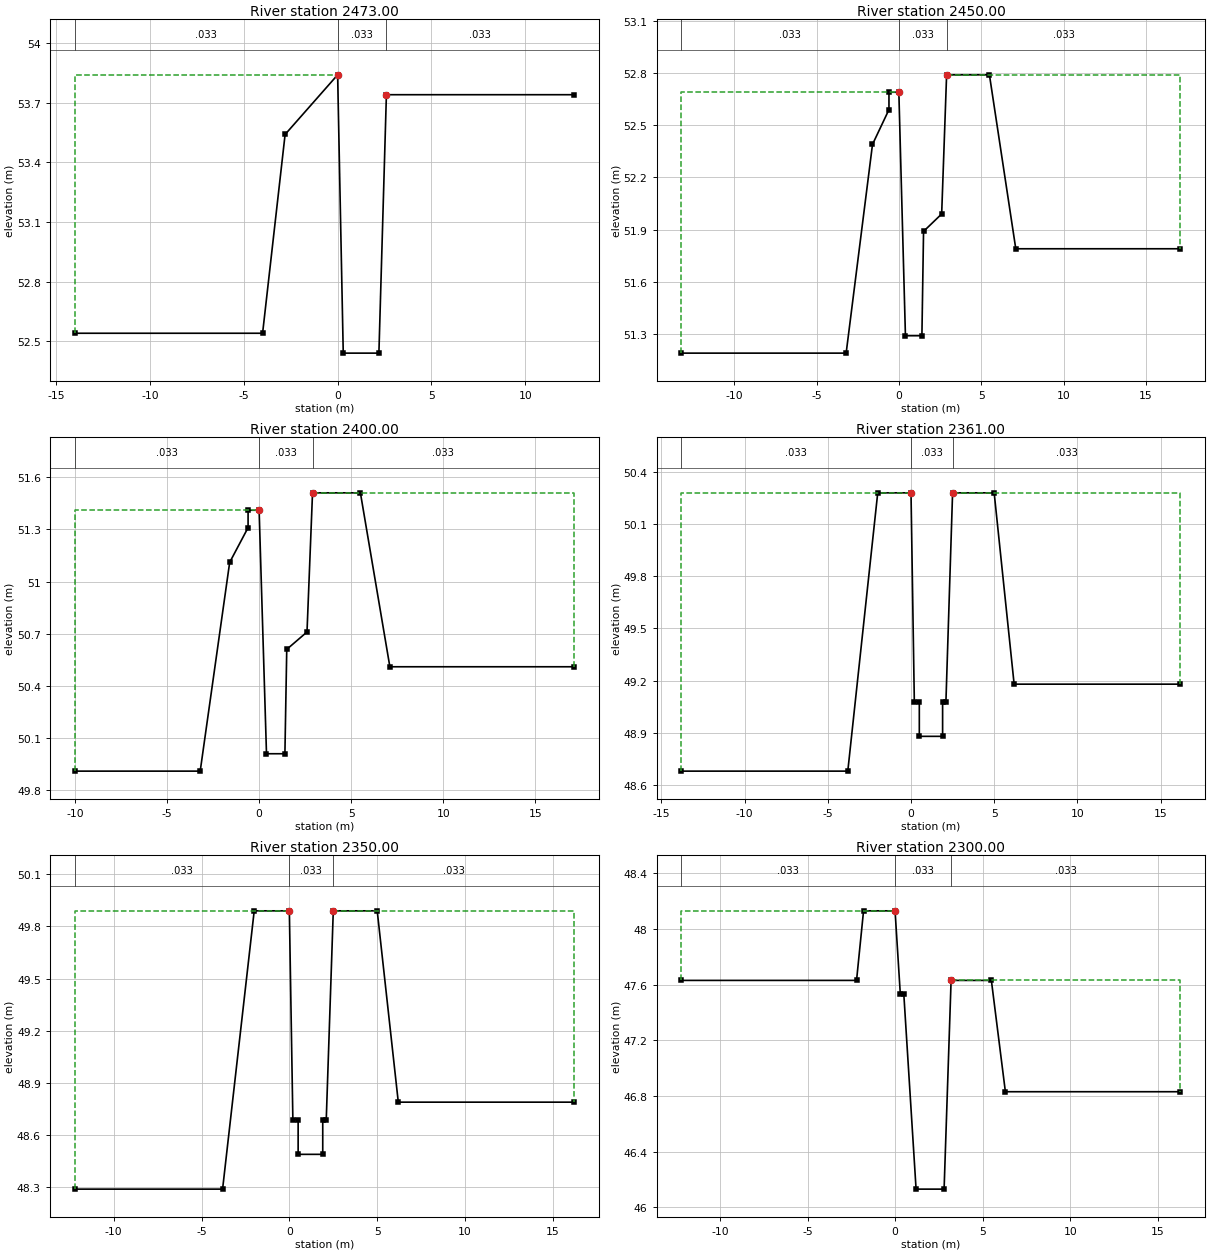
Type RM Length L Ch R = 1 ,2473.00 ,23,23,23
BEGIN DESCRIPTION:
49.023
END DESCRIPTION:
#Sta/Elev= 8
     -14   52.54      -4   52.54    -2.8   53.54       0   53.84      .3   52.44
     2.2   52.44     2.6   53.74    12.6   53.74
#Mann= 3 , 0 , 0
     -14    .033       0       0    .033       0     2.6    .033       0
#XS Ineff= 2 , 0
               0   53.84     2.6           53.74
Permanent Ineff=
       F       F
Bank Sta=0,2.6
XS Rating Curve= 0
Exp/Cntr=.3,.1

Type RM Length L Ch R = 1 ,2450.00 ,50,50,50
BEGIN DESCRIPTION:
49
END DESCRIPTION:
#Sta/Elev= 14
   -13.2   51.19    -3.2   51.19    -1.6   52.39     -.6   52.59     -.6   52.69
       0   52.69      .4   51.29     1.4   51.29     1.5   51.89     2.6   51.99
     2.9   52.79     5.5   52.79     7.1   51.79    17.1   51.79
#Mann= 3 , 0 , 0
   -13.2    .033       0       0    .033       0     2.9    .033       0
#XS Ineff= 2 , 0
               0   52.69     2.9           52.79
Permanent Ineff=
       F       F
Bank Sta=0,2.9
XS Rating Curve= 0
Exp/Cntr=.3,.1

Type RM Length L Ch R = 1 ,2400.00 ,39,39,39
BEGIN DESCRIPTION:
48
END DESCRIPTION:
#Sta/Elev= 14
     -10   49.91    -3.2   49.91    -1.6   51.11     -.6   51.31     -.6   51.41
       0   51.41      .4   50.01     1.4   50.01     1.5   50.61     2.6   50.71
     2.9   51.51     5.5   51.51     7.1   50.51    17.1   50.51
#Mann= 3 , 0 , 0
     -10    .033       0       0    .033       0     2.9    .033       0
#XS Ineff= 2 , 0
               0   51.41     2.9           51.51
Permanent Ineff=
       F       F
Bank Sta=0,2.9
XS Rating Curve= 0
Exp/Cntr=.3,.1

Type RM Length L Ch R = 1 ,2361.00 ,11,11,11
BEGIN DESCRIPTION:
47.011
END DESCRIPTION:
#Sta/Elev= 14
   -13.8   48.68    -3.8   48.68      -2   50.28       0   50.28      .2   49.08
      .5   49.08      .5   48.88     1.9   48.88     1.9   49.08     2.1   49.08
     2.5   50.28       5   50.28     6.2   49.18    16.2   49.18
#Mann= 3 , 0 , 0
   -13.8    .033       0       0    .033       0     2.5    .033       0
#XS Ineff= 2 , 0
               0   50.28     2.5           50.28
Permanent Ineff=
       F       F
Bank Sta=0,2.5
XS Rating Curve= 0
Exp/Cntr=.3,.1

Type RM Length L Ch R = 1 ,2350.00 ,50,50,50
BEGIN DESCRIPTION:
47
END DESCRIPTION:
#Sta/Elev= 14
   -12.2   48.29    -3.8   48.29      -2   49.89       0   49.89      .2   48.69
      .5   48.69      .5   48.49     1.9   48.49     1.9   48.69     2.1   48.69
     2.5   49.89       5   49.89     6.2   48.79    16.2   48.79
#Mann= 3 , 0 , 0
   -12.2    .033       0       0    .033       0     2.5    .033       0
#XS Ineff= 2 , 0
               0   49.89     2.5           49.89
Permanent Ineff=
       F       F
Bank Sta=0,2.5
XS Rating Curve= 0
Exp/Cntr=.3,.1

Type RM Length L Ch R = 1 ,2300.00 ,40,40,40
BEGIN DESCRIPTION:
46
END DESCRIPTION:
#Sta/Elev= 12
   -12.2   47.63    -2.2   47.63    -1.8   48.13       0   48.13      .3   47.53
      .5   47.53     1.2   46.13     2.8   46.13     3.2   47.63     5.5   47.63
     6.3   46.83    16.3   46.83
#Mann= 3 , 0 , 0
   -12.2    .033       0       0    .033       0     3.2    .033       0
#XS Ineff= 2 , 0
               0   48.13     3.2           47.63
Permanent Ineff=
       F       F
Bank Sta=0,3.2
XS Rating Curve= 0
Exp/Cntr=.3,.1

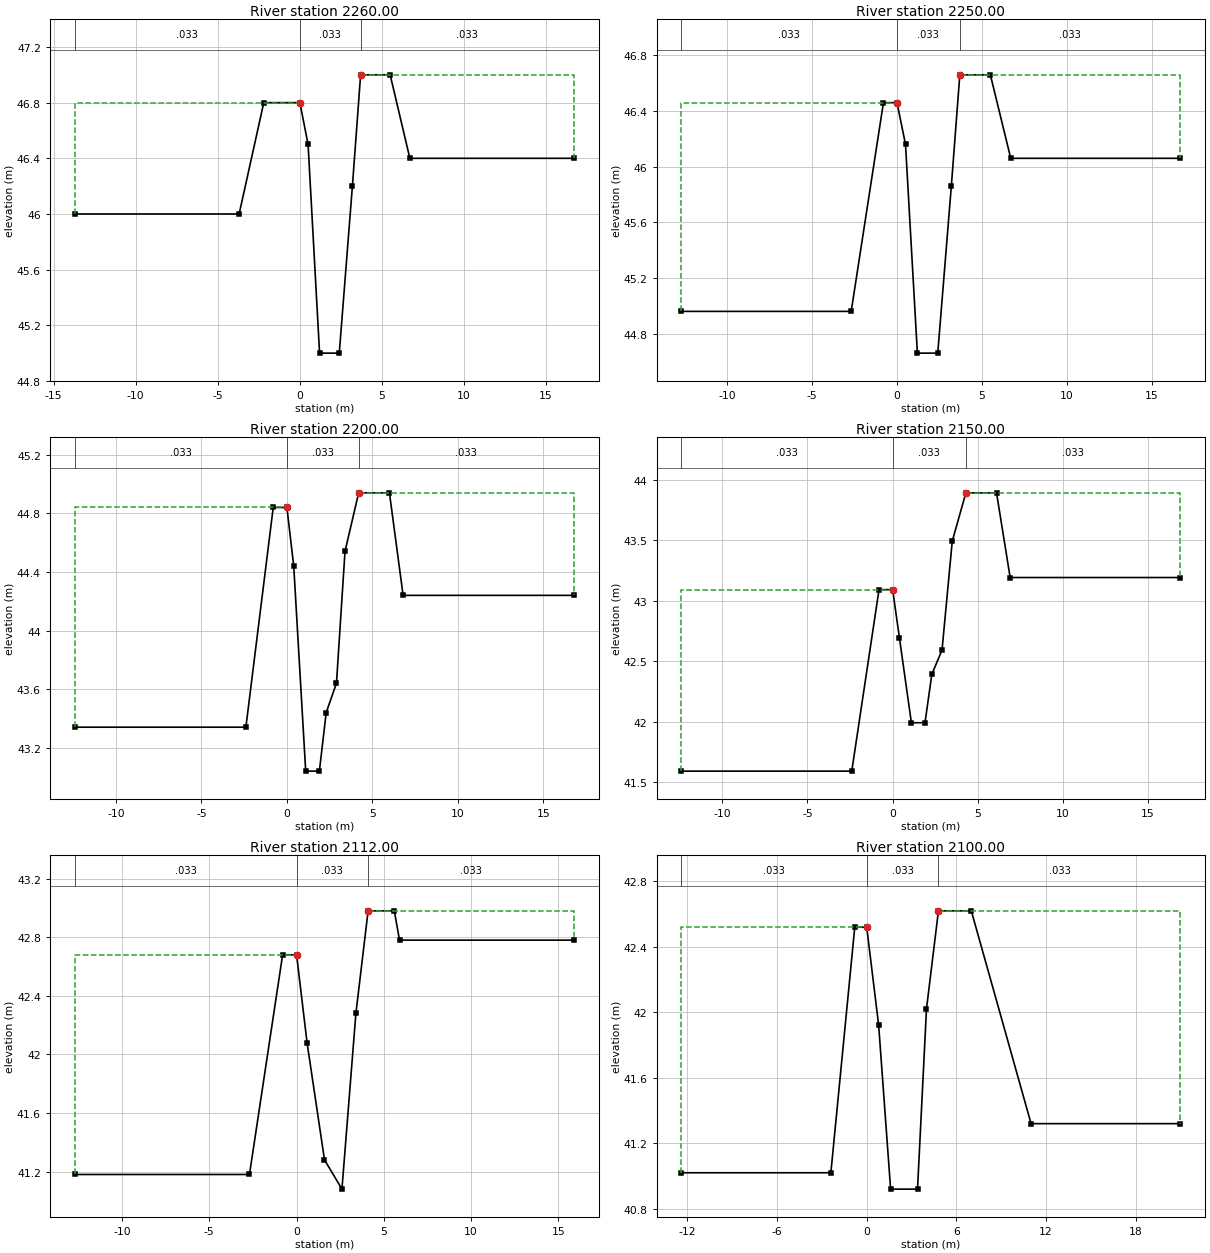
Type RM Length L Ch R = 1 ,2260.00 ,10,10,10
BEGIN DESCRIPTION:
45.01
END DESCRIPTION:
#Sta/Elev= 12
   -13.7      46    -3.7      46    -2.2    46.8       0    46.8      .5    46.5
     1.2      45     2.4      45     3.2    46.2     3.7      47     5.5      47
     6.7    46.4    16.7    46.4
#Mann= 3 , 0 , 0
   -13.7    .033       0       0    .033       0     3.7    .033       0
#XS Ineff= 2 , 0
               0    46.8     3.7              47
Permanent Ineff=
       F       F
Bank Sta=0,3.7
XS Rating Curve= 0
Exp/Cntr=.3,.1

Type RM Length L Ch R = 1 ,2250.00 ,50,50,50
BEGIN DESCRIPTION:
45
END DESCRIPTION:
#Sta/Elev= 12
   -12.7   44.96    -2.7   44.96     -.8   46.46       0   46.46      .5   46.16
     1.2   44.66     2.4   44.66     3.2   45.86     3.7   46.66     5.5   46.66
     6.7   46.06    16.7   46.06
#Mann= 3 , 0 , 0
   -12.7    .033       0       0    .033       0     3.7    .033       0
#XS Ineff= 2 , 0
               0   46.46     3.7           46.66
Permanent Ineff=
       F       F
Bank Sta=0,3.7
XS Rating Curve= 0
Exp/Cntr=.3,.1

Type RM Length L Ch R = 1 ,2200.00 ,50,50,50
BEGIN DESCRIPTION:
44
END DESCRIPTION:
#Sta/Elev= 14
   -12.4   43.34    -2.4   43.34     -.8   44.84       0   44.84      .4   44.44
     1.1   43.04     1.9   43.04     2.3   43.44     2.9   43.64     3.4   44.54
     4.2   44.94       6   44.94     6.8   44.24    16.8   44.24
#Mann= 3 , 0 , 0
   -12.4    .033       0       0    .033       0     4.2    .033       0
#XS Ineff= 2 , 0
               0   44.84     4.2           44.94
Permanent Ineff=
       F       F
Bank Sta=0,4.2
XS Rating Curve= 0
Exp/Cntr=.3,.1

Type RM Length L Ch R = 1 ,2150.00 ,38,38,38
BEGIN DESCRIPTION:
43
END DESCRIPTION:
#Sta/Elev= 14
   -12.4   41.59    -2.4   41.59     -.8   43.09       0   43.09      .4   42.69
     1.1   41.99     1.9   41.99     2.3   42.39     2.9   42.59     3.5   43.49
     4.3   43.89     6.1   43.89     6.9   43.19    16.9   43.19
#Mann= 3 , 0 , 0
   -12.4    .033       0       0    .033       0     4.3    .033       0
#XS Ineff= 2 , 0
               0   43.09     4.3           43.89
Permanent Ineff=
       F       F
Bank Sta=0,4.3
XS Rating Curve= 0
Exp/Cntr=.3,.1

Type RM Length L Ch R = 1 ,2112.00 ,12,12,12
BEGIN DESCRIPTION:
42.012
END DESCRIPTION:
#Sta/Elev= 12
   -12.7   41.18    -2.7   41.18     -.8   42.68       0   42.68      .6   42.08
     1.6   41.28     2.6   41.08     3.4   42.28     4.1   42.98     5.6   42.98
     5.9   42.78    15.9   42.78
#Mann= 3 , 0 , 0
   -12.7    .033       0       0    .033       0     4.1    .033       0
#XS Ineff= 2 , 0
               0   42.68     4.1           42.98
Permanent Ineff=
       F       F
Bank Sta=0,4.1
XS Rating Curve= 0
Exp/Cntr=.3,.1

Type RM Length L Ch R = 1 ,2100.00 ,50,50,50
BEGIN DESCRIPTION:
42
END DESCRIPTION:
#Sta/Elev= 12
   -12.4   41.02    -2.4   41.02     -.8   42.52       0   42.52      .8   41.92
     1.6   40.92     3.4   40.92       4   42.02     4.8   42.62       7   42.62
      11   41.32      21   41.32
#Mann= 3 , 0 , 0
   -12.4    .033       0       0    .033       0     4.8    .033       0
#XS Ineff= 2 , 0
               0   42.52     4.8           42.62
Permanent Ineff=
       F       F
Bank Sta=0,4.8
XS Rating Curve= 0
Exp/Cntr=.3,.1

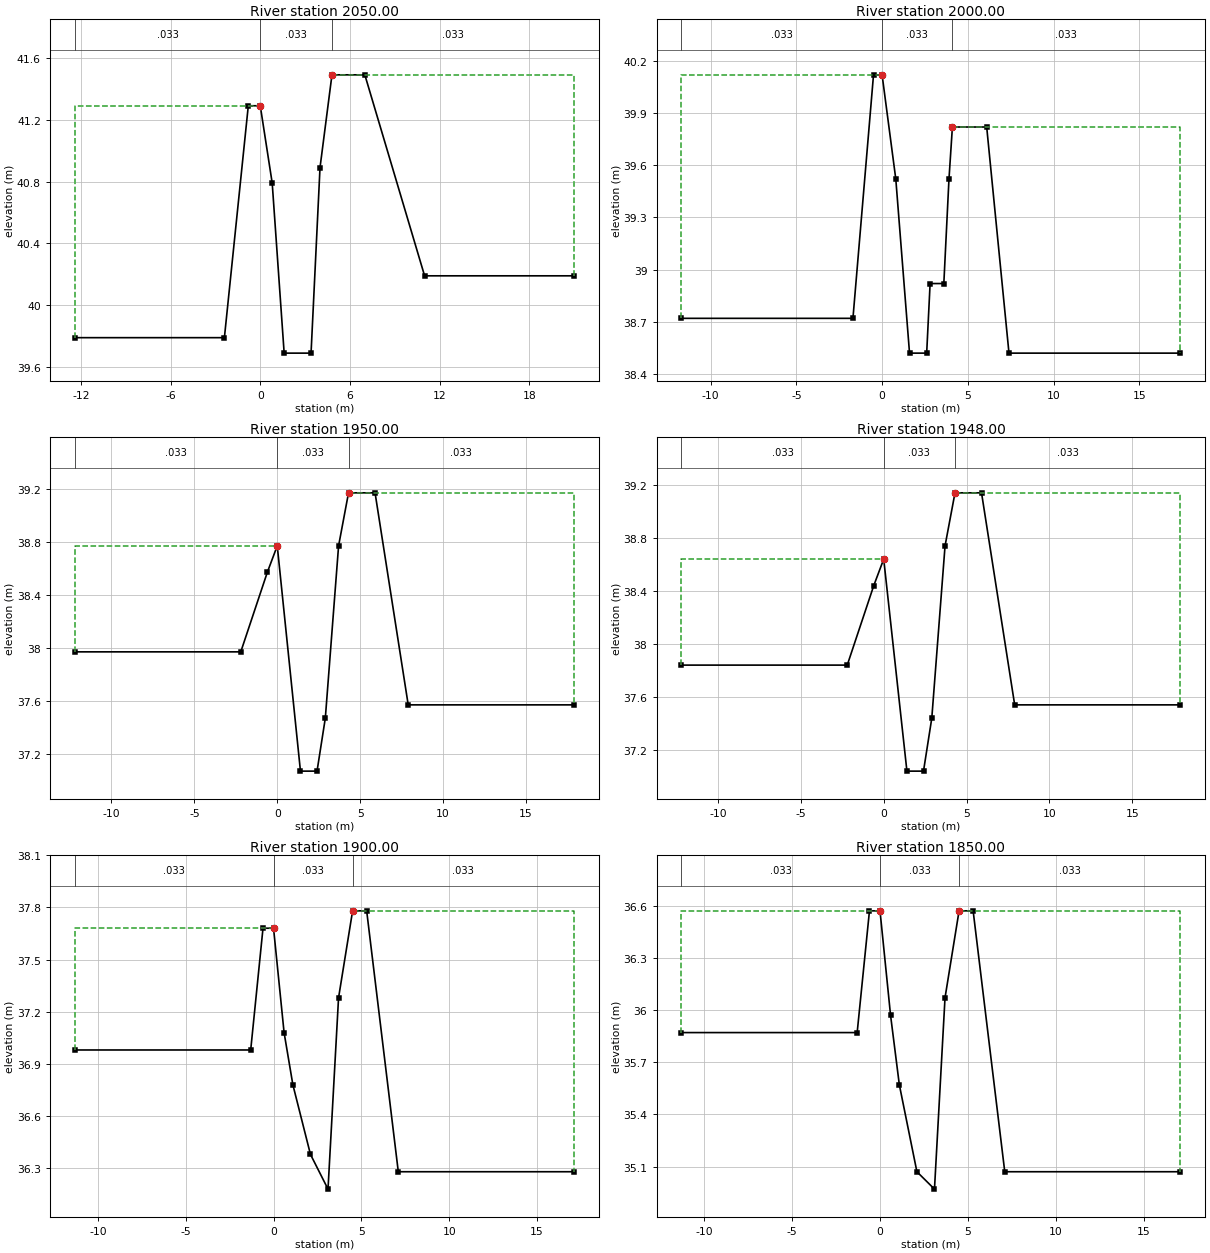
Type RM Length L Ch R = 1 ,2050.00 ,50,50,50
BEGIN DESCRIPTION:
41
END DESCRIPTION:
#Sta/Elev= 12
   -12.4   39.79    -2.4   39.79     -.8   41.29       0   41.29      .8   40.79
     1.6   39.69     3.4   39.69       4   40.89     4.8   41.49       7   41.49
      11   40.19      21   40.19
#Mann= 3 , 0 , 0
   -12.4    .033       0       0    .033       0     4.8    .033       0
#XS Ineff= 2 , 0
               0   41.29     4.8           41.49
Permanent Ineff=
       F       F
Bank Sta=0,4.8
XS Rating Curve= 0
Exp/Cntr=.3,.1

Type RM Length L Ch R = 1 ,2000.00 ,50,50,50
BEGIN DESCRIPTION:
40
END DESCRIPTION:
#Sta/Elev= 14
   -11.7   38.72    -1.7   38.72     -.5   40.12       0   40.12      .8   39.52
     1.6   38.52     2.6   38.52     2.8   38.92     3.6   38.92     3.9   39.52
     4.1   39.82     6.1   39.82     7.4   38.52    17.4   38.52
#Mann= 3 , 0 , 0
   -11.7    .033       0       0    .033       0     4.1    .033       0
#XS Ineff= 2 , 0
               0   40.12     4.1           39.82
Permanent Ineff=
       F       F
Bank Sta=0,4.1
XS Rating Curve= 0
Exp/Cntr=.3,.1

Type RM Length L Ch R = 1 ,1950.00 ,2,2,2
BEGIN DESCRIPTION:
39
END DESCRIPTION:
#Sta/Elev= 12
   -12.2   37.97    -2.2   37.97     -.6   38.57       0   38.77     1.4   37.07
     2.4   37.07     2.9   37.47     3.7   38.77     4.3   39.17     5.9   39.17
     7.9   37.57    17.9   37.57
#Mann= 3 , 0 , 0
   -12.2    .033       0       0    .033       0     4.3    .033       0
#XS Ineff= 2 , 0
               0   38.77     4.3           39.17
Permanent Ineff=
       F       F
Bank Sta=0,4.3
XS Rating Curve= 0
Exp/Cntr=.3,.1

Type RM Length L Ch R = 1 ,1948.00 ,48,48,48
BEGIN DESCRIPTION:
38.048
END DESCRIPTION:
#Sta/Elev= 12
   -12.2   37.84    -2.2   37.84     -.6   38.44       0   38.64     1.4   37.04
     2.4   37.04     2.9   37.44     3.7   38.74     4.3   39.14     5.9   39.14
     7.9   37.54    17.9   37.54
#Mann= 3 , 0 , 0
   -12.2    .033       0       0    .033       0     4.3    .033       0
#XS Ineff= 2 , 0
               0   38.64     4.3           39.14
Permanent Ineff=
       F       F
Bank Sta=0,4.3
XS Rating Curve= 0
Exp/Cntr=.3,.1

Type RM Length L Ch R = 1 ,1900.00 ,50,50,50
BEGIN DESCRIPTION:
38
END DESCRIPTION:
#Sta/Elev= 13
   -11.3   36.98    -1.3   36.98     -.6   37.68       0   37.68      .6   37.08
     1.1   36.78     2.1   36.38     3.1   36.18     3.7   37.28     4.5   37.78
     5.3   37.78     7.1   36.28    17.1   36.28
#Mann= 3 , 0 , 0
   -11.3    .033       0       0    .033       0     4.5    .033       0
#XS Ineff= 2 , 0
               0   37.68     4.5           37.78
Permanent Ineff=
       F       F
Bank Sta=0,4.5
XS Rating Curve= 0
Exp/Cntr=.3,.1

Type RM Length L Ch R = 1 ,1850.00 ,32,32,32
BEGIN DESCRIPTION:
37
END DESCRIPTION:
#Sta/Elev= 13
   -11.3   35.87    -1.3   35.87     -.6   36.57       0   36.57      .6   35.97
     1.1   35.57     2.1   35.07     3.1   34.97     3.7   36.07     4.5   36.57
     5.3   36.57     7.1   35.07    17.1   35.07
#Mann= 3 , 0 , 0
   -11.3    .033       0       0    .033       0     4.5    .033       0
#XS Ineff= 2 , 0
               0   36.57     4.5           36.57
Permanent Ineff=
       F       F
Bank Sta=0,4.5
XS Rating Curve= 0
Exp/Cntr=.3,.1

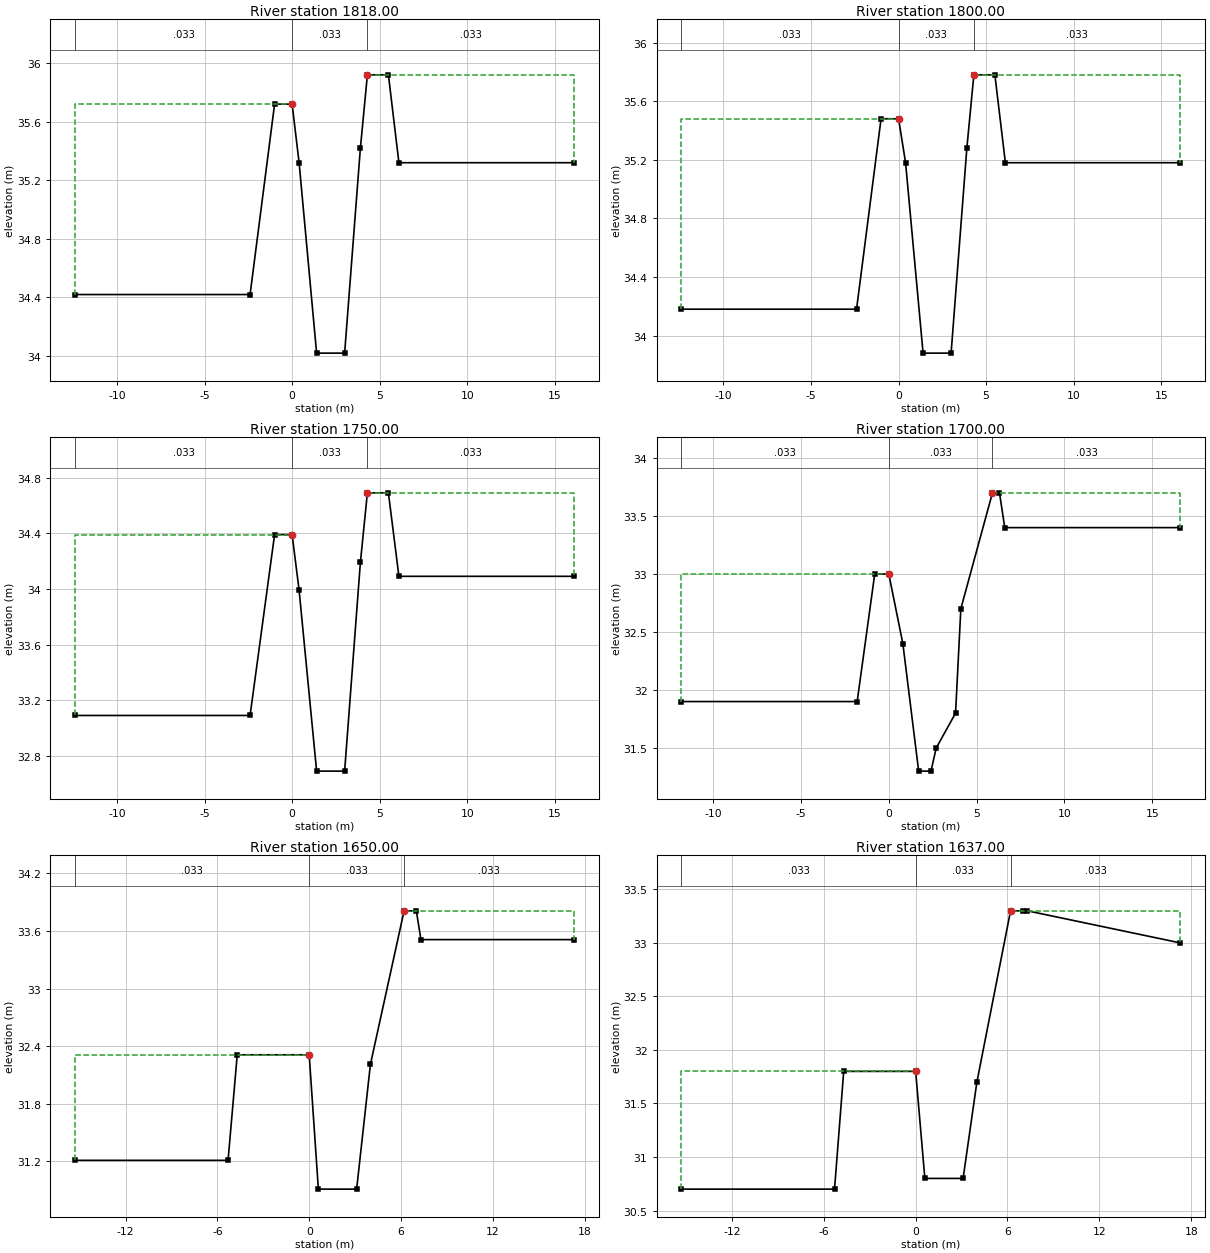
Type RM Length L Ch R = 1 ,1818.00 ,18,18,18
BEGIN DESCRIPTION:
36.018
END DESCRIPTION:
#Sta/Elev= 12
   -12.4   34.42    -2.4   34.42      -1   35.72       0   35.72      .4   35.32
     1.4   34.02       3   34.02     3.9   35.42     4.3   35.92     5.5   35.92
     6.1   35.32    16.1   35.32
#Mann= 3 , 0 , 0
   -12.4    .033       0       0    .033       0     4.3    .033       0
#XS Ineff= 2 , 0
               0   35.72     4.3           35.92
Permanent Ineff=
       F       F
Bank Sta=0,4.3
XS Rating Curve= 0
Exp/Cntr=.3,.1

Type RM Length L Ch R = 1 ,1800.00 ,50,50,50
BEGIN DESCRIPTION:
36
END DESCRIPTION:
#Sta/Elev= 12
   -12.4   34.18    -2.4   34.18      -1   35.48       0   35.48      .4   35.18
     1.4   33.88       3   33.88     3.9   35.28     4.3   35.78     5.5   35.78
     6.1   35.18    16.1   35.18
#Mann= 3 , 0 , 0
   -12.4    .033       0       0    .033       0     4.3    .033       0
#XS Ineff= 2 , 0
               0   35.48     4.3           35.78
Permanent Ineff=
       F       F
Bank Sta=0,4.3
XS Rating Curve= 0
Exp/Cntr=.3,.1

Type RM Length L Ch R = 1 ,1750.00 ,50,50,50
BEGIN DESCRIPTION:
35
END DESCRIPTION:
#Sta/Elev= 12
   -12.4   33.09    -2.4   33.09      -1   34.39       0   34.39      .4   33.99
     1.4   32.69       3   32.69     3.9   34.19     4.3   34.69     5.5   34.69
     6.1   34.09    16.1   34.09
#Mann= 3 , 0 , 0
   -12.4    .033       0       0    .033       0     4.3    .033       0
#XS Ineff= 2 , 0
               0   34.39     4.3           34.69
Permanent Ineff=
       F       F
Bank Sta=0,4.3
XS Rating Curve= 0
Exp/Cntr=.3,.1

Type RM Length L Ch R = 1 ,1700.00 ,50,50,50
BEGIN DESCRIPTION:
34
END DESCRIPTION:
#Sta/Elev= 14
   -11.8    31.9    -1.8    31.9     -.8      33       0      33      .8    32.4
     1.7    31.3     2.4    31.3     2.7    31.5     3.8    31.8     4.1    32.7
     5.9    33.7     6.3    33.7     6.6    33.4    16.6    33.4
#Mann= 3 , 0 , 0
   -11.8    .033       0       0    .033       0     5.9    .033       0
#XS Ineff= 2 , 0
               0      33     5.9            33.7
Permanent Ineff=
       F       F
Bank Sta=0,5.9
XS Rating Curve= 0
Exp/Cntr=.3,.1

Type RM Length L Ch R = 1 ,1650.00 ,13,13,13
BEGIN DESCRIPTION:
33
END DESCRIPTION:
#Sta/Elev= 11
   -15.3   31.21    -5.3   31.21    -4.7   32.31       0   32.31      .6   30.91
     3.1   30.91       4   32.21     6.2   33.81       7   33.81     7.3   33.51
    17.3   33.51
#Mann= 3 , 0 , 0
   -15.3    .033       0       0    .033       0     6.2    .033       0
#XS Ineff= 2 , 0
               0   32.31     6.2           33.81
Permanent Ineff=
       F       F
Bank Sta=0,6.2
XS Rating Curve= 0
Exp/Cntr=.3,.1

Type RM Length L Ch R = 1 ,1637.00 ,37,37,37
BEGIN DESCRIPTION:
32.037
END DESCRIPTION:
#Sta/Elev= 11
   -15.3    30.7    -5.3    30.7    -4.7    31.8       0    31.8      .6    30.8
     3.1    30.8       4    31.7     6.2    33.3       7    33.3     7.3    33.3
    17.3      33
#Mann= 3 , 0 , 0
   -15.3    .033       0       0    .033       0     6.2    .033       0
#XS Ineff= 2 , 0
               0    31.8     6.2            33.3
Permanent Ineff=
       F       F
Bank Sta=0,6.2
XS Rating Curve= 0
Exp/Cntr=.3,.1

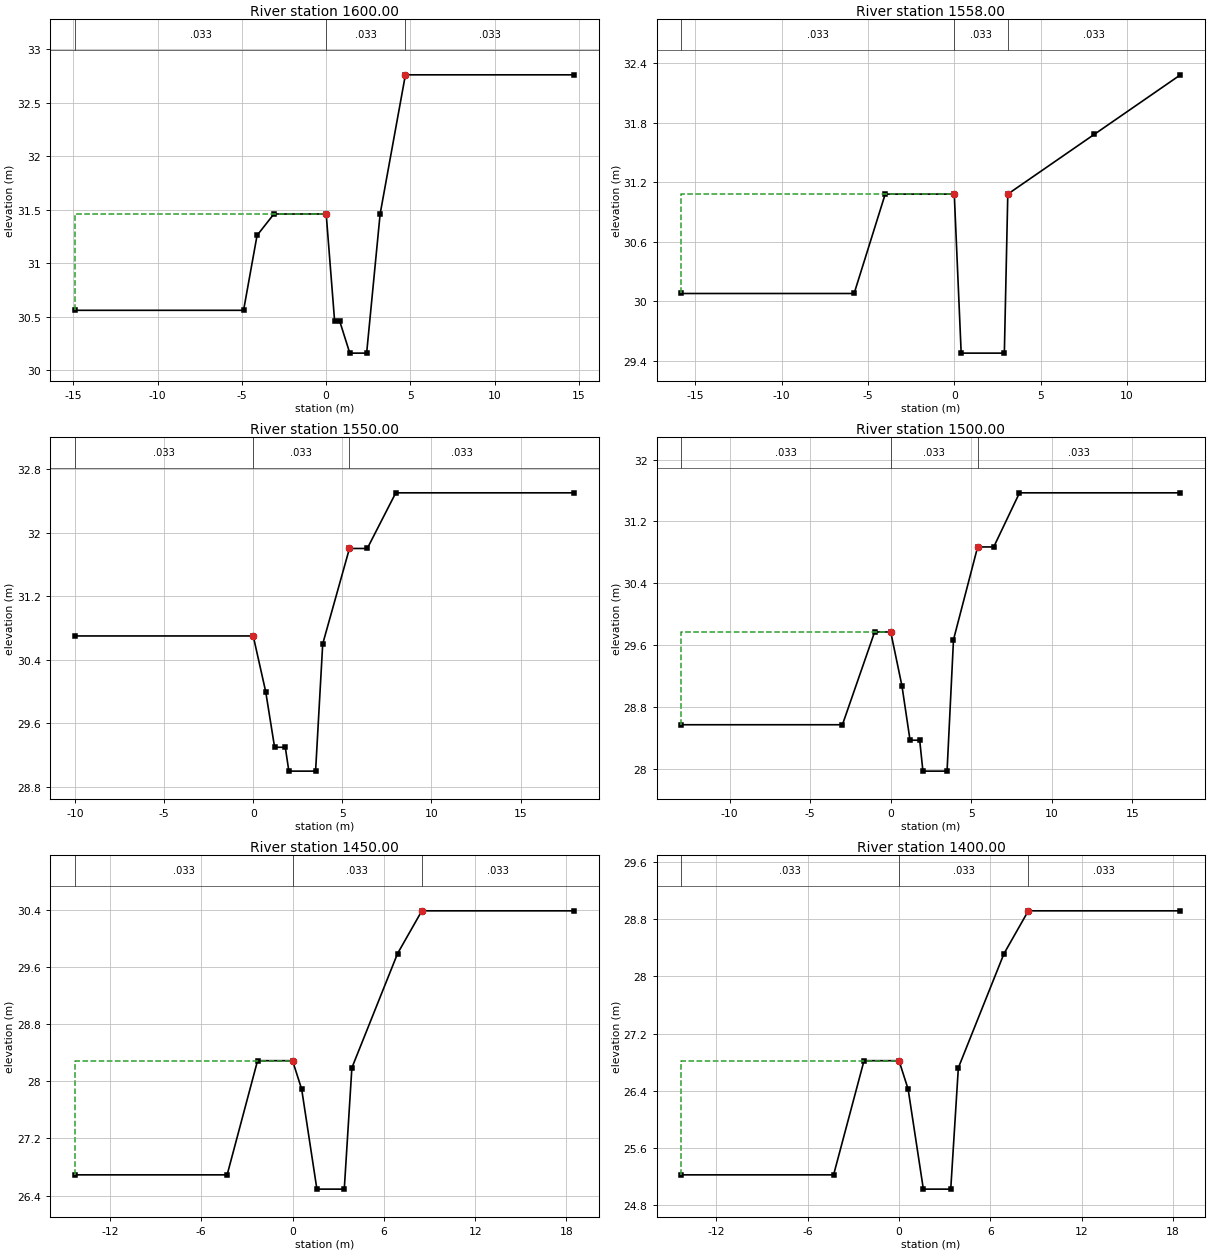
Type RM Length L Ch R = 1 ,1600.00 ,42,42,42
BEGIN DESCRIPTION:
32
END DESCRIPTION:
#Sta/Elev= 12
   -14.9   30.56    -4.9   30.56    -4.1   31.26    -3.1   31.46       0   31.46
      .5   30.46      .8   30.46     1.4   30.16     2.4   30.16     3.2   31.46
     4.7   32.76    14.7   32.76
#Mann= 3 , 0 , 0
   -14.9    .033       0       0    .033       0     4.7    .033       0
#XS Ineff= 2 , 0
               0   31.46     4.7           32.76
Permanent Ineff=
       F       F
Bank Sta=0,4.7
XS Rating Curve= 0
Exp/Cntr=.3,.1

Type RM Length L Ch R = 1 ,1558.00 ,8,8,8
BEGIN DESCRIPTION:
31.008
END DESCRIPTION:
#Sta/Elev= 9
   -15.8   30.08    -5.8   30.08      -4   31.08       0   31.08      .4   29.48
     2.9   29.48     3.1   31.08     8.1   31.68    13.1   32.28
#Mann= 3 , 0 , 0
   -15.8    .033       0       0    .033       0     3.1    .033       0
#XS Ineff= 2 , 0
               0   31.08     3.1           31.08
Permanent Ineff=
       F       F
Bank Sta=0,3.1
XS Rating Curve= 0
Exp/Cntr=.3,.1

Type RM Length L Ch R = 1 ,1550.00 ,50,50,50
BEGIN DESCRIPTION:
31
END DESCRIPTION:
#Sta/Elev= 12
     -10    30.7       0    30.7      .7      30     1.2    29.3     1.8    29.3
       2      29     3.5      29     3.9    30.6     5.4    31.8     6.4    31.8
       8    32.5      18    32.5
#Mann= 3 , 0 , 0
     -10    .033       0       0    .033       0     5.4    .033       0
#XS Ineff= 2 , 0
               0    30.7     5.4            31.8
Permanent Ineff=
       F       F
Bank Sta=0,5.4
XS Rating Curve= 0
Exp/Cntr=.3,.1

Type RM Length L Ch R = 1 ,1500.00 ,50,50,50
BEGIN DESCRIPTION:
30
END DESCRIPTION:
#Sta/Elev= 14
     -13   28.57      -3   28.57      -1   29.77       0   29.77      .7   29.07
     1.2   28.37     1.8   28.37       2   27.97     3.5   27.97     3.9   29.67
     5.4   30.87     6.4   30.87       8   31.57      18   31.57
#Mann= 3 , 0 , 0
     -13    .033       0       0    .033       0     5.4    .033       0
#XS Ineff= 2 , 0
               0   29.77     5.4           30.87
Permanent Ineff=
       F       F
Bank Sta=0,5.4
XS Rating Curve= 0
Exp/Cntr=.3,.1

Type RM Length L Ch R = 1 ,1450.00 ,50,50,50
BEGIN DESCRIPTION:
29
END DESCRIPTION:
#Sta/Elev= 11
   -14.3   26.69    -4.3   26.69    -2.3   28.29       0   28.29      .6   27.89
     1.6   26.49     3.4   26.49     3.9   28.19     6.9   29.79     8.5   30.39
    18.5   30.39
#Mann= 3 , 0 , 0
   -14.3    .033       0       0    .033       0     8.5    .033       0
#XS Ineff= 2 , 0
               0   28.29     8.5           30.39
Permanent Ineff=
       F       F
Bank Sta=0,8.5
XS Rating Curve= 0
Exp/Cntr=.3,.1

Type RM Length L Ch R = 1 ,1400.00 ,7,7,7
BEGIN DESCRIPTION:
28
END DESCRIPTION:
#Sta/Elev= 11
   -14.3   25.22    -4.3   25.22    -2.3   26.82       0   26.82      .6   26.42
     1.6   25.02     3.4   25.02     3.9   26.72     6.9   28.32     8.5   28.92
    18.5   28.92
#Mann= 3 , 0 , 0
   -14.3    .033       0       0    .033       0     8.5    .033       0
#XS Ineff= 2 , 0
               0   26.82     8.5           28.92
Permanent Ineff=
       F       F
Bank Sta=0,8.5
XS Rating Curve= 0
Exp/Cntr=.3,.1