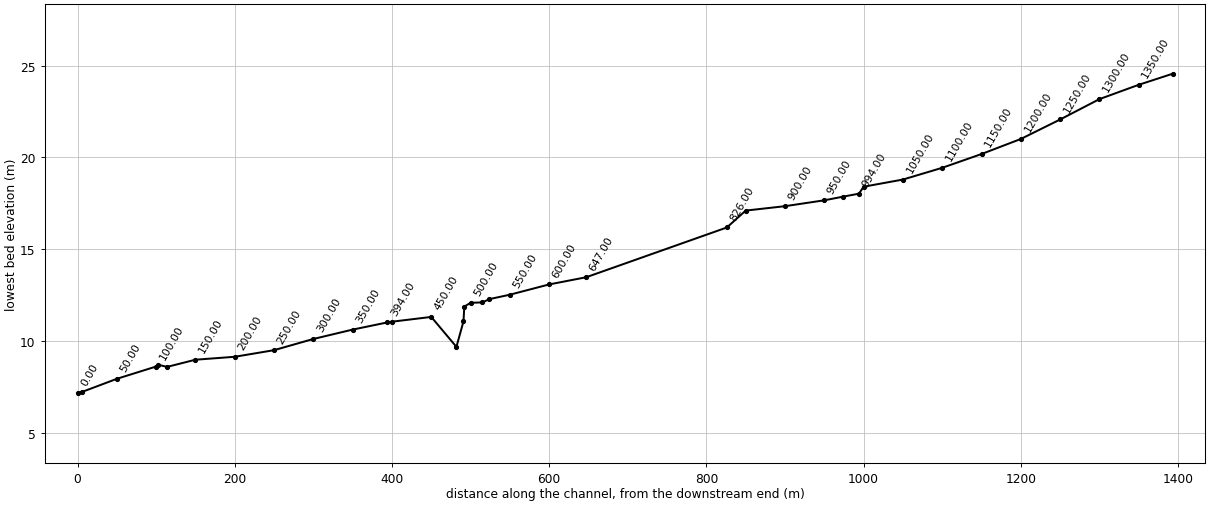
HEC-RAS study OKMA.prj: OKMA

--- OKMA.g01 (geometry) --- (continued)

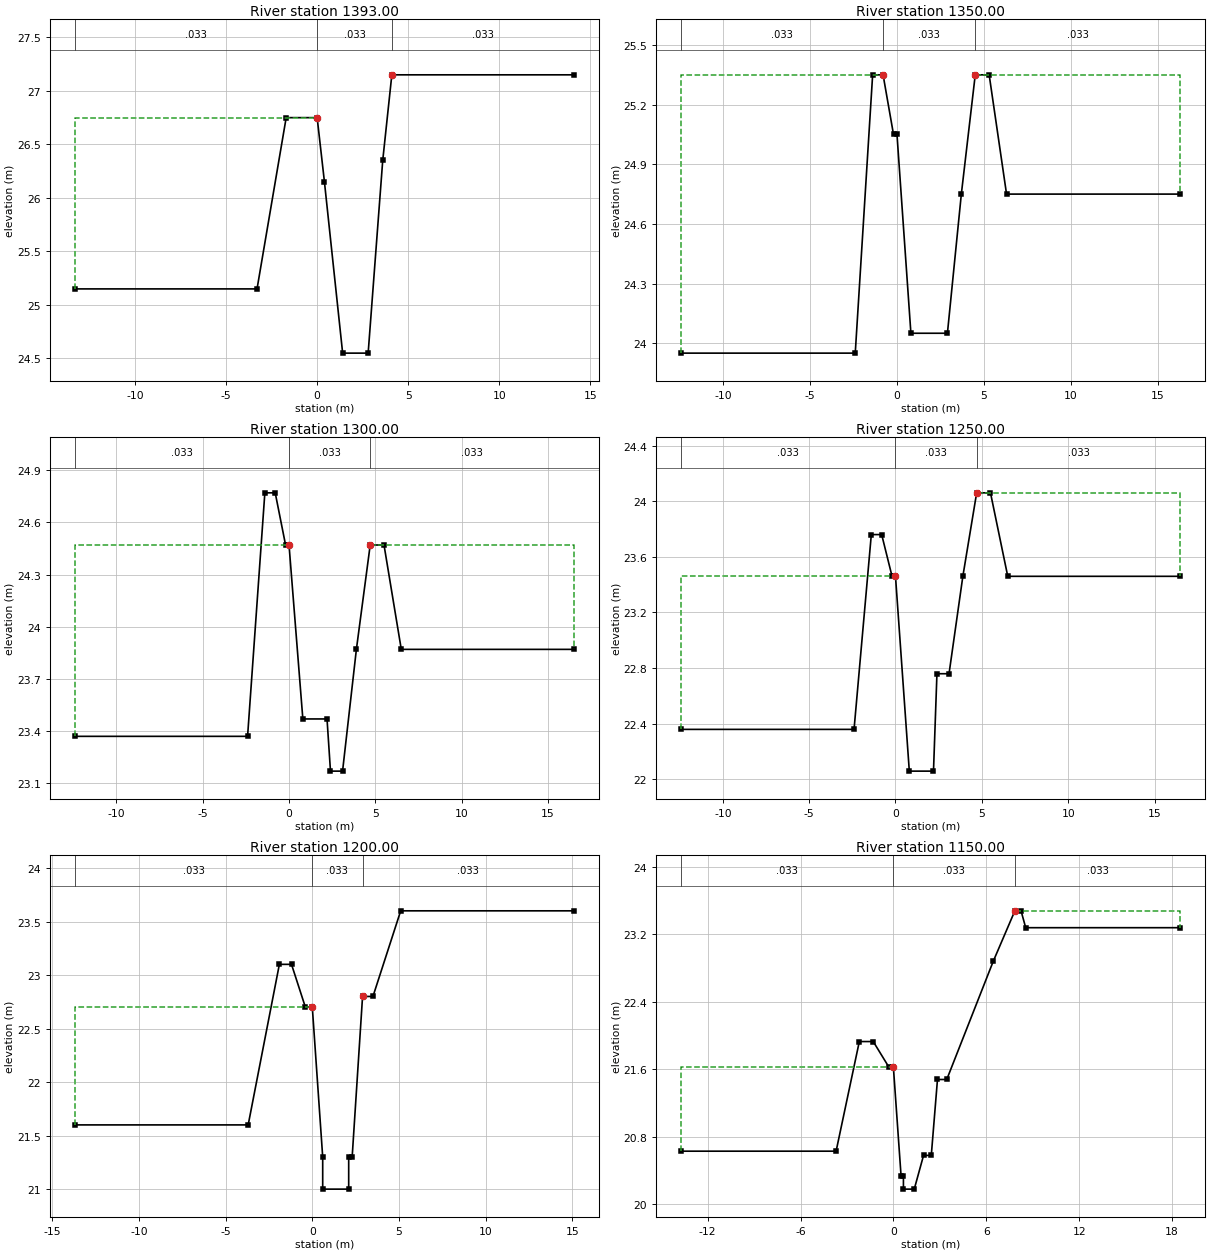
Type RM Length L Ch R = 1 ,1393.00 ,43,43,43
BEGIN DESCRIPTION:
27.043
END DESCRIPTION:
#Sta/Elev= 10
   -13.3   25.15    -3.3   25.15    -1.7   26.75       0   26.75      .4   26.15
     1.4   24.55     2.8   24.55     3.6   26.35     4.1   27.15    14.1   27.15
#Mann= 3 , 0 , 0
   -13.3    .033       0       0    .033       0     4.1    .033       0
#XS Ineff= 2 , 0
               0   26.75     4.1           27.15
Permanent Ineff=
       F       F
Bank Sta=0,4.1
XS Rating Curve= 0
Exp/Cntr=.3,.1

Type RM Length L Ch R = 1 ,1350.00 ,50,50,50
BEGIN DESCRIPTION:
27
END DESCRIPTION:
#Sta/Elev= 13
   -12.4   23.95    -2.4   23.95    -1.4   25.35     -.8   25.35     -.2   25.05
       0   25.05      .8   24.05     2.9   24.05     3.7   24.75     4.5   25.35
     5.3   25.35     6.3   24.75    16.3   24.75
#Mann= 3 , 0 , 0
   -12.4    .033       0     -.8    .033       0     4.5    .033       0
#XS Ineff= 2 , 0
             -.8   25.35     4.5           25.35
Permanent Ineff=
       F       F
Bank Sta=-.8,4.5
XS Rating Curve= 0
Exp/Cntr=.3,.1

Type RM Length L Ch R = 1 ,1300.00 ,50,50,50
BEGIN DESCRIPTION:
26
END DESCRIPTION:
#Sta/Elev= 15
   -12.4   23.37    -2.4   23.37    -1.4   24.77     -.8   24.77     -.2   24.47
       0   24.47      .8   23.47     2.2   23.47     2.4   23.17     3.1   23.17
     3.9   23.87     4.7   24.47     5.5   24.47     6.5   23.87    16.5   23.87
#Mann= 3 , 0 , 0
   -12.4    .033       0       0    .033       0     4.7    .033       0
#XS Ineff= 2 , 0
               0   24.47     4.7           24.47
Permanent Ineff=
       F       F
Bank Sta=0,4.7
XS Rating Curve= 0
Exp/Cntr=.3,.1

Type RM Length L Ch R = 1 ,1250.00 ,50,50,50
BEGIN DESCRIPTION:
25
END DESCRIPTION:
#Sta/Elev= 15
   -12.4   22.36    -2.4   22.36    -1.4   23.76     -.8   23.76     -.2   23.46
       0   23.46      .8   22.06     2.2   22.06     2.4   22.76     3.1   22.76
     3.9   23.46     4.7   24.06     5.5   24.06     6.5   23.46    16.5   23.46
#Mann= 3 , 0 , 0
   -12.4    .033       0       0    .033       0     4.7    .033       0
#XS Ineff= 2 , 0
               0   23.46     4.7           24.06
Permanent Ineff=
       F       F
Bank Sta=0,4.7
XS Rating Curve= 0
Exp/Cntr=.3,.1

Type RM Length L Ch R = 1 ,1200.00 ,50,50,50
BEGIN DESCRIPTION:
24
END DESCRIPTION:
#Sta/Elev= 15
   -13.7    21.6    -3.7    21.6    -1.9    23.1    -1.2    23.1     -.4    22.7
       0    22.7      .6    21.3      .6      21     2.1      21     2.1    21.3
     2.3    21.3     2.9    22.8     3.5    22.8     5.1    23.6    15.1    23.6
#Mann= 3 , 0 , 0
   -13.7    .033       0       0    .033       0     2.9    .033       0
#XS Ineff= 2 , 0
               0    22.7     2.9            22.8
Permanent Ineff=
       F       F
Bank Sta=0,2.9
XS Rating Curve= 0
Exp/Cntr=.3,.1

Type RM Length L Ch R = 1 ,1150.00 ,50,50,50
BEGIN DESCRIPTION:
23
END DESCRIPTION:
#Sta/Elev= 19
   -13.7   20.63    -3.7   20.63    -2.2   21.93    -1.3   21.93     -.3   21.63
       0   21.63      .5   20.33     .65   20.33     .65   20.18    1.35   20.18
    1.95   20.58    2.45   20.58    2.85   21.48    3.45   21.48    6.45   22.88
    7.85   23.48    8.25   23.48    8.55   23.28   18.55   23.28
#Mann= 3 , 0 , 0
   -13.7    .033       0       0    .033       0    7.85    .033       0
#XS Ineff= 2 , 0
               0   21.63    7.85           23.48
Permanent Ineff=
       F       F
Bank Sta=0,7.85
XS Rating Curve= 0
Exp/Cntr=.3,.1

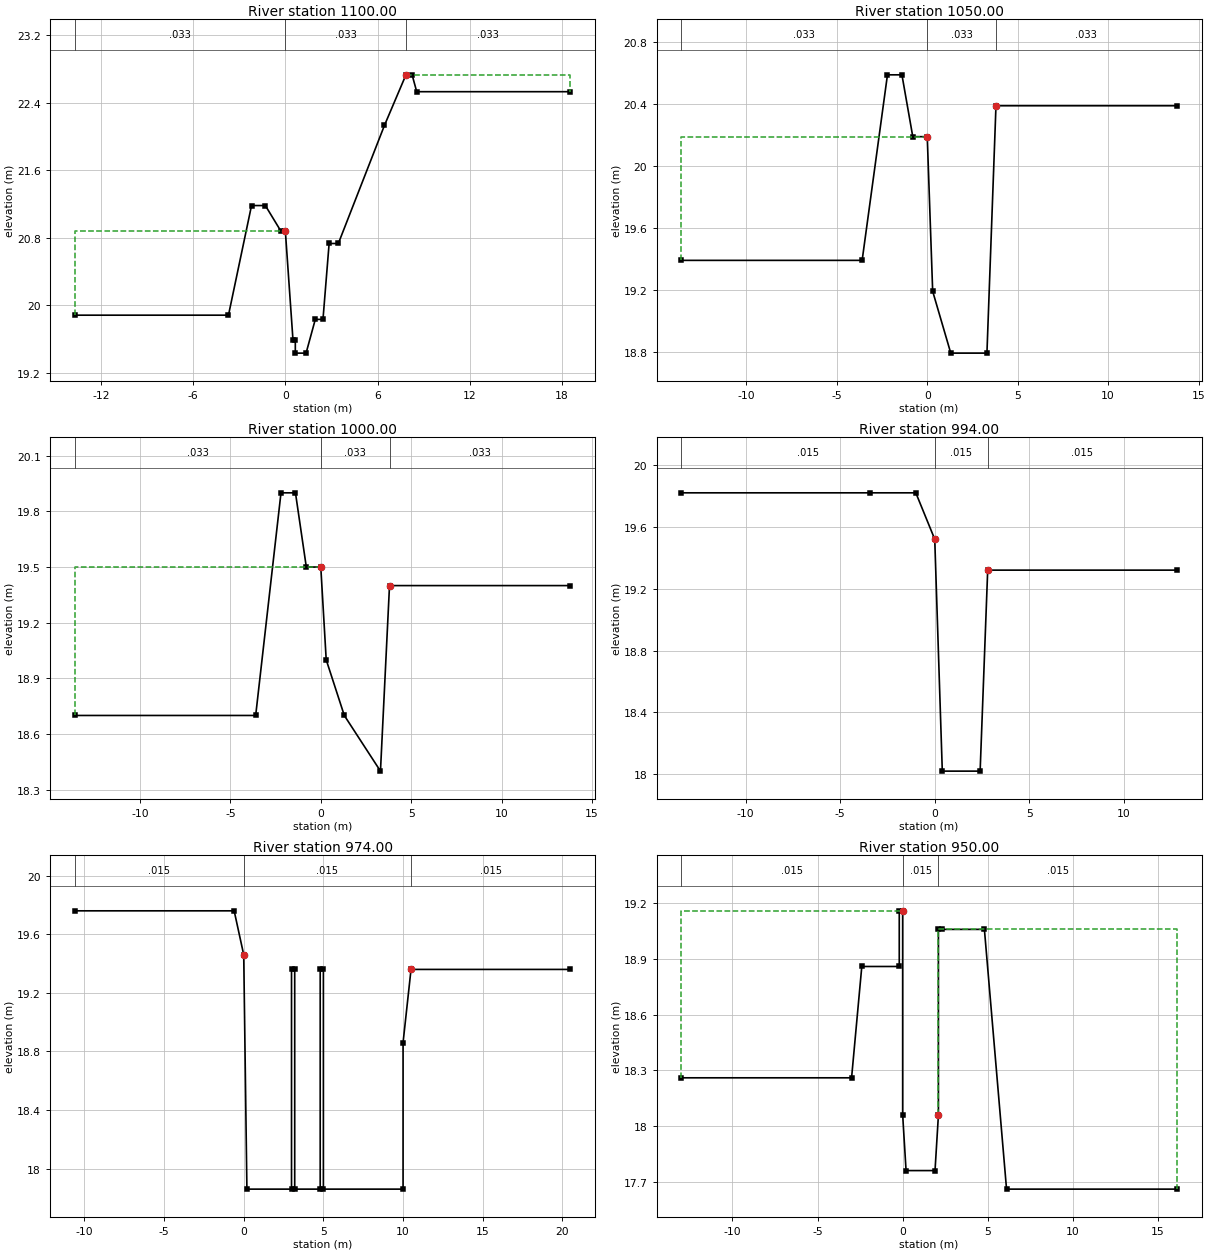
Type RM Length L Ch R = 1 ,1100.00 ,50,50,50
BEGIN DESCRIPTION:
22
END DESCRIPTION:
#Sta/Elev= 19
   -13.7   19.88    -3.7   19.88    -2.2   21.18    -1.3   21.18     -.3   20.88
       0   20.88      .5   19.58     .65   19.58     .65   19.43    1.35   19.43
    1.95   19.83    2.45   19.83    2.85   20.73    3.45   20.73    6.45   22.13
    7.85   22.73    8.25   22.73    8.55   22.53   18.55   22.53
#Mann= 3 , 0 , 0
   -13.7    .033       0       0    .033       0    7.85    .033       0
#XS Ineff= 2 , 0
               0   20.88    7.85           22.73
Permanent Ineff=
       F       F
Bank Sta=0,7.85
XS Rating Curve= 0
Exp/Cntr=.3,.1

Type RM Length L Ch R = 1 ,1050.00 ,50,50,50
BEGIN DESCRIPTION:
21
END DESCRIPTION:
#Sta/Elev= 11
   -13.6   19.39    -3.6   19.39    -2.2   20.59    -1.4   20.59     -.8   20.19
       0   20.19      .3   19.19     1.3   18.79     3.3   18.79     3.8   20.39
    13.8   20.39
#Mann= 3 , 0 , 0
   -13.6    .033       0       0    .033       0     3.8    .033       0
#XS Ineff= 2 , 0
               0   20.19     3.8           20.39
Permanent Ineff=
       F       F
Bank Sta=0,3.8
XS Rating Curve= 0
Exp/Cntr=.3,.1

Type RM Length L Ch R = 1 ,1000.00 ,6,6,6
BEGIN DESCRIPTION:
20
END DESCRIPTION:
#Sta/Elev= 11
   -13.6    18.7    -3.6    18.7    -2.2    19.9    -1.4    19.9     -.8    19.5
       0    19.5      .3      19     1.3    18.7     3.3    18.4     3.8    19.4
    13.8    19.4
#Mann= 3 , 0 , 0
   -13.6    .033       0       0    .033       0     3.8    .033       0
#XS Ineff= 2 , 0
               0    19.5     3.8            19.4
Permanent Ineff=
       F       F
Bank Sta=0,3.8
XS Rating Curve= 0
Exp/Cntr=.3,.1

Type RM Length L Ch R = 1 ,994.00  ,20,20,20
BEGIN DESCRIPTION:
19.044
END DESCRIPTION:
#Sta/Elev= 8
   -13.4   19.82    -3.4   19.82      -1   19.82       0   19.52      .4   18.02
     2.4   18.02     2.8   19.32    12.8   19.32
#Mann= 3 , 0 , 0
   -13.4    .015       0       0    .015       0     2.8    .015       0
#XS Ineff= 2 , 0
               0   19.52     2.8           19.32
Permanent Ineff=
       F       F
Bank Sta=0,2.8
XS Rating Curve= 0
Exp/Cntr=.3,.1

Type RM Length L Ch R = 1 ,974.00  ,24,24,24
BEGIN DESCRIPTION:
19.024
END DESCRIPTION:
#Sta/Elev= 16
   -10.6   19.76     -.6   19.76       0   19.46      .2   17.86       3   17.86
       3   19.36     3.2   19.36     3.2   17.86     4.8   17.86     4.8   19.36
       5   19.36       5   17.86      10   17.86      10   18.86    10.5   19.36
    20.5   19.36
#Mann= 3 , 0 , 0
   -10.6    .015       0       0    .015       0    10.5    .015       0
#XS Ineff= 2 , 0
               0   19.46    10.5           19.36
Permanent Ineff=
       F       F
Bank Sta=0,10.5
XS Rating Curve= 0
Exp/Cntr=.3,.1

Type RM Length L Ch R = 1 ,950.00  ,50,50,50
BEGIN DESCRIPTION:
19
END DESCRIPTION:
#Sta/Elev= 15
     -13   18.26      -3   18.26    -2.4   18.86     -.2   18.86     -.2   19.16
       0   19.16       0   18.06      .2   17.76     1.9   17.76     2.1   18.06
     2.1   19.06     2.3   19.06     4.8   19.06     6.1   17.66    16.1   17.66
#Mann= 3 , 0 , 0
     -13    .015       0       0    .015       0     2.1    .015       0
#XS Ineff= 2 , 0
               0   19.16     2.1           19.06
Permanent Ineff=
       F       F
Bank Sta=0,2.1
XS Rating Curve= 0
Exp/Cntr=.3,.1

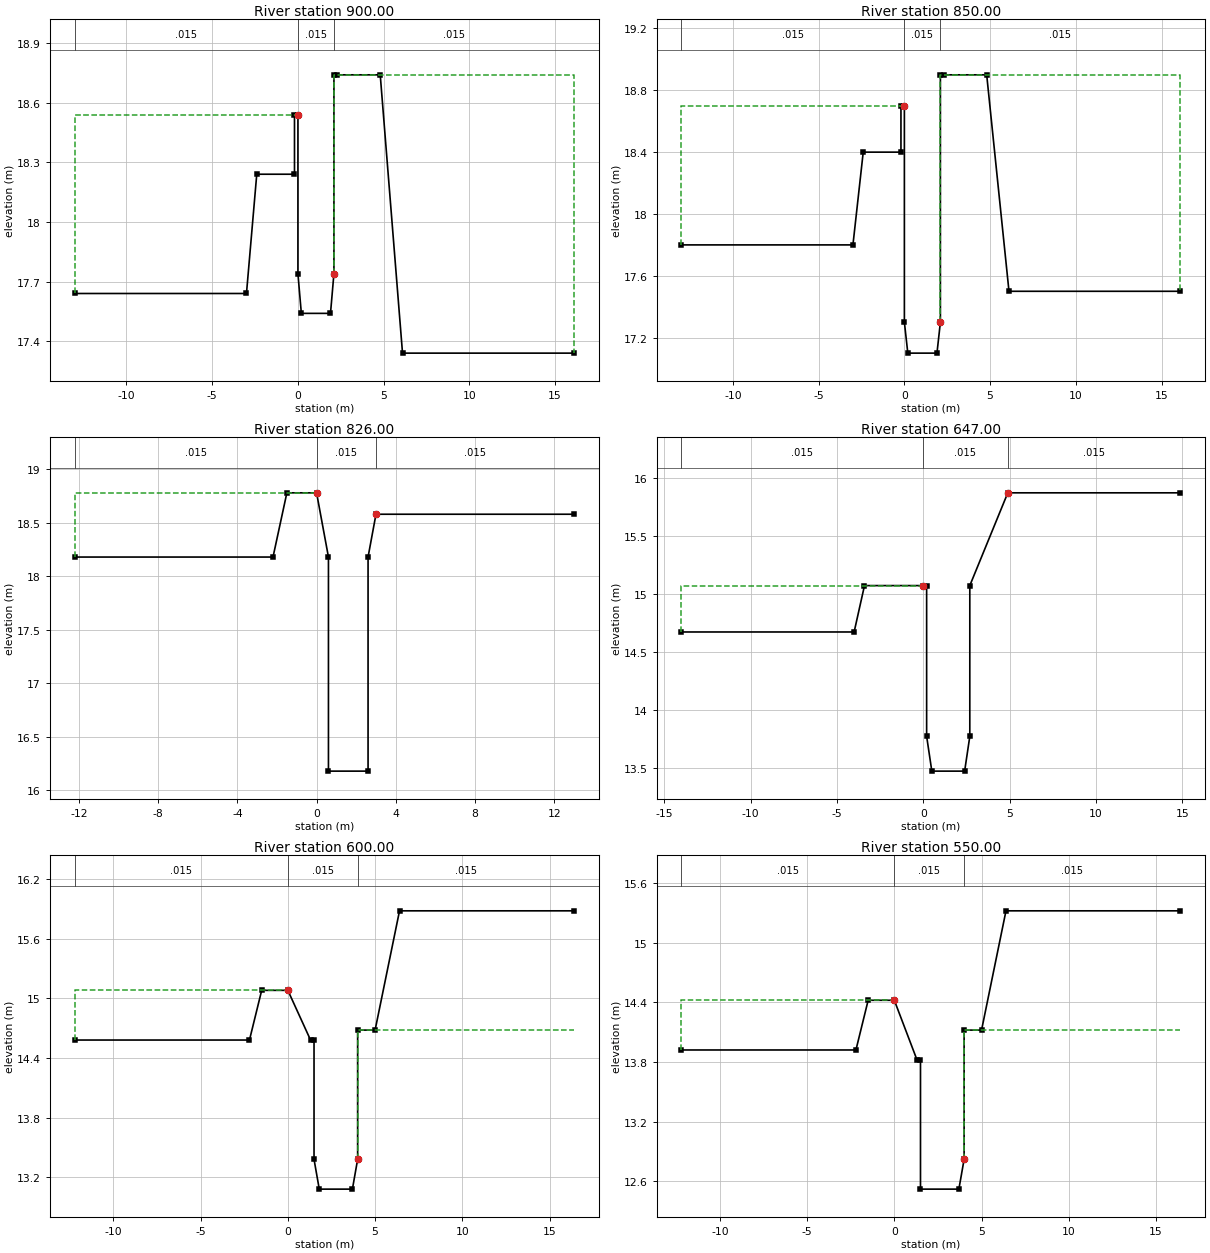
Type RM Length L Ch R = 1 ,900.00  ,50,50,50
BEGIN DESCRIPTION:
18
END DESCRIPTION:
#Sta/Elev= 15
     -13   17.64      -3   17.64    -2.4   18.24     -.2   18.24     -.2   18.54
       0   18.54       0   17.74      .2   17.54     1.9   17.54     2.1   17.74
     2.1   18.74     2.3   18.74     4.8   18.74     6.1   17.34    16.1   17.34
#Mann= 3 , 0 , 0
     -13    .015       0       0    .015       0     2.1    .015       0
#XS Ineff= 2 , 0
               0   18.54     2.1           18.74
Permanent Ineff=
       F       F
Bank Sta=0,2.1
XS Rating Curve= 0
Exp/Cntr=.3,.1

Type RM Length L Ch R = 1 ,850.00  ,24,24,24
BEGIN DESCRIPTION:
17
END DESCRIPTION:
#Sta/Elev= 15
     -13    17.8      -3    17.8    -2.4    18.4     -.2    18.4     -.2    18.7
       0    18.7       0    17.3      .2    17.1     1.9    17.1     2.1    17.3
     2.1    18.9     2.3    18.9     4.8    18.9     6.1    17.5    16.1    17.5
#Mann= 3 , 0 , 0
     -13    .015       0       0    .015       0     2.1    .015       0
#XS Ineff= 2 , 0
               0    18.7     2.1            18.9
Permanent Ineff=
       F       F
Bank Sta=0,2.1
XS Rating Curve= 0
Exp/Cntr=.3,.1

Type RM Length L Ch R = 1 ,826.00  ,179,179,179
BEGIN DESCRIPTION:
16.026
END DESCRIPTION:
#Sta/Elev= 10
   -12.2   18.18    -2.2   18.18    -1.5   18.78       0   18.78      .6   18.18
      .6   16.18     2.6   16.18     2.6   18.18       3   18.58      13   18.58
#Mann= 3 , 0 , 0
   -12.2    .015       0       0    .015       0       3    .015       0
#XS Ineff= 2 , 0
               0   18.78       3           18.58
Permanent Ineff=
       F       F
Bank Sta=0,3
XS Rating Curve= 0
Exp/Cntr=.3,.1

Type RM Length L Ch R = 1 ,647.00  ,47,47,47
BEGIN DESCRIPTION:
12.047
END DESCRIPTION:
#Sta/Elev= 12
     -14   14.67      -4   14.67    -3.4   15.07       0   15.07      .2   15.07
      .2   13.77      .5   13.47     2.4   13.47     2.7   13.77     2.7   15.07
     4.9   15.87    14.9   15.87
#Mann= 3 , 0 , 0
     -14    .015       0       0    .015       0     4.9    .015       0
#XS Ineff= 2 , 0
               0   15.07     4.9           15.87
Permanent Ineff=
       F       F
Bank Sta=0,4.9
XS Rating Curve= 0
Exp/Cntr=.3,.1

Type RM Length L Ch R = 1 ,600.00  ,50,50,50
BEGIN DESCRIPTION:
12
END DESCRIPTION:
#Sta/Elev= 14
   -12.2   14.58    -2.2   14.58    -1.5   15.08       0   15.08     1.3   14.58
     1.5   14.58     1.5   13.38     1.8   13.08     3.7   13.08       4   13.38
       4   14.68       5   14.68     6.4   15.88    16.4   15.88
#Mann= 3 , 0 , 0
   -12.2    .015       0       0    .015       0       4    .015       0
#XS Ineff= 2 , 0
               0   15.08       4           14.68
Permanent Ineff=
       F       F
Bank Sta=0,4
XS Rating Curve= 0
Exp/Cntr=.3,.1

Type RM Length L Ch R = 1 ,550.00  ,26,26,26
BEGIN DESCRIPTION:
11
END DESCRIPTION:
#Sta/Elev= 13
   -12.2   13.92    -2.2   13.92    -1.5   14.42       0   14.42     1.3   13.82
     1.5   13.82     1.5   12.52     3.7   12.52       4   12.82       4   14.12
       5   14.12     6.4   15.32    16.4   15.32
#Mann= 3 , 0 , 0
   -12.2    .015       0       0    .015       0       4    .015       0
#XS Ineff= 2 , 0
               0   14.42       4           14.12
Permanent Ineff=
       F       F
Bank Sta=0,4
XS Rating Curve= 0
Exp/Cntr=.3,.1

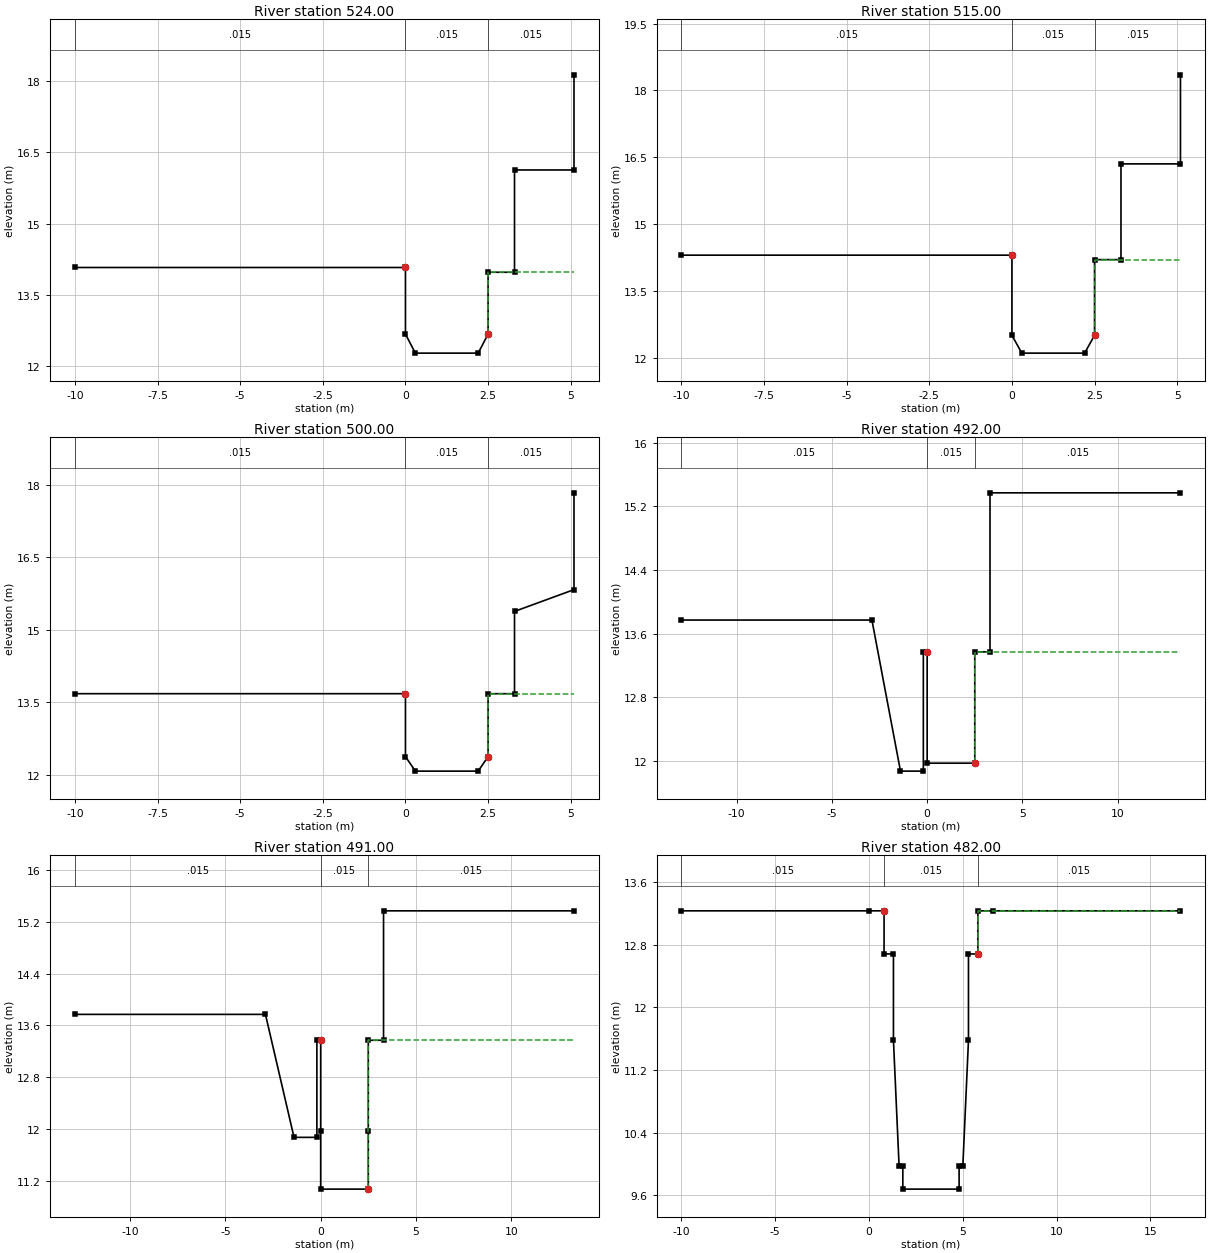
Type RM Length L Ch R = 1 ,524.00  ,9,9,9
BEGIN DESCRIPTION:
10.024
END DESCRIPTION:
#Sta/Elev= 11
     -10   14.08       0   14.08       0   12.68      .3   12.28     2.2   12.28
     2.5   12.68     2.5   13.98     3.3   13.98     3.3   16.13     5.1   16.13
     5.1   18.13
#Mann= 3 , 0 , 0
     -10    .015       0       0    .015       0     2.5    .015       0
#XS Ineff= 2 , 0
               0   14.08     2.5           13.98
Permanent Ineff=
       F       F
Bank Sta=0,2.5
XS Rating Curve= 0
Exp/Cntr=.3,.1

Type RM Length L Ch R = 1 ,515.00  ,15,15,15
BEGIN DESCRIPTION:
10.015
END DESCRIPTION:
#Sta/Elev= 11
     -10    14.3       0    14.3       0    12.5      .3    12.1     2.2    12.1
     2.5    12.5     2.5    14.2     3.3    14.2     3.3   16.35     5.1   16.35
     5.1   18.35
#Mann= 3 , 0 , 0
     -10    .015       0       0    .015       0     2.5    .015       0
#XS Ineff= 2 , 0
               0    14.3     2.5            14.2
Permanent Ineff=
       F       F
Bank Sta=0,2.5
XS Rating Curve= 0
Exp/Cntr=.3,.1

Type RM Length L Ch R = 1 ,500.00  ,8,8,8
BEGIN DESCRIPTION:
10
END DESCRIPTION:
#Sta/Elev= 11
     -10   13.68       0   13.68       0   12.38      .3   12.08     2.2   12.08
     2.5   12.38     2.5   13.68     3.3   13.68     3.3   15.38     5.1   15.83
     5.1   17.83
#Mann= 3 , 0 , 0
     -10    .015       0       0    .015       0     2.5    .015       0
#XS Ineff= 2 , 0
               0   13.68     2.5           13.68
Permanent Ineff=
       F       F
Bank Sta=0,2.5
XS Rating Curve= 0
Exp/Cntr=.3,.1

Type RM Length L Ch R = 1 ,492.00  ,1,1,1
BEGIN DESCRIPTION:
9.042
END DESCRIPTION:
#Sta/Elev= 12
   -12.9   13.77    -2.9   13.77    -1.4   11.87     -.2   11.87     -.2   13.37
       0   13.37       0   11.97     2.5   11.97     2.5   13.37     3.3   13.37
     3.3   15.37    13.3   15.37
#Mann= 3 , 0 , 0
   -12.9    .015       0       0    .015       0     2.5    .015       0
#XS Ineff= 2 , 0
               0   13.37     2.5           13.37
Permanent Ineff=
       F       F
Bank Sta=0,2.5
XS Rating Curve= 0
Exp/Cntr=.3,.1

Type RM Length L Ch R = 1 ,491.00  ,9,9,9
BEGIN DESCRIPTION:
9.041
END DESCRIPTION:
#Sta/Elev= 14
   -12.9   13.77    -2.9   13.77    -1.4   11.87     -.2   11.87     -.2   13.37
       0   13.37       0   11.97       0   11.07     2.5   11.07     2.5   11.97
     2.5   13.37     3.3   13.37     3.3   15.37    13.3   15.37
#Mann= 3 , 0 , 0
   -12.9    .015       0       0    .015       0     2.5    .015       0
#XS Ineff= 2 , 0
               0   13.37     2.5           13.37
Permanent Ineff=
       F       F
Bank Sta=0,2.5
XS Rating Curve= 0
Exp/Cntr=.3,.1

Type RM Length L Ch R = 1 ,482.00  ,32,32,32
BEGIN DESCRIPTION:
9.032
END DESCRIPTION:
#Sta/Elev= 18
     -10   13.23       0   13.23      .8   13.23      .8   12.68     1.3   12.68
     1.3   11.58     1.6    9.98     1.8    9.98     1.8    9.68     4.8    9.68
     4.8    9.98       5    9.98     5.3   11.58     5.3   12.68     5.8   12.68
     5.8   13.23     6.6   13.23    16.6   13.23
#Mann= 3 , 0 , 0
     -10    .015       0      .8    .015       0     5.8    .015       0
#XS Ineff= 2 , 0
              .8   13.23     5.8           13.23
Permanent Ineff=
       F       F
Bank Sta=.8,5.8
XS Rating Curve= 0
Exp/Cntr=.3,.1

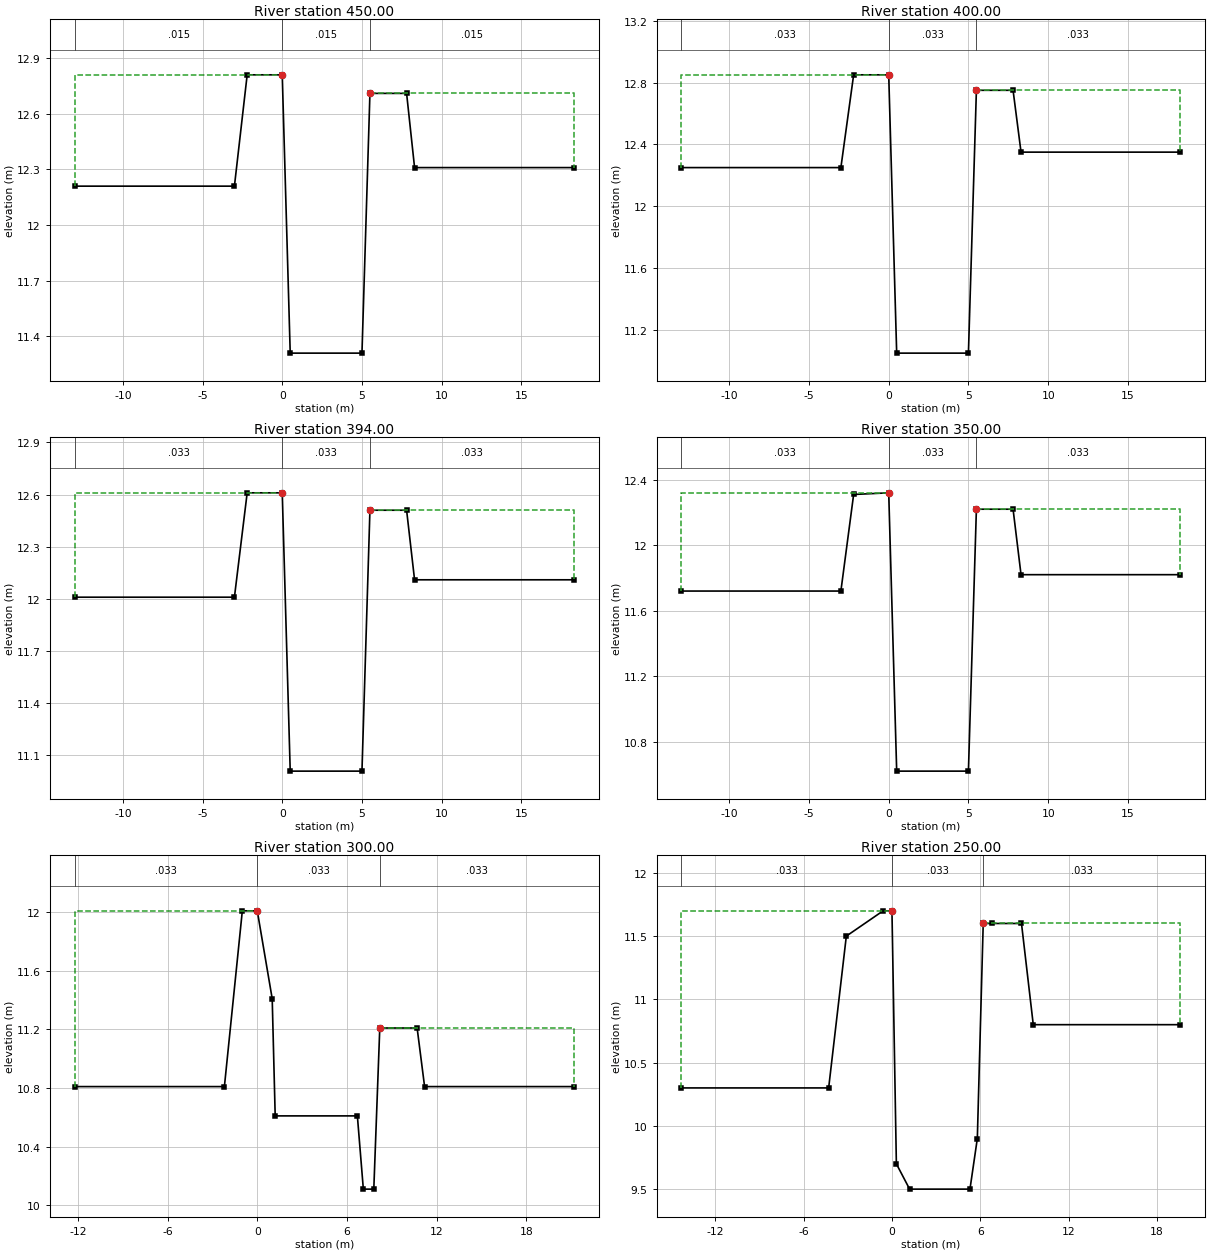
Type RM Length L Ch R = 1 ,450.00  ,50,50,50
BEGIN DESCRIPTION:
9
END DESCRIPTION:
#Sta/Elev= 10
     -13   12.21      -3   12.21    -2.2   12.81       0   12.81      .5   11.31
       5   11.31     5.5   12.71     7.8   12.71     8.3   12.31    18.3   12.31
#Mann= 3 , 0 , 0
     -13    .015       0       0    .015       0     5.5    .015       0
#XS Ineff= 2 , 0
               0   12.81     5.5           12.71
Permanent Ineff=
       F       F
Bank Sta=0,5.5
XS Rating Curve= 0
Exp/Cntr=.3,.1

Type RM Length L Ch R = 1 ,400.00  ,6,6,6
BEGIN DESCRIPTION:
8
END DESCRIPTION:
#Sta/Elev= 10
     -13   12.25      -3   12.25    -2.2   12.85       0   12.85      .5   11.05
       5   11.05     5.5   12.75     7.8   12.75     8.3   12.35    18.3   12.35
#Mann= 3 , 0 , 0
     -13    .033       0       0    .033       0     5.5    .033       0
#XS Ineff= 2 , 0
               0   12.85     5.5           12.75
Permanent Ineff=
       F       F
Bank Sta=0,5.5
XS Rating Curve= 0
Exp/Cntr=.3,.1

Type RM Length L Ch R = 1 ,394.00  ,44,44,44
BEGIN DESCRIPTION:
7.044
END DESCRIPTION:
#Sta/Elev= 10
     -13   12.01      -3   12.01    -2.2   12.61       0   12.61      .5   11.01
       5   11.01     5.5   12.51     7.8   12.51     8.3   12.11    18.3   12.11
#Mann= 3 , 0 , 0
     -13    .033       0       0    .033       0     5.5    .033       0
#XS Ineff= 2 , 0
               0   12.61     5.5           12.51
Permanent Ineff=
       F       F
Bank Sta=0,5.5
XS Rating Curve= 0
Exp/Cntr=.3,.1

Type RM Length L Ch R = 1 ,350.00  ,50,50,50
BEGIN DESCRIPTION:
7
END DESCRIPTION:
#Sta/Elev= 10
     -13   11.72      -3   11.72    -2.2   12.31       0   12.32      .5   10.62
       5   10.62     5.5   12.22     7.8   12.22     8.3   11.82    18.3   11.82
#Mann= 3 , 0 , 0
     -13    .033       0       0    .033       0     5.5    .033       0
#XS Ineff= 2 , 0
               0   12.32     5.5           12.22
Permanent Ineff=
       F       F
Bank Sta=0,5.5
XS Rating Curve= 0
Exp/Cntr=.3,.1

Type RM Length L Ch R = 1 ,300.00  ,50,50,50
BEGIN DESCRIPTION:
6
END DESCRIPTION:
#Sta/Elev= 13
   -12.2   10.81    -2.2   10.81      -1   12.01       0   12.01       1   11.41
     1.2   10.61     6.7   10.61     7.1   10.11     7.8   10.11     8.2   11.21
    10.7   11.21    11.2   10.81    21.2   10.81
#Mann= 3 , 0 , 0
   -12.2    .033       0       0    .033       0     8.2    .033       0
#XS Ineff= 2 , 0
               0   12.01     8.2           11.21
Permanent Ineff=
       F       F
Bank Sta=0,8.2
XS Rating Curve= 0
Exp/Cntr=.3,.1

Type RM Length L Ch R = 1 ,250.00  ,50,50,50
BEGIN DESCRIPTION:
5
END DESCRIPTION:
#Sta/Elev= 14
   -14.3    10.3    -4.3    10.3    -3.1    11.5     -.6    11.7       0    11.7
      .3     9.7     1.2     9.5     5.3     9.5     5.8     9.9     6.2    11.6
     6.8    11.6     8.8    11.6     9.6    10.8    19.6    10.8
#Mann= 3 , 0 , 0
   -14.3    .033       0       0    .033       0     6.2    .033       0
#XS Ineff= 2 , 0
               0    11.7     6.2            11.6
Permanent Ineff=
       F       F
Bank Sta=0,6.2
XS Rating Curve= 0
Exp/Cntr=.3,.1

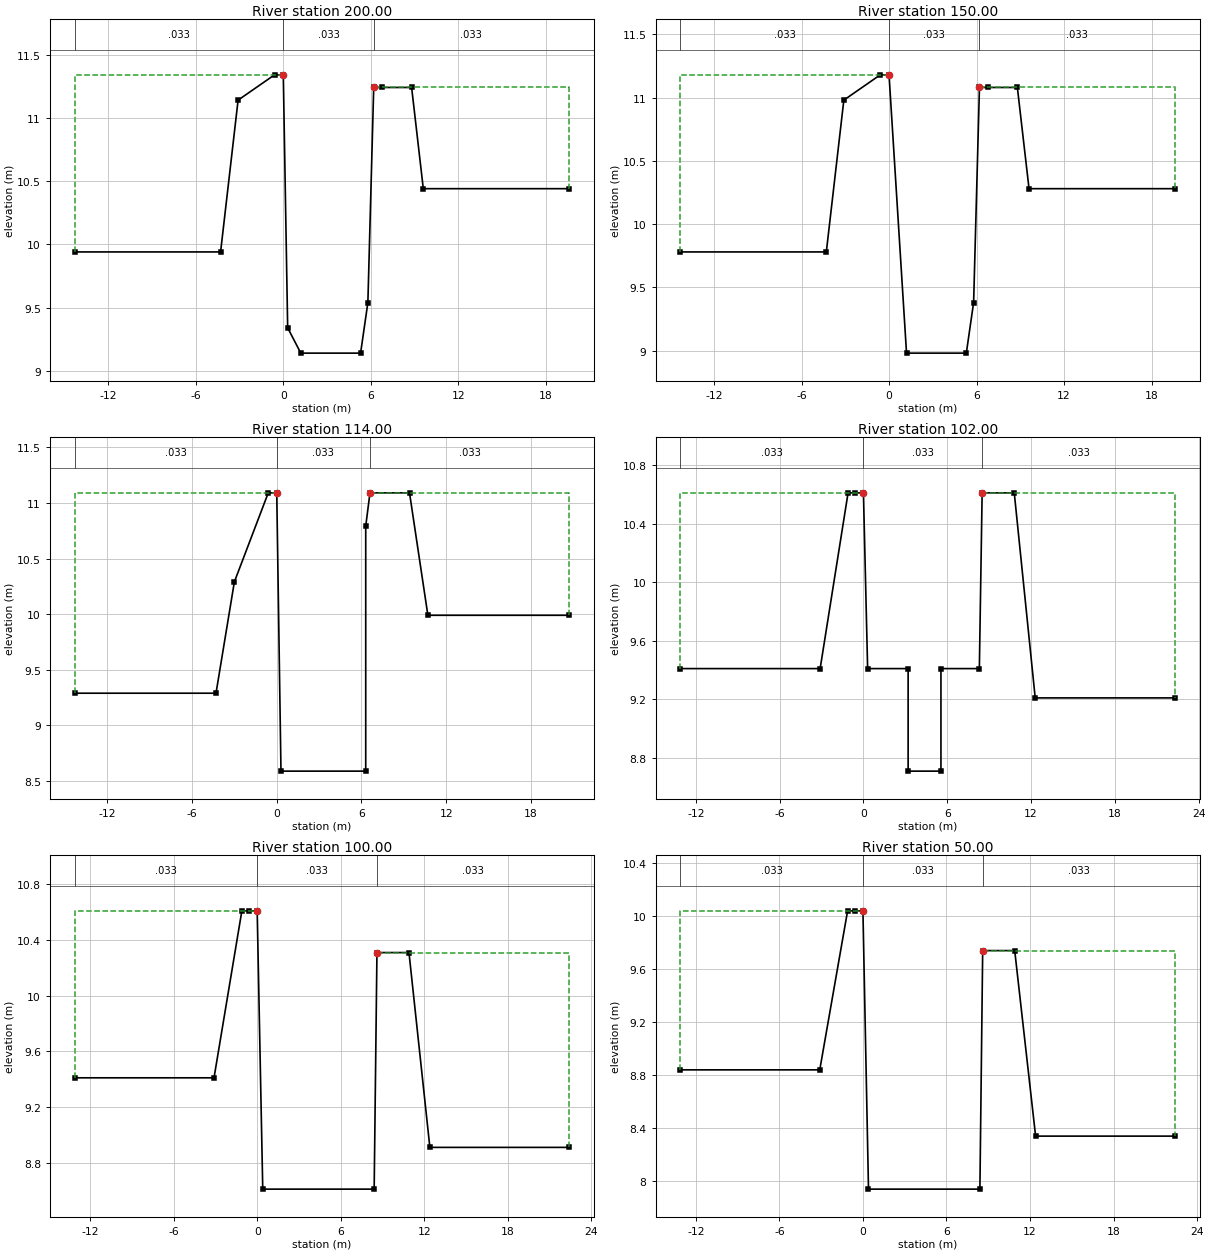
Type RM Length L Ch R = 1 ,200.00  ,50,50,50
BEGIN DESCRIPTION:
4
END DESCRIPTION:
#Sta/Elev= 14
   -14.3    9.94    -4.3    9.94    -3.1   11.14     -.6   11.34       0   11.34
      .3    9.34     1.2    9.14     5.3    9.14     5.8    9.54     6.2   11.24
     6.8   11.24     8.8   11.24     9.6   10.44    19.6   10.44
#Mann= 3 , 0 , 0
   -14.3    .033       0       0    .033       0     6.2    .033       0
#XS Ineff= 2 , 0
               0   11.34     6.2           11.24
Permanent Ineff=
       F       F
Bank Sta=0,6.2
XS Rating Curve= 0
Exp/Cntr=.3,.1

Type RM Length L Ch R = 1 ,150.00  ,36,36,36
BEGIN DESCRIPTION:
3
END DESCRIPTION:
#Sta/Elev= 13
   -14.3    9.78    -4.3    9.78    -3.1   10.98     -.6   11.18       0   11.18
     1.2    8.98     5.3    8.98     5.8    9.38     6.2   11.08     6.8   11.08
     8.8   11.08     9.6   10.28    19.6   10.28
#Mann= 3 , 0 , 0
   -14.3    .033       0       0    .033       0     6.2    .033       0
#XS Ineff= 2 , 0
               0   11.18     6.2           11.08
Permanent Ineff=
       F       F
Bank Sta=0,6.2
XS Rating Curve= 0
Exp/Cntr=.3,.1

Type RM Length L Ch R = 1 ,114.00  ,12,12,12
BEGIN DESCRIPTION:
2.014
END DESCRIPTION:
#Sta/Elev= 12
   -14.3    9.29    -4.3    9.29      -3   10.29     -.6   11.09       0   11.09
      .3    8.59     6.3    8.59     6.3   10.79     6.6   11.09     9.4   11.09
    10.7    9.99    20.7    9.99
#Mann= 3 , 0 , 0
   -14.3    .033       0       0    .033       0     6.6    .033       0
#XS Ineff= 2 , 0
               0   11.09     6.6           11.09
Permanent Ineff=
       F       F
Bank Sta=0,6.6
XS Rating Curve= 0
Exp/Cntr=.3,.1

Type RM Length L Ch R = 1 ,102.00  ,2,2,2
BEGIN DESCRIPTION:
2.002
END DESCRIPTION:
#Sta/Elev= 15
   -13.1    9.41    -3.1    9.41    -1.1   10.61     -.6   10.61       0   10.61
      .3    9.41     3.2    9.41     3.2    8.71    5.55    8.71    5.55    9.41
     8.3    9.41     8.5   10.61    10.8   10.61    12.3    9.21    22.3    9.21
#Mann= 3 , 0 , 0
   -13.1    .033       0       0    .033       0     8.5    .033       0
#XS Ineff= 2 , 0
               0   10.61     8.5           10.61
Permanent Ineff=
       F       F
Bank Sta=0,8.5
XS Rating Curve= 0
Exp/Cntr=.3,.1

Type RM Length L Ch R = 1 ,100.00  ,50,50,50
BEGIN DESCRIPTION:
2
END DESCRIPTION:
#Sta/Elev= 11
   -13.1    9.41    -3.1    9.41    -1.1   10.61     -.6   10.61       0   10.61
      .4    8.61     8.4    8.61     8.6   10.31    10.9   10.31    12.4    8.91
    22.4    8.91
#Mann= 3 , 0 , 0
   -13.1    .033       0       0    .033       0     8.6    .033       0
#XS Ineff= 2 , 0
               0   10.61     8.6           10.31
Permanent Ineff=
       F       F
Bank Sta=0,8.6
XS Rating Curve= 0
Exp/Cntr=.3,.1

Type RM Length L Ch R = 1 ,50.00   ,44,44,44
BEGIN DESCRIPTION:
1
END DESCRIPTION:
#Sta/Elev= 11
   -13.1    8.84    -3.1    8.84    -1.1   10.04     -.6   10.04       0   10.04
      .4    7.94     8.4    7.94     8.6    9.74    10.9    9.74    12.4    8.34
    22.4    8.34
#Mann= 3 , 0 , 0
   -13.1    .033       0       0    .033       0     8.6    .033       0
#XS Ineff= 2 , 0
               0   10.04     8.6            9.74
Permanent Ineff=
       F       F
Bank Sta=0,8.6
XS Rating Curve= 0
Exp/Cntr=.3,.1

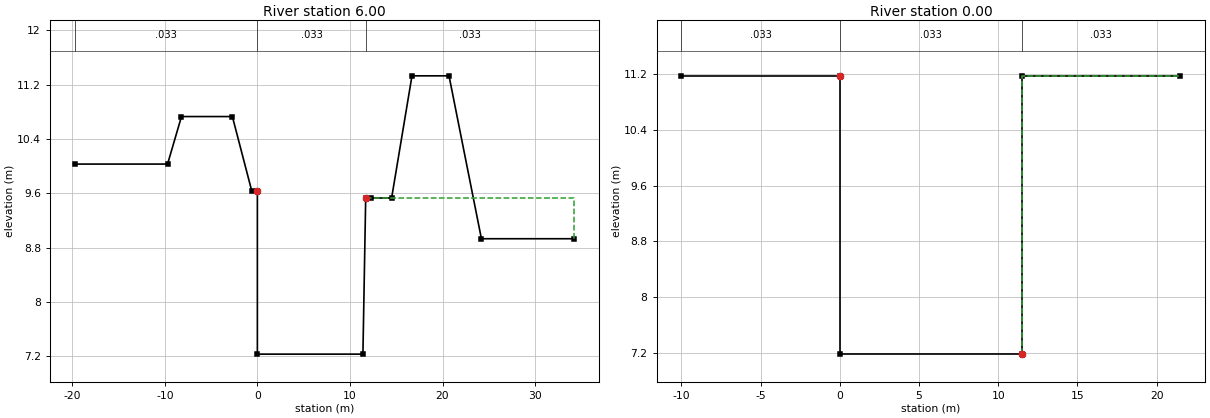
Type RM Length L Ch R = 1 ,6.00    ,6,6,6
BEGIN DESCRIPTION:
0.006
END DESCRIPTION:
#Sta/Elev= 15
   -19.7   10.03    -9.7   10.03    -8.2   10.73    -2.7   10.73     -.6    9.63
       0    9.63       0    7.23    11.4    7.23    11.7    9.53    12.3    9.53
    14.5    9.53    16.7   11.33    20.7   11.33    24.2    8.93    34.2    8.93
#Mann= 3 , 0 , 0
   -19.7    .033       0       0    .033       0    11.7    .033       0
#XS Ineff= 2 , 0
               0    9.63    11.7            9.53
Permanent Ineff=
       F       F
Bank Sta=0,11.7
XS Rating Curve= 0
Exp/Cntr=.3,.1

Type RM Length L Ch R = 1 ,0.00    ,0,0,0
BEGIN DESCRIPTION:
0
END DESCRIPTION:
#Sta/Elev= 6
     -10   11.18       0   11.18       0    7.18    11.5    7.18    11.5   11.18
    21.5   11.18
#Mann= 3 , 0 , 0
     -10    .033       0       0    .033       0    11.5    .033       0
#XS Ineff= 2 , 0
               0   11.18    11.5           11.18
Permanent Ineff=
       F       F
Bank Sta=0,11.5
XS Rating Curve= 0
Exp/Cntr=.3,.1

Chan Stop Cuts=-1