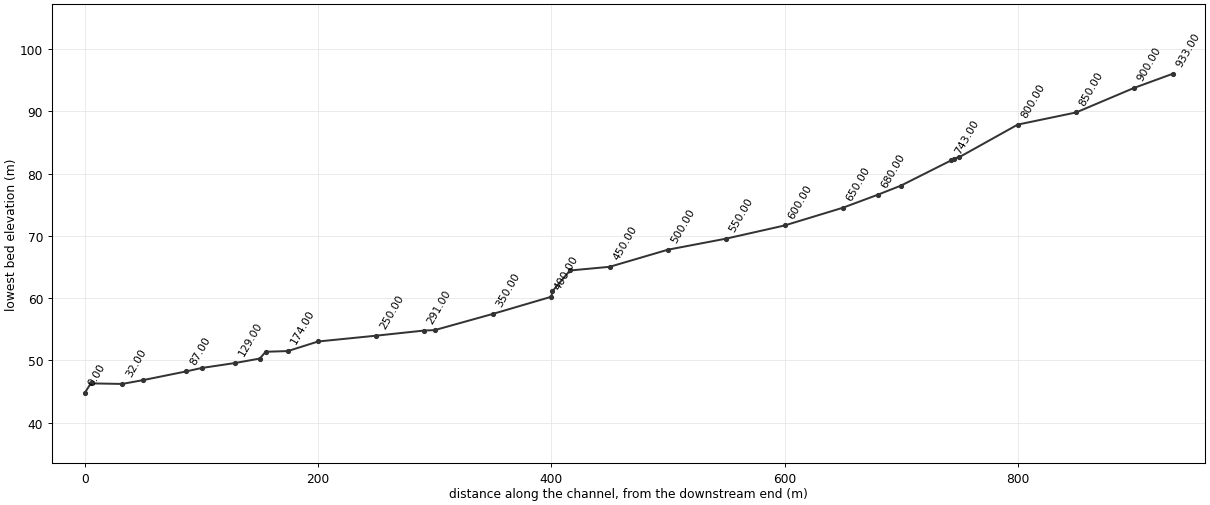
--- ICC.prj (project) ---

Proj Title=ICC
Current Plan=p01
Default Exp/Contr=.3,.1
SI Units
Geom File=g01
Flow File=f01
Plan File=p01
Y Axis Title=Elevation
X Axis Title(PF)=Main Channel Distance
X Axis Title(XS)=Station
BEGIN DESCRIPTION:
           BACK WATER COMPUTATION
      APPLICATION OF HEC-2 BY Samju Construction Engineering
      ICHUN-STREEM : 30 YR
END DESCRIPTION:
DSS Export Rating Curves= 0
DSS Export Rating Curve Sorted= 0
DSS Export Volume Flow Curves= 0
DXF OffsetX= 0
DXF OffsetY= 0
DXF ScaleX= 1
DXF ScaleY= 10

--- ICC.p01 (plan) ---

Plan Title=Imported Plan 01
Version=Version 3.0.1  Mar 2001
Short Identifier=Imported Pla
Geom File=g01
Flow File=f01
Subcritical Flow
K Sum by GR= 0
Std Step Tol= 0.003
Critical Tol= 0.003
Num of Std Step Trials= 20
Max Error Tol= 0.1
Flow Tol Ratio= 0.001
Split Flow NTrial= 30
Split Flow Tol= 0.02
Split Flow Ratio= 0.02
Log Output Level= 0
Friction Slope Method= 1
Unsteady Friction Slope Method= 2
Parabolic Critical Depth
Global Vel Dist= 0 , 0 , 0
Global Log Level= 0
CheckData=True
Encroach Param=-1 ,0,0, 0
Computation Interval=1HOUR
Output Interval=1HOUR
Run HTab= 0
Run UNet= 0
Run PostProcess= 0
UNET Theta= 1
UNET ZTol= 0.02
UNET ZSATol= 0.1
UNET MxIter= 20
UNET MaxInSteps= 20
UNET DtIC= 0
UNET DtMin= 0
UNET MaxCRTS= 20
UNET WFStab= 2
UNET SFStab= 1
UNET WFX= 1
UNET SFX= 1
UNET Convert EG Bridges=-1
UNET Use Existing IB Tables=-1
Instantaneous Interval=1HOUR
Write IC File= 0
Write Velocity= 0
Write Detailed= 0

--- ICC.f01 (steady flow) ---

Flow Title=Imported Flow 01
Version=Version 3.0.1  Mar 2001
Number of Profiles= 5
Profile Names=10YR,20YR,30YR,50YR,80YR
River Rch & RM=RIVER-1,Reach-1         ,18.033
    5.82    6.41    6.76    7.19    7.59
River Rch & RM=ICHUN,ICHUN           ,933.00
    5.82    6.41    6.76    7.19    7.59
Boundary for River Rch & Prof#=ICHUN,ICHUN           , 1
Up Type= 0
Dn Type= 3
Dn Slope=.028
Boundary for River Rch & Prof#=ICHUN,ICHUN           , 2
Up Type= 0
Dn Type= 3
Dn Slope=.028
Boundary for River Rch & Prof#=ICHUN,ICHUN           , 3
Up Type= 0
Dn Type= 3
Dn Slope=.028
Boundary for River Rch & Prof#=ICHUN,ICHUN           , 4
Up Type= 0
Dn Type= 3
Dn Slope=.028
Boundary for River Rch & Prof#=ICHUN,ICHUN           , 5
Up Type= 0
Dn Type= 3
Dn Slope=.028
DSS Import GetInterval= 0
DSS Import GetPeak= 0
DSS Import FillOption= 0

--- ICC.g01 (geometry) ---

Geom Title=Imported Geom 01
Version=Version 3.0.1  Mar 2001

River Reach=ICHUN           ,ICHUN
Reach XY= 2
              .5             .95              .5             .05

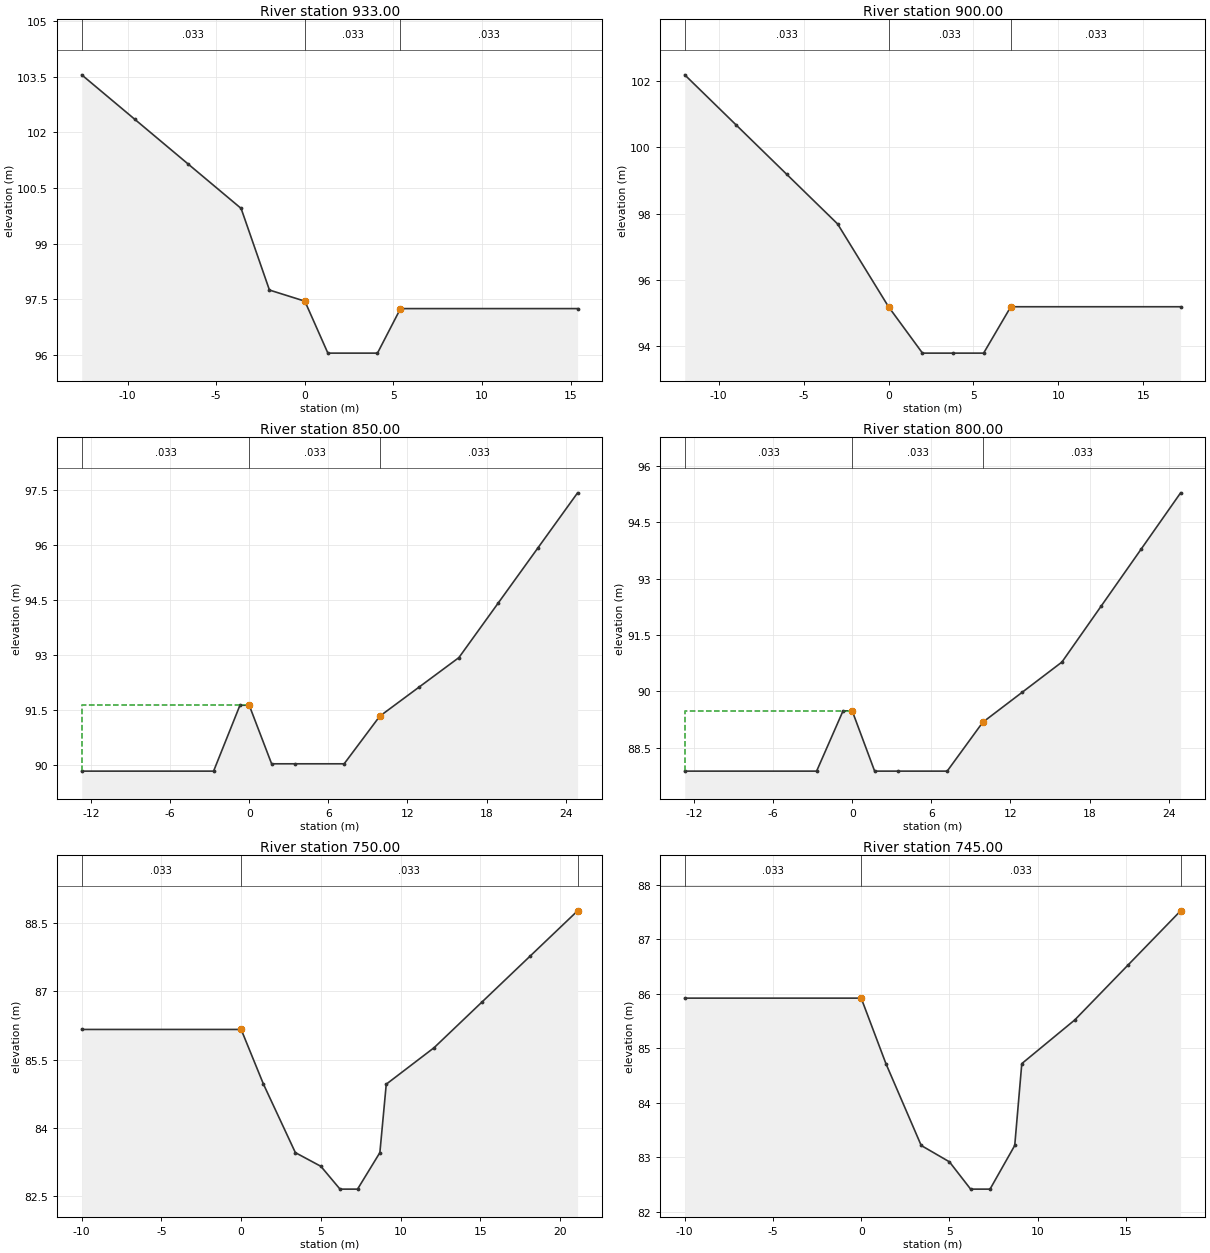
Type RM Length L Ch R = 1 ,933.00  ,33,33,33
BEGIN DESCRIPTION:
18.033
END DESCRIPTION:
#Sta/Elev= 10
   -12.6  103.55    -9.6  102.35    -6.6  101.15    -3.6   99.95      -2   97.75
       0   97.45     1.3   96.05     4.1   96.05     5.4   97.25    15.4   97.25
#Mann= 3 , 0 , 0
   -12.6    .033       0       0    .033       0     5.4    .033       0
#XS Ineff= 2 , 0
               0   97.45     5.4           97.25
Permanent Ineff=
       F       F
Bank Sta=0,5.4
XS Rating Curve= 0
Exp/Cntr=.3,.1

Type RM Length L Ch R = 1 ,900.00  ,50,50,50
BEGIN DESCRIPTION:
18
END DESCRIPTION:
#Sta/Elev= 10
     -12  102.19      -9  100.69      -6   99.19      -3   97.69       0   95.19
       2   93.79     3.8   93.79     5.6   93.79     7.2   95.19    17.2   95.19
#Mann= 3 , 0 , 0
     -12    .033       0       0    .033       0     7.2    .033       0
#XS Ineff= 2 , 0
               0   95.19     7.2           95.19
Permanent Ineff=
       F       F
Bank Sta=0,7.2
XS Rating Curve= 0
Exp/Cntr=.3,.1

Type RM Length L Ch R = 1 ,850.00  ,50,50,50
BEGIN DESCRIPTION:
17
END DESCRIPTION:
#Sta/Elev= 13
   -12.7   89.83    -2.7   89.83     -.7   91.63       0   91.63     1.7   90.03
     3.5   90.03     7.2   90.03     9.9   91.33    12.9   92.13    15.9   92.93
    18.9   94.43    21.9   95.93    24.9   97.43
#Mann= 3 , 0 , 0
   -12.7    .033       0       0    .033       0     9.9    .033       0
#XS Ineff= 2 , 0
               0   91.63     9.9           91.33
Permanent Ineff=
       F       F
Bank Sta=0,9.9
XS Rating Curve= 0
Exp/Cntr=.3,.1

Type RM Length L Ch R = 1 ,800.00  ,50,50,50
BEGIN DESCRIPTION:
16
END DESCRIPTION:
#Sta/Elev= 13
   -12.7   87.88    -2.7   87.88     -.7   89.48       0   89.48     1.7   87.88
     3.5   87.88     7.2   87.88     9.9   89.18    12.9   89.98    15.9   90.78
    18.9   92.28    21.9   93.78    24.9   95.28
#Mann= 3 , 0 , 0
   -12.7    .033       0       0    .033       0     9.9    .033       0
#XS Ineff= 2 , 0
               0   89.48     9.9           89.18
Permanent Ineff=
       F       F
Bank Sta=0,9.9
XS Rating Curve= 0
Exp/Cntr=.3,.1

Type RM Length L Ch R = 1 ,750.00  ,5,5,5
BEGIN DESCRIPTION:
15
END DESCRIPTION:
#Sta/Elev= 13
     -10   86.16       0   86.16     1.4   84.96     3.4   83.46       5   83.16
     6.2   82.66     7.3   82.66     8.7   83.46     9.1   84.96    12.1   85.76
    15.1   86.76    18.1   87.76    21.1   88.76
#Mann= 3 , 0 , 0
     -10    .033       0       0    .033       0    21.1    .033       0
#XS Ineff= 2 , 0
               0   86.16    21.1           88.76
Permanent Ineff=
       F       F
Bank Sta=0,21.1
XS Rating Curve= 0
Exp/Cntr=.3,.1

Type RM Length L Ch R = 1 ,745.00  ,2,2,2
BEGIN DESCRIPTION:
14.045
END DESCRIPTION:
#Sta/Elev= 12
     -10   85.92       0   85.92     1.4   84.72     3.4   83.22       5   82.92
     6.2   82.42     7.3   82.42     8.7   83.22     9.1   84.72    12.1   85.52
    15.1   86.52    18.1   87.52
#Mann= 3 , 0 , 0
     -10    .033       0       0    .033       0    18.1    .033       0
#XS Ineff= 2 , 0
               0   85.92    18.1           87.52
Permanent Ineff=
       F       F
Bank Sta=0,18.1
XS Rating Curve= 0
Exp/Cntr=.3,.1

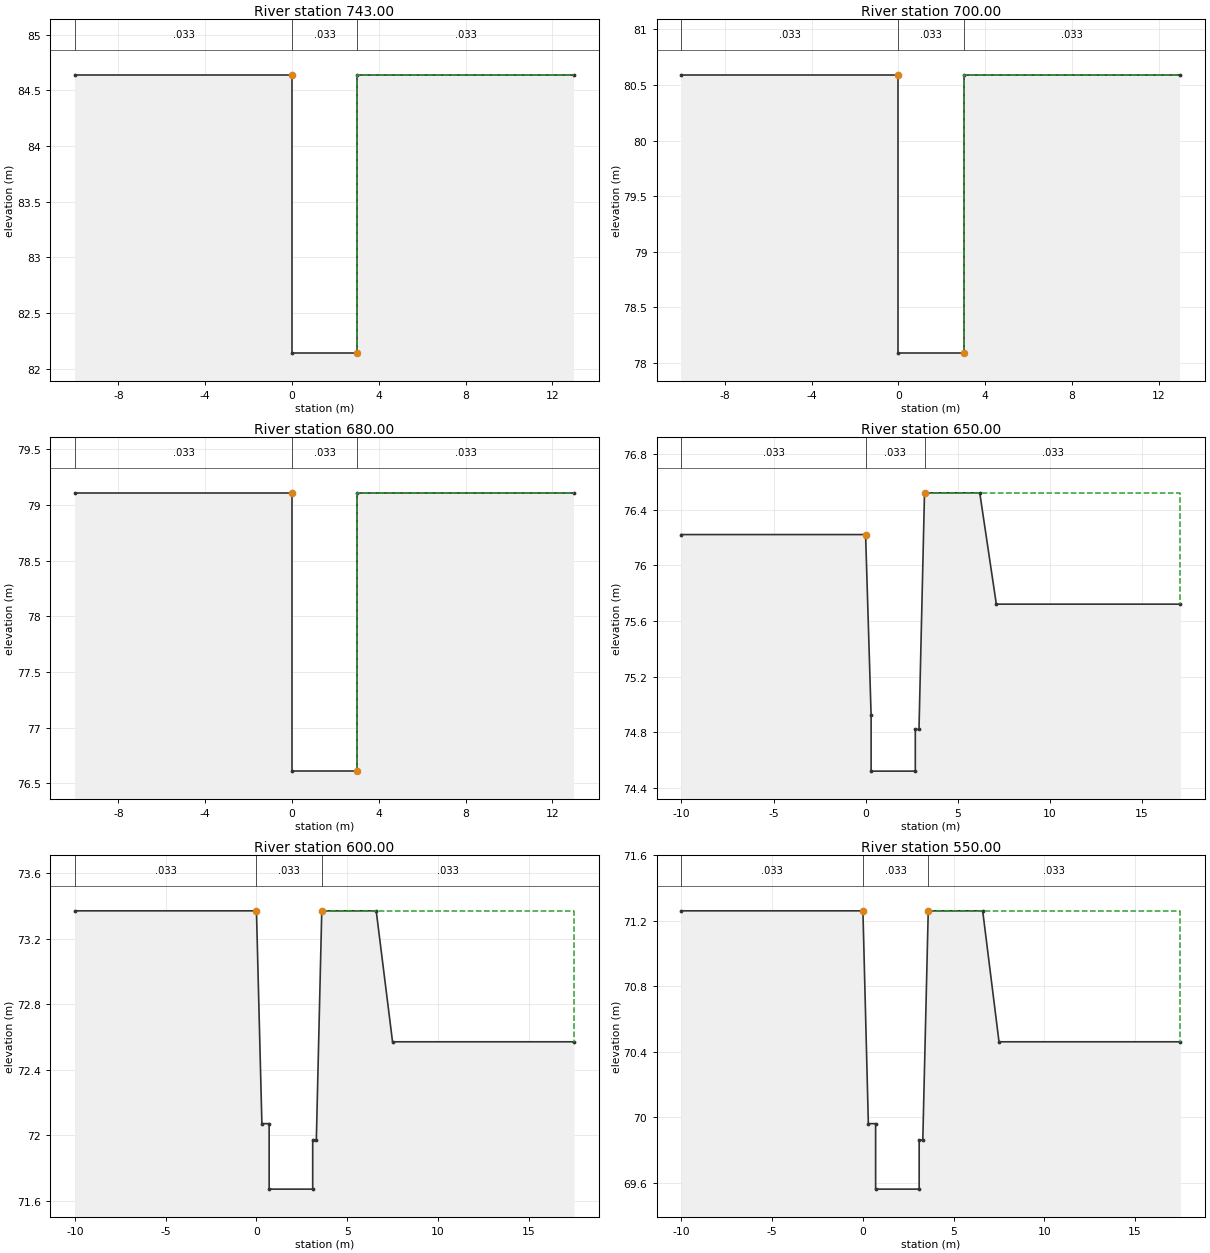
Type RM Length L Ch R = 1 ,743.00  ,43,43,43
BEGIN DESCRIPTION:
14.043
END DESCRIPTION:
#Sta/Elev= 6
     -10   84.64       0   84.64       0   82.14       3   82.14       3   84.64
      13   84.64
#Mann= 3 , 0 , 0
     -10    .033       0       0    .033       0       3    .033       0
#XS Ineff= 2 , 0
               0   84.64       3           84.64
Permanent Ineff=
       F       F
Bank Sta=0,3
XS Rating Curve= 0
Exp/Cntr=.3,.1

Type RM Length L Ch R = 1 ,700.00  ,20,20,20
BEGIN DESCRIPTION:
14
END DESCRIPTION:
#Sta/Elev= 6
     -10   80.59       0   80.59       0   78.09       3   78.09       3   80.59
      13   80.59
#Mann= 3 , 0 , 0
     -10    .033       0       0    .033       0       3    .033       0
#XS Ineff= 2 , 0
               0   80.59       3           80.59
Permanent Ineff=
       F       F
Bank Sta=0,3
XS Rating Curve= 0
Exp/Cntr=.3,.1

Type RM Length L Ch R = 1 ,680.00  ,30,30,30
BEGIN DESCRIPTION:
13.03
END DESCRIPTION:
#Sta/Elev= 6
     -10   79.11       0   79.11       0   76.61       3   76.61       3   79.11
      13   79.11
#Mann= 3 , 0 , 0
     -10    .033       0       0    .033       0       3    .033       0
#XS Ineff= 2 , 0
               0   79.11       3           79.11
Permanent Ineff=
       F       F
Bank Sta=0,3
XS Rating Curve= 0
Exp/Cntr=.3,.1

Type RM Length L Ch R = 1 ,650.00  ,50,50,50
BEGIN DESCRIPTION:
13
END DESCRIPTION:
#Sta/Elev= 11
     -10   76.22       0   76.22      .3   74.92      .3   74.52     2.7   74.52
     2.7   74.82     2.9   74.82     3.2   76.52     6.2   76.52     7.1   75.72
    17.1   75.72
#Mann= 3 , 0 , 0
     -10    .033       0       0    .033       0     3.2    .033       0
#XS Ineff= 2 , 0
               0   76.22     3.2           76.52
Permanent Ineff=
       F       F
Bank Sta=0,3.2
XS Rating Curve= 0
Exp/Cntr=.3,.1

Type RM Length L Ch R = 1 ,600.00  ,50,50,50
BEGIN DESCRIPTION:
12
END DESCRIPTION:
#Sta/Elev= 12
     -10   73.37       0   73.37      .3   72.07      .7   72.07      .7   71.67
     3.1   71.67     3.1   71.97     3.3   71.97     3.6   73.37     6.6   73.37
     7.5   72.57    17.5   72.57
#Mann= 3 , 0 , 0
     -10    .033       0       0    .033       0     3.6    .033       0
#XS Ineff= 2 , 0
               0   73.37     3.6           73.37
Permanent Ineff=
       F       F
Bank Sta=0,3.6
XS Rating Curve= 0
Exp/Cntr=.3,.1

Type RM Length L Ch R = 1 ,550.00  ,50,50,50
BEGIN DESCRIPTION:
11
END DESCRIPTION:
#Sta/Elev= 12
     -10   71.26       0   71.26      .3   69.96      .7   69.96      .7   69.56
     3.1   69.56     3.1   69.86     3.3   69.86     3.6   71.26     6.6   71.26
     7.5   70.46    17.5   70.46
#Mann= 3 , 0 , 0
     -10    .033       0       0    .033       0     3.6    .033       0
#XS Ineff= 2 , 0
               0   71.26     3.6           71.26
Permanent Ineff=
       F       F
Bank Sta=0,3.6
XS Rating Curve= 0
Exp/Cntr=.3,.1

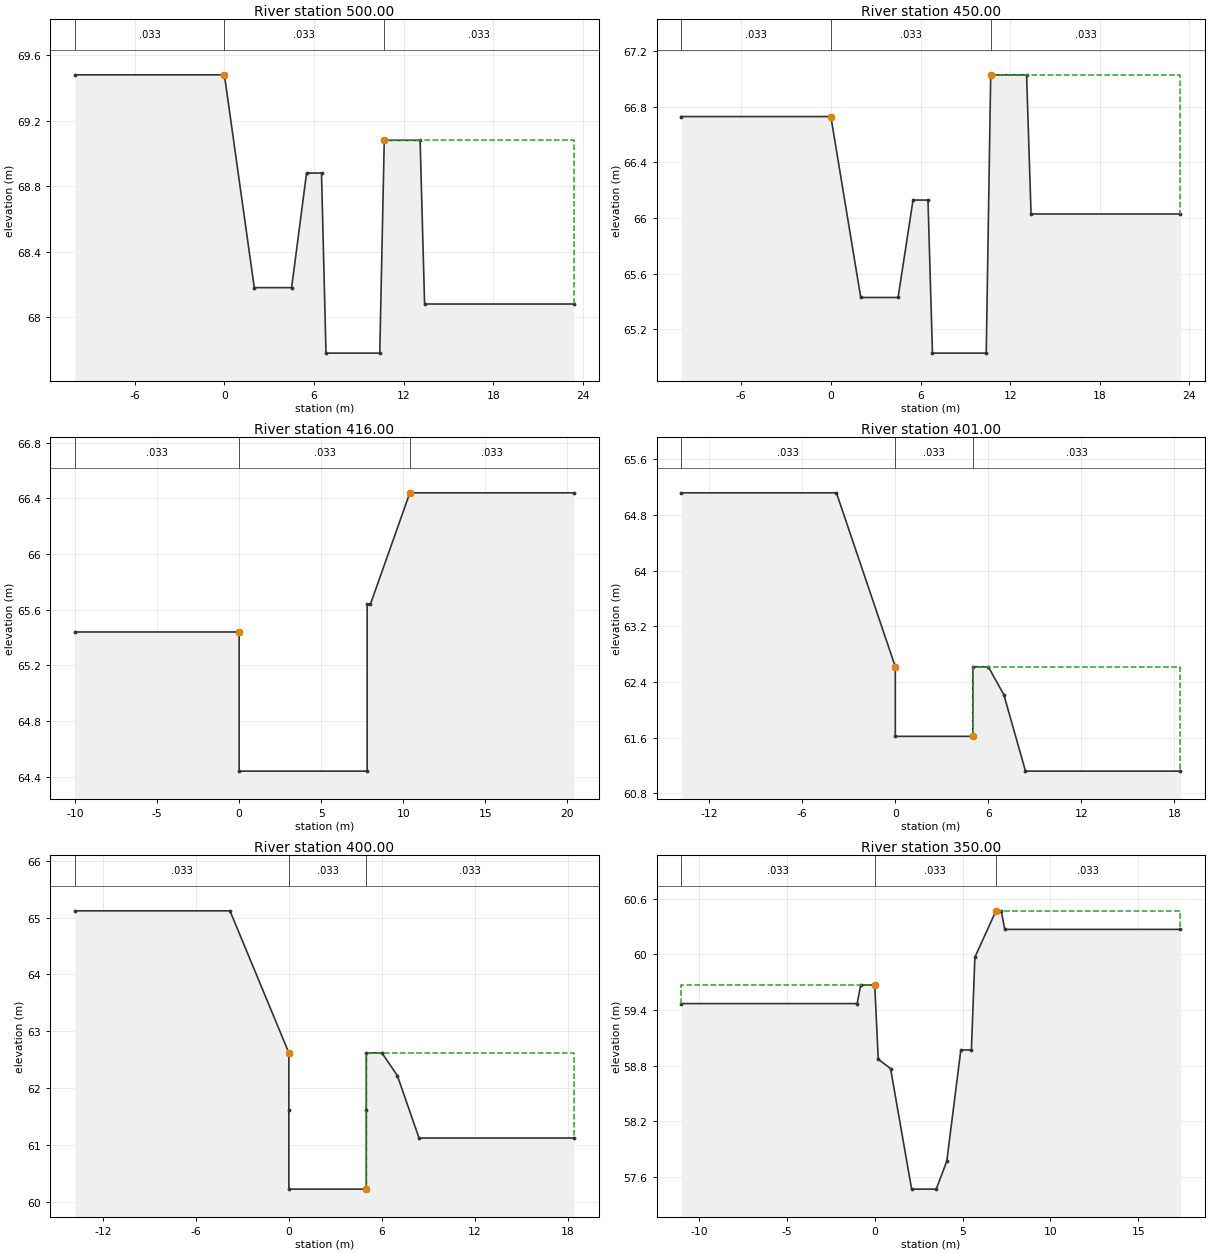
Type RM Length L Ch R = 1 ,500.00  ,50,50,50
BEGIN DESCRIPTION:
10
END DESCRIPTION:
#Sta/Elev= 12
     -10   69.48       0   69.48       2   68.18     4.5   68.18     5.5   68.88
     6.5   68.88     6.8   67.78    10.4   67.78    10.7   69.08    13.1   69.08
    13.4   68.08    23.4   68.08
#Mann= 3 , 0 , 0
     -10    .033       0       0    .033       0    10.7    .033       0
#XS Ineff= 2 , 0
               0   69.48    10.7           69.08
Permanent Ineff=
       F       F
Bank Sta=0,10.7
XS Rating Curve= 0
Exp/Cntr=.3,.1

Type RM Length L Ch R = 1 ,450.00  ,34,34,34
BEGIN DESCRIPTION:
9
END DESCRIPTION:
#Sta/Elev= 12
     -10   66.73       0   66.73       2   65.43     4.5   65.43     5.5   66.13
     6.5   66.13     6.8   65.03    10.4   65.03    10.7   67.03    13.1   67.03
    13.4   66.03    23.4   66.03
#Mann= 3 , 0 , 0
     -10    .033       0       0    .033       0    10.7    .033       0
#XS Ineff= 2 , 0
               0   66.73    10.7           67.03
Permanent Ineff=
       F       F
Bank Sta=0,10.7
XS Rating Curve= 0
Exp/Cntr=.3,.1

Type RM Length L Ch R = 1 ,416.00  ,15,15,15
BEGIN DESCRIPTION:
8.016
END DESCRIPTION:
#Sta/Elev= 8
     -10   65.44       0   65.44       0   64.44     7.8   64.44     7.8   65.64
       8   65.64    10.4   66.44    20.4   66.44
#Mann= 3 , 0 , 0
     -10    .033       0       0    .033       0    10.4    .033       0
#XS Ineff= 2 , 0
               0   65.44    10.4           66.44
Permanent Ineff=
       F       F
Bank Sta=0,10.4
XS Rating Curve= 0
Exp/Cntr=.3,.1

Type RM Length L Ch R = 1 ,401.00  ,1,1,1
BEGIN DESCRIPTION:
8.001
END DESCRIPTION:
#Sta/Elev= 10
   -13.8   65.12    -3.8   65.12       0   62.62       0   61.62       5   61.62
       5   62.62       6   62.62       7   62.22     8.4   61.12    18.4   61.12
#Mann= 3 , 0 , 0
   -13.8    .033       0       0    .033       0       5    .033       0
#XS Ineff= 2 , 0
               0   62.62       5           62.62
Permanent Ineff=
       F       F
Bank Sta=0,5
XS Rating Curve= 0
Exp/Cntr=.3,.1

Type RM Length L Ch R = 1 ,400.00  ,50,50,50
BEGIN DESCRIPTION:
8
END DESCRIPTION:
#Sta/Elev= 12
   -13.8   65.12    -3.8   65.12       0   62.62       0   61.62       0   60.22
       5   60.22       5   61.62       5   62.62       6   62.62       7   62.22
     8.4   61.12    18.4   61.12
#Mann= 3 , 0 , 0
   -13.8    .033       0       0    .033       0       5    .033       0
#XS Ineff= 2 , 0
               0   62.62       5           62.62
Permanent Ineff=
       F       F
Bank Sta=0,5
XS Rating Curve= 0
Exp/Cntr=.3,.1

Type RM Length L Ch R = 1 ,350.00  ,50,50,50
BEGIN DESCRIPTION:
7
END DESCRIPTION:
#Sta/Elev= 16
     -11   59.47      -1   59.47     -.8   59.67       0   59.67      .2   58.87
      .9   58.77     2.1   57.47     3.5   57.47     4.1   57.77     4.9   58.97
     5.5   58.97     5.7   59.97     6.9   60.47     7.2   60.47     7.4   60.27
    17.4   60.27
#Mann= 3 , 0 , 0
     -11    .033       0       0    .033       0     6.9    .033       0
#XS Ineff= 2 , 0
               0   59.67     6.9           60.47
Permanent Ineff=
       F       F
Bank Sta=0,6.9
XS Rating Curve= 0
Exp/Cntr=.3,.1

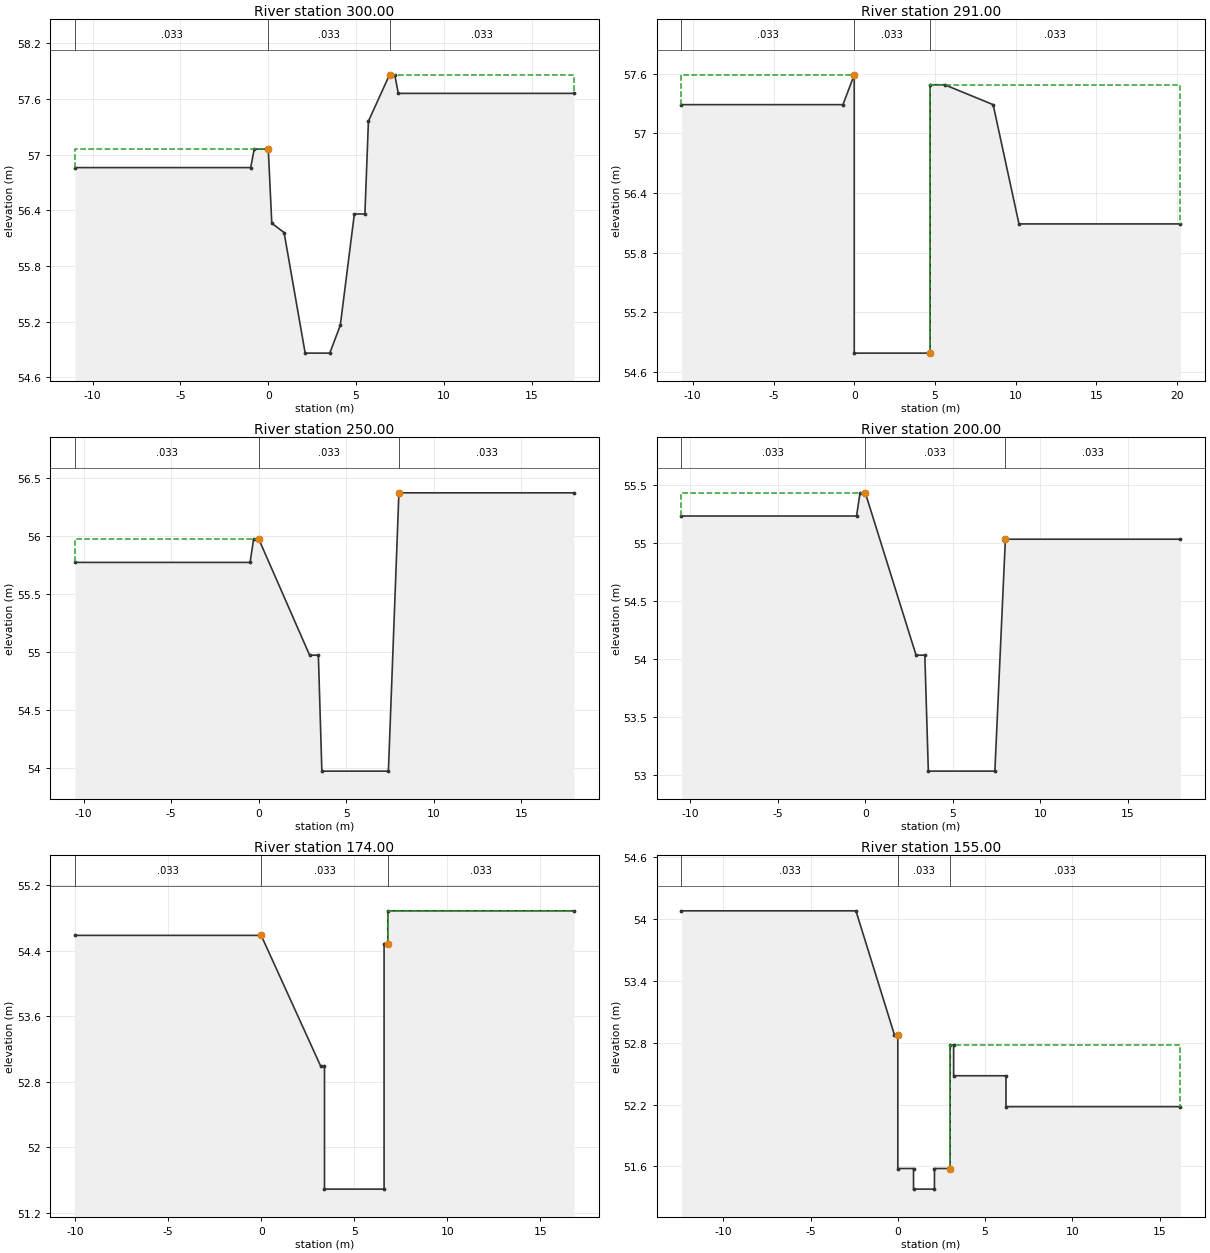
Type RM Length L Ch R = 1 ,300.00  ,9,9,9
BEGIN DESCRIPTION:
6
END DESCRIPTION:
#Sta/Elev= 16
     -11   56.86      -1   56.86     -.8   57.06       0   57.06      .2   56.26
      .9   56.16     2.1   54.86     3.5   54.86     4.1   55.16     4.9   56.36
     5.5   56.36     5.7   57.36     6.9   57.86     7.2   57.86     7.4   57.66
    17.4   57.66
#Mann= 3 , 0 , 0
     -11    .033       0       0    .033       0     6.9    .033       0
#XS Ineff= 2 , 0
               0   57.06     6.9           57.86
Permanent Ineff=
       F       F
Bank Sta=0,6.9
XS Rating Curve= 0
Exp/Cntr=.3,.1

Type RM Length L Ch R = 1 ,291.00  ,41,41,41
BEGIN DESCRIPTION:
5.041
END DESCRIPTION:
#Sta/Elev= 10
   -10.7   57.29     -.7   57.29       0   57.59       0   54.79     4.7   54.79
     4.7   57.49     5.6   57.49     8.6   57.29    10.2   56.09    20.2   56.09
#Mann= 3 , 0 , 0
   -10.7    .033       0       0    .033       0     4.7    .033       0
#XS Ineff= 2 , 0
               0   57.59     4.7           57.49
Permanent Ineff=
       F       F
Bank Sta=0,4.7
XS Rating Curve= 0
Exp/Cntr=.3,.1

Type RM Length L Ch R = 1 ,250.00  ,50,50,50
BEGIN DESCRIPTION:
5
END DESCRIPTION:
#Sta/Elev= 10
   -10.5   55.77     -.5   55.77     -.3   55.97       0   55.97     2.9   54.97
     3.4   54.97     3.6   53.97     7.4   53.97       8   56.37      18   56.37
#Mann= 3 , 0 , 0
   -10.5    .033       0       0    .033       0       8    .033       0
#XS Ineff= 2 , 0
               0   55.97       8           56.37
Permanent Ineff=
       F       F
Bank Sta=0,8
XS Rating Curve= 0
Exp/Cntr=.3,.1

Type RM Length L Ch R = 1 ,200.00  ,26,26,26
BEGIN DESCRIPTION:
4
END DESCRIPTION:
#Sta/Elev= 10
   -10.5   55.23     -.5   55.23     -.3   55.43       0   55.43     2.9   54.03
     3.4   54.03     3.6   53.03     7.4   53.03       8   55.03      18   55.03
#Mann= 3 , 0 , 0
   -10.5    .033       0       0    .033       0       8    .033       0
#XS Ineff= 2 , 0
               0   55.43       8           55.03
Permanent Ineff=
       F       F
Bank Sta=0,8
XS Rating Curve= 0
Exp/Cntr=.3,.1

Type RM Length L Ch R = 1 ,174.00  ,19,19,19
BEGIN DESCRIPTION:
3.024
END DESCRIPTION:
#Sta/Elev= 10
     -10   54.59       0   54.59     3.2   52.99     3.4   52.99     3.4   51.49
     6.6   51.49     6.6   54.49     6.8   54.49     6.8   54.89    16.8   54.89
#Mann= 3 , 0 , 0
     -10    .033       0       0    .033       0     6.8    .033       0
#XS Ineff= 2 , 0
               0   54.59     6.8           54.89
Permanent Ineff=
       F       F
Bank Sta=0,6.8
XS Rating Curve= 0
Exp/Cntr=.3,.1

Type RM Length L Ch R = 1 ,155.00  ,5,5,5
BEGIN DESCRIPTION:
3.005
END DESCRIPTION:
#Sta/Elev= 16
   -12.4   54.08    -2.4   54.08     -.2   52.88       0   52.88       0   51.58
      .9   51.58      .9   51.38     2.1   51.38     2.1   51.58       3   51.58
       3   52.78     3.2   52.78     3.2   52.48     6.2   52.48     6.2   52.18
    16.2   52.18
#Mann= 3 , 0 , 0
   -12.4    .033       0       0    .033       0       3    .033       0
#XS Ineff= 2 , 0
               0   52.88       3           52.78
Permanent Ineff=
       F       F
Bank Sta=0,3
XS Rating Curve= 0
Exp/Cntr=.3,.1

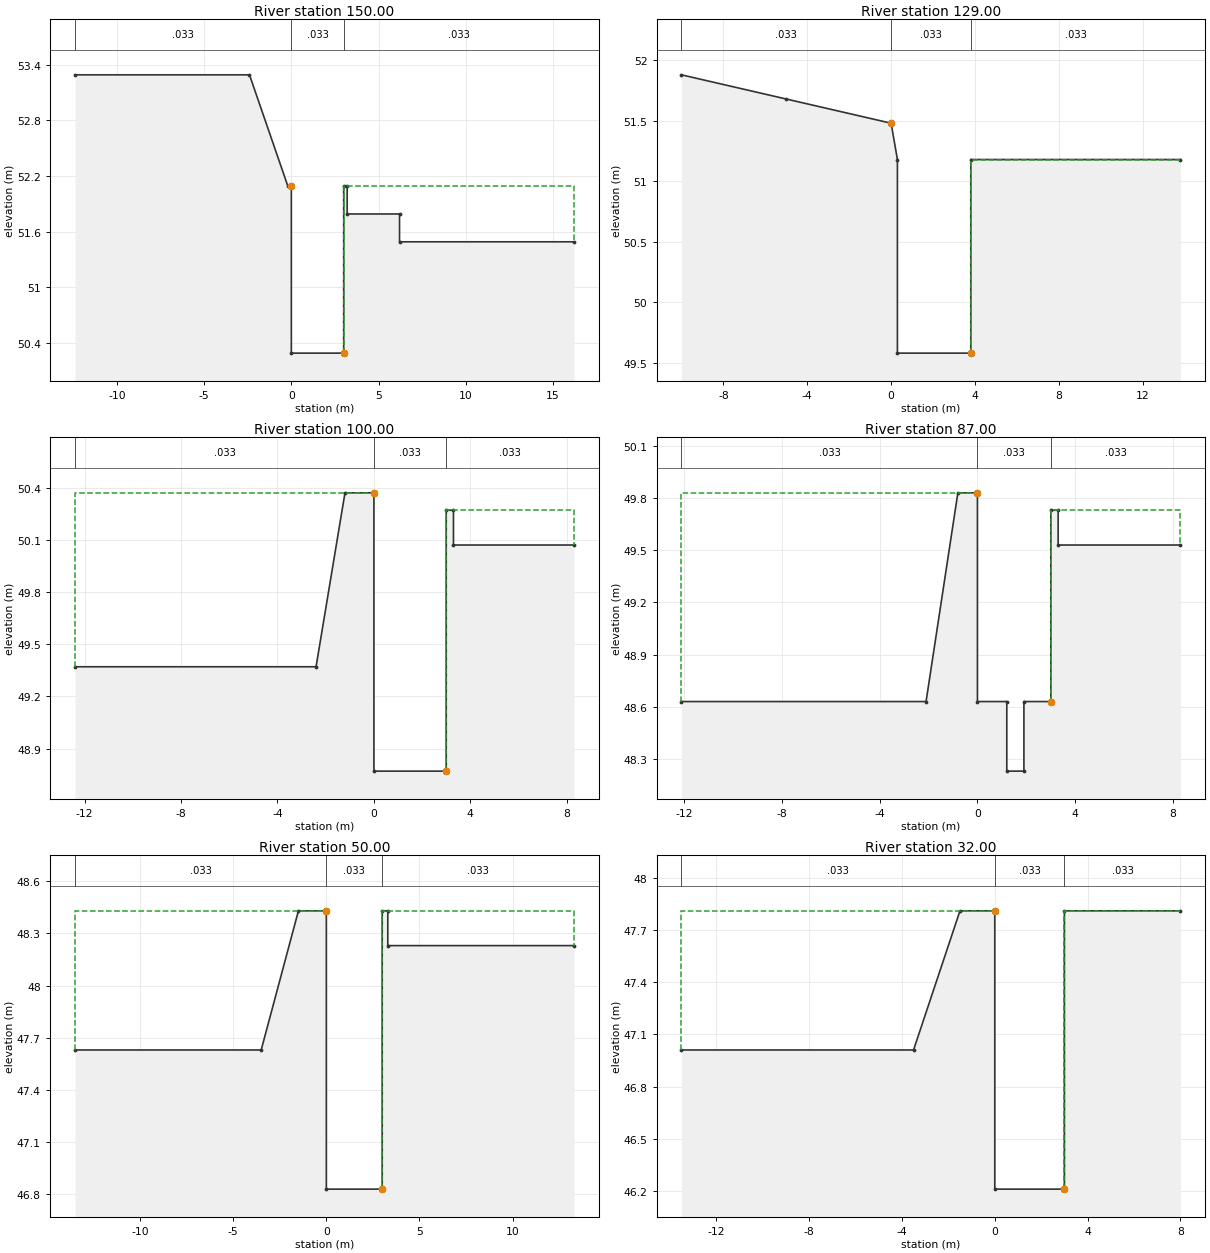
Type RM Length L Ch R = 1 ,150.00  ,21,21,21
BEGIN DESCRIPTION:
3
END DESCRIPTION:
#Sta/Elev= 12
   -12.4   53.29    -2.4   53.29     -.2   52.09       0   52.09       0   50.29
       3   50.29       3   52.09     3.2   52.09     3.2   51.79     6.2   51.79
     6.2   51.49    16.2   51.49
#Mann= 3 , 0 , 0
   -12.4    .033       0       0    .033       0       3    .033       0
#XS Ineff= 2 , 0
               0   52.09       3           52.09
Permanent Ineff=
       F       F
Bank Sta=0,3
XS Rating Curve= 0
Exp/Cntr=.3,.1

Type RM Length L Ch R = 1 ,129.00  ,29,29,29
BEGIN DESCRIPTION:
2.029
END DESCRIPTION:
#Sta/Elev= 8
     -10   51.88      -5   51.68       0   51.48      .3   51.18      .3   49.58
     3.8   49.58     3.8   51.18    13.8   51.18
#Mann= 3 , 0 , 0
     -10    .033       0       0    .033       0     3.8    .033       0
#XS Ineff= 2 , 0
               0   51.48     3.8           51.18
Permanent Ineff=
       F       F
Bank Sta=0,3.8
XS Rating Curve= 0
Exp/Cntr=.3,.1

Type RM Length L Ch R = 1 ,100.00  ,13,13,13
BEGIN DESCRIPTION:
2
END DESCRIPTION:
#Sta/Elev= 10
   -12.4   49.37    -2.4   49.37    -1.2   50.37       0   50.37       0   48.77
       3   48.77       3   50.27     3.3   50.27     3.3   50.07     8.3   50.07
#Mann= 3 , 0 , 0
   -12.4    .033       0       0    .033       0       3    .033       0
#XS Ineff= 2 , 0
               0   50.37       3           50.27
Permanent Ineff=
       F       F
Bank Sta=0,3
XS Rating Curve= 0
Exp/Cntr=.3,.1

Type RM Length L Ch R = 1 ,87.00   ,37,37,37
BEGIN DESCRIPTION:
1.037
END DESCRIPTION:
#Sta/Elev= 14
   -12.1   48.63    -2.1   48.63     -.8   49.83       0   49.83       0   48.63
     1.2   48.63     1.2   48.23     1.9   48.23     1.9   48.63       3   48.63
       3   49.73     3.3   49.73     3.3   49.53     8.3   49.53
#Mann= 3 , 0 , 0
   -12.1    .033       0       0    .033       0       3    .033       0
#XS Ineff= 2 , 0
               0   49.83       3           49.73
Permanent Ineff=
       F       F
Bank Sta=0,3
XS Rating Curve= 0
Exp/Cntr=.3,.1

Type RM Length L Ch R = 1 ,50.00   ,18,18,18
BEGIN DESCRIPTION:
1
END DESCRIPTION:
#Sta/Elev= 10
   -13.5   47.63    -3.5   47.63    -1.5   48.43       0   48.43       0   46.83
       3   46.83       3   48.43     3.3   48.43     3.3   48.23    13.3   48.23
#Mann= 3 , 0 , 0
   -13.5    .033       0       0    .033       0       3    .033       0
#XS Ineff= 2 , 0
               0   48.43       3           48.43
Permanent Ineff=
       F       F
Bank Sta=0,3
XS Rating Curve= 0
Exp/Cntr=.3,.1

Type RM Length L Ch R = 1 ,32.00   ,27,27,27
BEGIN DESCRIPTION:
0.032
END DESCRIPTION:
#Sta/Elev= 8
   -13.5   47.01    -3.5   47.01    -1.5   47.81       0   47.81       0   46.21
       3   46.21       3   47.81       8   47.81
#Mann= 3 , 0 , 0
   -13.5    .033       0       0    .033       0       3    .033       0
#XS Ineff= 2 , 0
               0   47.81       3           47.81
Permanent Ineff=
       F       F
Bank Sta=0,3
XS Rating Curve= 0
Exp/Cntr=.3,.1

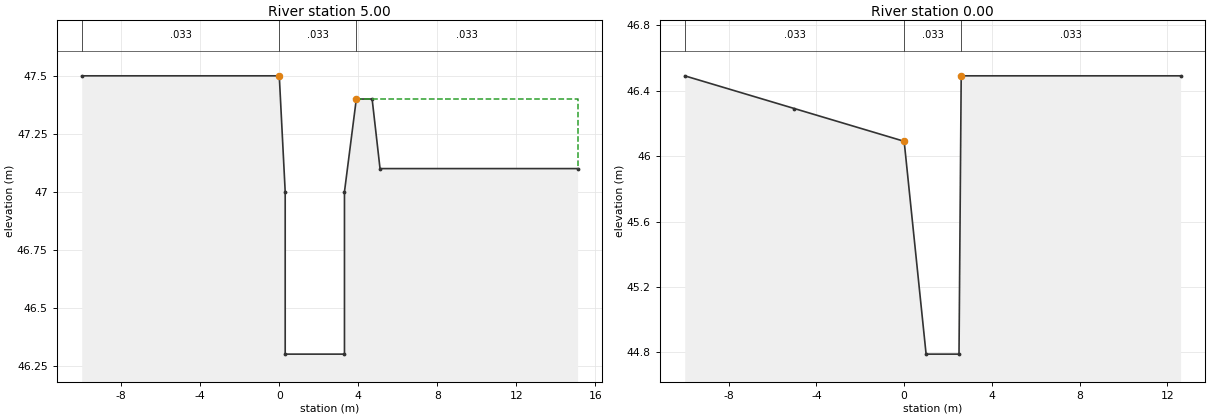
Type RM Length L Ch R = 1 ,5.00    ,5,5,5
BEGIN DESCRIPTION:
0.005
END DESCRIPTION:
#Sta/Elev= 10
     -10    47.5       0    47.5      .3      47      .3    46.3     3.3    46.3
     3.3      47     3.9    47.4     4.7    47.4     5.1    47.1    15.1    47.1
#Mann= 3 , 0 , 0
     -10    .033       0       0    .033       0     3.9    .033       0
#XS Ineff= 2 , 0
               0    47.5     3.9            47.4
Permanent Ineff=
       F       F
Bank Sta=0,3.9
XS Rating Curve= 0
Exp/Cntr=.3,.1

Type RM Length L Ch R = 1 ,0.00    ,0,0,0
BEGIN DESCRIPTION:
0
END DESCRIPTION:
#Sta/Elev= 7
     -10   46.49      -5   46.29       0   46.09       1   44.79     2.5   44.79
     2.6   46.49    12.6   46.49
#Mann= 3 , 0 , 0
     -10    .033       0       0    .033       0     2.6    .033       0
#XS Ineff= 2 , 0
               0   46.09     2.6           46.49
Permanent Ineff=
       F       F
Bank Sta=0,2.6
XS Rating Curve= 0
Exp/Cntr=.3,.1

Chan Stop Cuts=-1