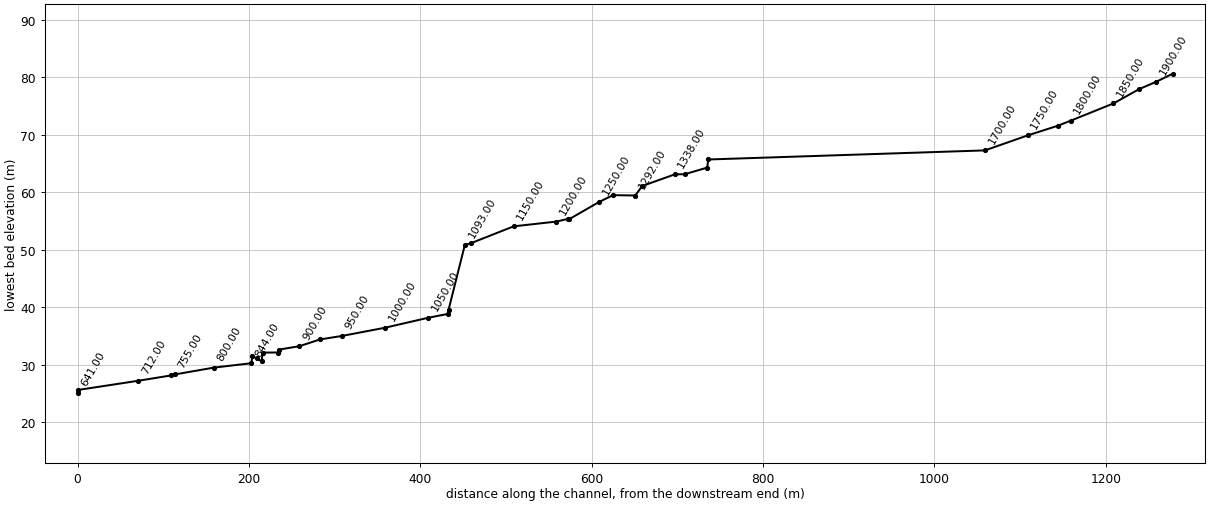
--- HGC.prj (project) ---

Proj Title=HGC
Current Plan=p01
Default Exp/Contr=.3,.1
SI Units
Geom File=g01
Flow File=f01
Plan File=p01
Y Axis Title=Elevation
X Axis Title(PF)=Main Channel Distance
X Axis Title(XS)=Station
BEGIN DESCRIPTION:
           BACK WATER COMPUTATION
      APPLICATION OF HEC-2 BY Samju Construction Engineering
      HEUNGKOK-STREEM : 30 YR
END DESCRIPTION:
DSS Export Rating Curves= 0
DSS Export Rating Curve Sorted= 0
DSS Export Volume Flow Curves= 0
DXF OffsetX= 0
DXF OffsetY= 0
DXF ScaleX= 1
DXF ScaleY= 10

--- HGC.p01 (plan) ---

Plan Title=Imported Plan 01
Version=Version 3.0.1  Mar 2001
Short Identifier=Imported Pla
Geom File=g01
Flow File=f01
Subcritical Flow
K Sum by GR= 0
Std Step Tol= 0.003
Critical Tol= 0.003
Num of Std Step Trials= 20
Max Error Tol= 0.1
Flow Tol Ratio= 0.001
Split Flow NTrial= 30
Split Flow Tol= 0.02
Split Flow Ratio= 0.02
Log Output Level= 0
Friction Slope Method= 1
Unsteady Friction Slope Method= 2
Parabolic Critical Depth
Global Vel Dist= 0 , 0 , 0
Global Log Level= 0
CheckData=True
Encroach Param=-1 ,0,0, 0
Computation Interval=1HOUR
Output Interval=1HOUR
Run HTab= 0
Run UNet= 0
Run PostProcess= 0
UNET Theta= 1
UNET ZTol= 0.02
UNET ZSATol= 0.1
UNET MxIter= 20
UNET MaxInSteps= 20
UNET DtIC= 0
UNET DtMin= 0
UNET MaxCRTS= 20
UNET WFStab= 2
UNET SFStab= 1
UNET WFX= 1
UNET SFX= 1
UNET Convert EG Bridges=-1
UNET Use Existing IB Tables=-1
Instantaneous Interval=1HOUR
Write IC File= 0
Write Velocity= 0
Write Detailed= 0

--- HGC.f01 (steady flow) ---

Flow Title=Imported Flow 01
Version=Version 3.0.1  Mar 2001
Number of Profiles= 5
Profile Names=10YR,20YR,30YR,50YR,80YR
River Rch & RM=RIVER-1,Reach-1         ,37.019
    5.59    6.16    6.49    6.91     7.3
River Rch & RM=RIVER-1,Reach-1         ,30
    9.35    10.3   10.86   11.56   12.21
River Rch & RM=RIVER-1,Reach-1         ,10.026
   11.06   12.19   12.85   13.68   14.45
River Rch & RM=HEUNGKOK,HEUNGKOK        ,1919.00
    5.59    6.16    6.49    6.91     7.3
River Rch & RM=HEUNGKOK,HEUNGKOK        ,1250.00
    9.35    10.3   10.86   11.56   12.21
River Rch & RM=HEUNGKOK,HEUNGKOK        ,526.00
   11.06   12.19   12.85   13.68   14.45
Boundary for River Rch & Prof#=HEUNGKOK,HEUNGKOK        , 1
Up Type= 0
Dn Type= 3
Dn Slope=.034
Boundary for River Rch & Prof#=HEUNGKOK,HEUNGKOK        , 2
Up Type= 0
Dn Type= 3
Dn Slope=.034
Boundary for River Rch & Prof#=HEUNGKOK,HEUNGKOK        , 3
Up Type= 0
Dn Type= 3
Dn Slope=.034
Boundary for River Rch & Prof#=HEUNGKOK,HEUNGKOK        , 4
Up Type= 0
Dn Type= 3
Dn Slope=.034
Boundary for River Rch & Prof#=HEUNGKOK,HEUNGKOK        , 5
Up Type= 0
Dn Type= 3
Dn Slope=.034
DSS Import GetInterval= 0
DSS Import GetPeak= 0
DSS Import FillOption= 0

--- HGC.g01 (geometry) ---

Geom Title=Imported Geom 01
Version=Version 3.0.1  Mar 2001

River Reach=HEUNGKOK        ,HEUNGKOK
Reach XY= 2
              .5             .95              .5             .05

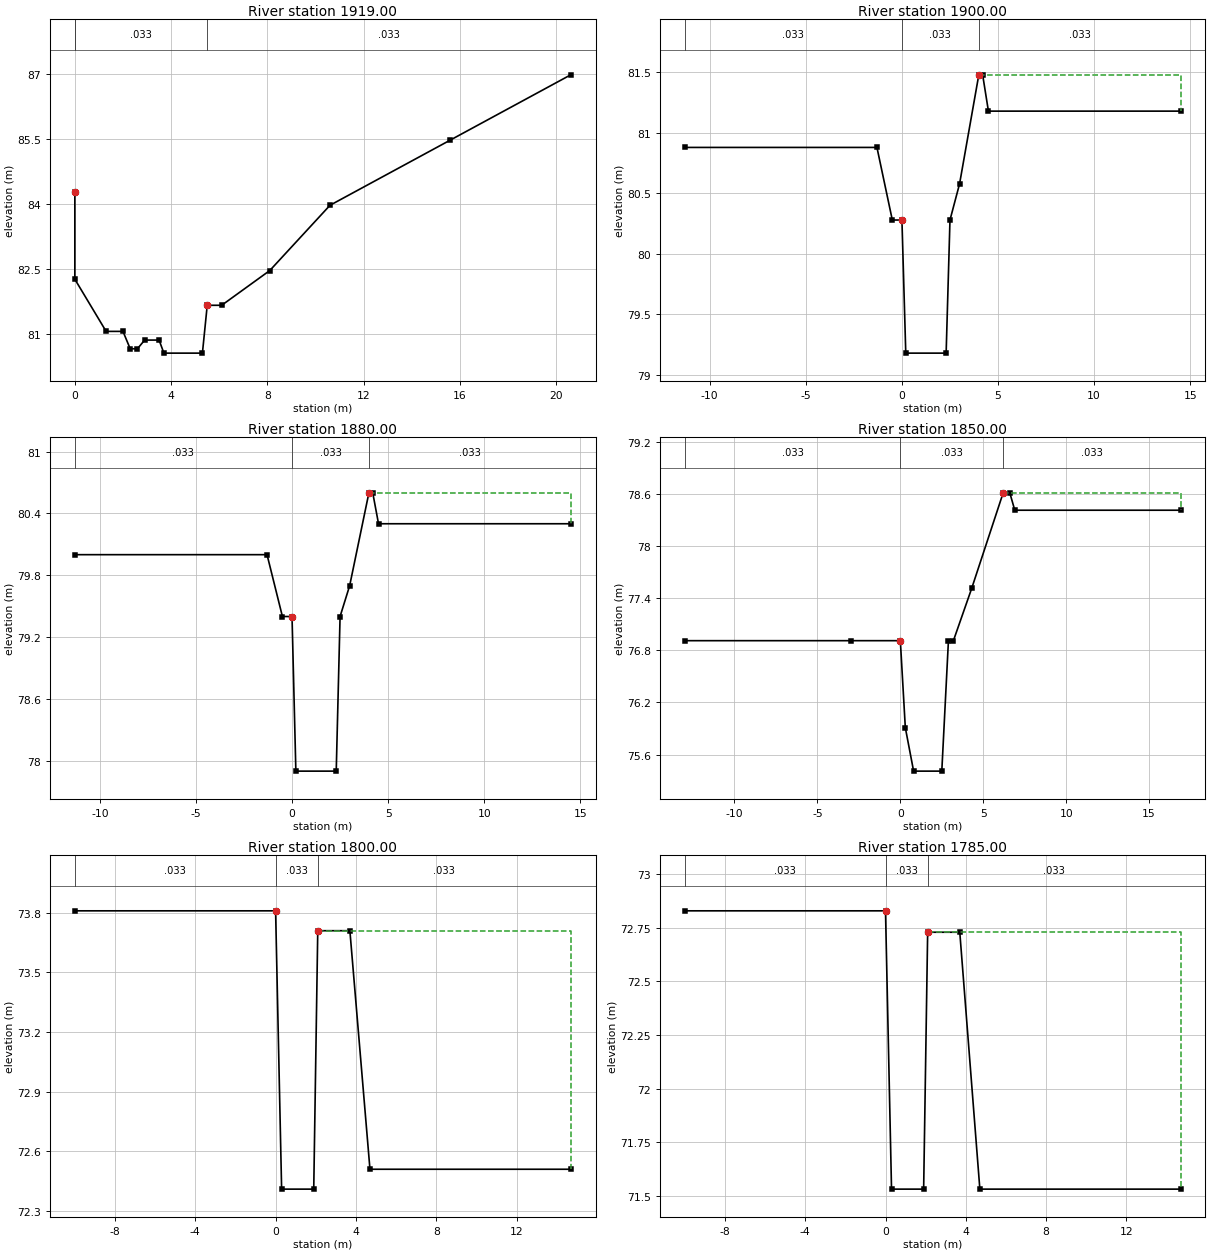
Type RM Length L Ch R = 1 ,1919.00 ,19,19,19
BEGIN DESCRIPTION:
37.019
END DESCRIPTION:
#Sta/Elev= 16
       0   84.27       0   82.27     1.3   81.07       2   81.07     2.3   80.67
     2.6   80.67     2.9   80.87     3.5   80.87     3.7   80.57     5.3   80.57
     5.5   81.67     6.1   81.67     8.1   82.47    10.6   83.97    15.6   85.47
    20.6   86.97
#Mann= 3 , 0 , 0
       0    .033       0       0    .033       0     5.5    .033       0
#XS Ineff= 2 , 0
               0   84.27     5.5           81.67
Permanent Ineff=
       F       F
Bank Sta=0,5.5
XS Rating Curve= 0
Exp/Cntr=.3,.1

Type RM Length L Ch R = 1 ,1900.00 ,20,20,20
BEGIN DESCRIPTION:
37
END DESCRIPTION:
#Sta/Elev= 12
   -11.3   80.88    -1.3   80.88     -.5   80.28       0   80.28      .2   79.18
     2.3   79.18     2.5   80.28       3   80.58       4   81.48     4.2   81.48
     4.5   81.18    14.5   81.18
#Mann= 3 , 0 , 0
   -11.3    .033       0       0    .033       0       4    .033       0
#XS Ineff= 2 , 0
               0   80.28       4           81.48
Permanent Ineff=
       F       F
Bank Sta=0,4
XS Rating Curve= 0
Exp/Cntr=.3,.1

Type RM Length L Ch R = 1 ,1880.00 ,30,30,30
BEGIN DESCRIPTION:
36.03
END DESCRIPTION:
#Sta/Elev= 12
   -11.3      80    -1.3      80     -.5    79.4       0    79.4      .2    77.9
     2.3    77.9     2.5    79.4       3    79.7       4    80.6     4.2    80.6
     4.5    80.3    14.5    80.3
#Mann= 3 , 0 , 0
   -11.3    .033       0       0    .033       0       4    .033       0
#XS Ineff= 2 , 0
               0    79.4       4            80.6
Permanent Ineff=
       F       F
Bank Sta=0,4
XS Rating Curve= 0
Exp/Cntr=.3,.1

Type RM Length L Ch R = 1 ,1850.00 ,50,50,50
BEGIN DESCRIPTION:
36
END DESCRIPTION:
#Sta/Elev= 13
     -13   76.91      -3   76.91       0   76.91      .3   75.91      .8   75.41
     2.5   75.41     2.9   76.91     3.2   76.91     4.3   77.51     6.2   78.61
     6.6   78.61     6.9   78.41    16.9   78.41
#Mann= 3 , 0 , 0
     -13    .033       0       0    .033       0     6.2    .033       0
#XS Ineff= 2 , 0
               0   76.91     6.2           78.61
Permanent Ineff=
       F       F
Bank Sta=0,6.2
XS Rating Curve= 0
Exp/Cntr=.3,.1

Type RM Length L Ch R = 1 ,1800.00 ,15,15,15
BEGIN DESCRIPTION:
35
END DESCRIPTION:
#Sta/Elev= 8
     -10   73.81       0   73.81      .3   72.41     1.9   72.41     2.1   73.71
     3.7   73.71     4.7   72.51    14.7   72.51
#Mann= 3 , 0 , 0
     -10    .033       0       0    .033       0     2.1    .033       0
#XS Ineff= 2 , 0
               0   73.81     2.1           73.71
Permanent Ineff=
       F       F
Bank Sta=0,2.1
XS Rating Curve= 0
Exp/Cntr=.3,.1

Type RM Length L Ch R = 1 ,1785.00 ,35,35,35
BEGIN DESCRIPTION:
34.035
END DESCRIPTION:
#Sta/Elev= 8
     -10   72.83       0   72.83      .3   71.53     1.9   71.53     2.1   72.73
     3.7   72.73     4.7   71.53    14.7   71.53
#Mann= 3 , 0 , 0
     -10    .033       0       0    .033       0     2.1    .033       0
#XS Ineff= 2 , 0
               0   72.83     2.1           72.73
Permanent Ineff=
       F       F
Bank Sta=0,2.1
XS Rating Curve= 0
Exp/Cntr=.3,.1

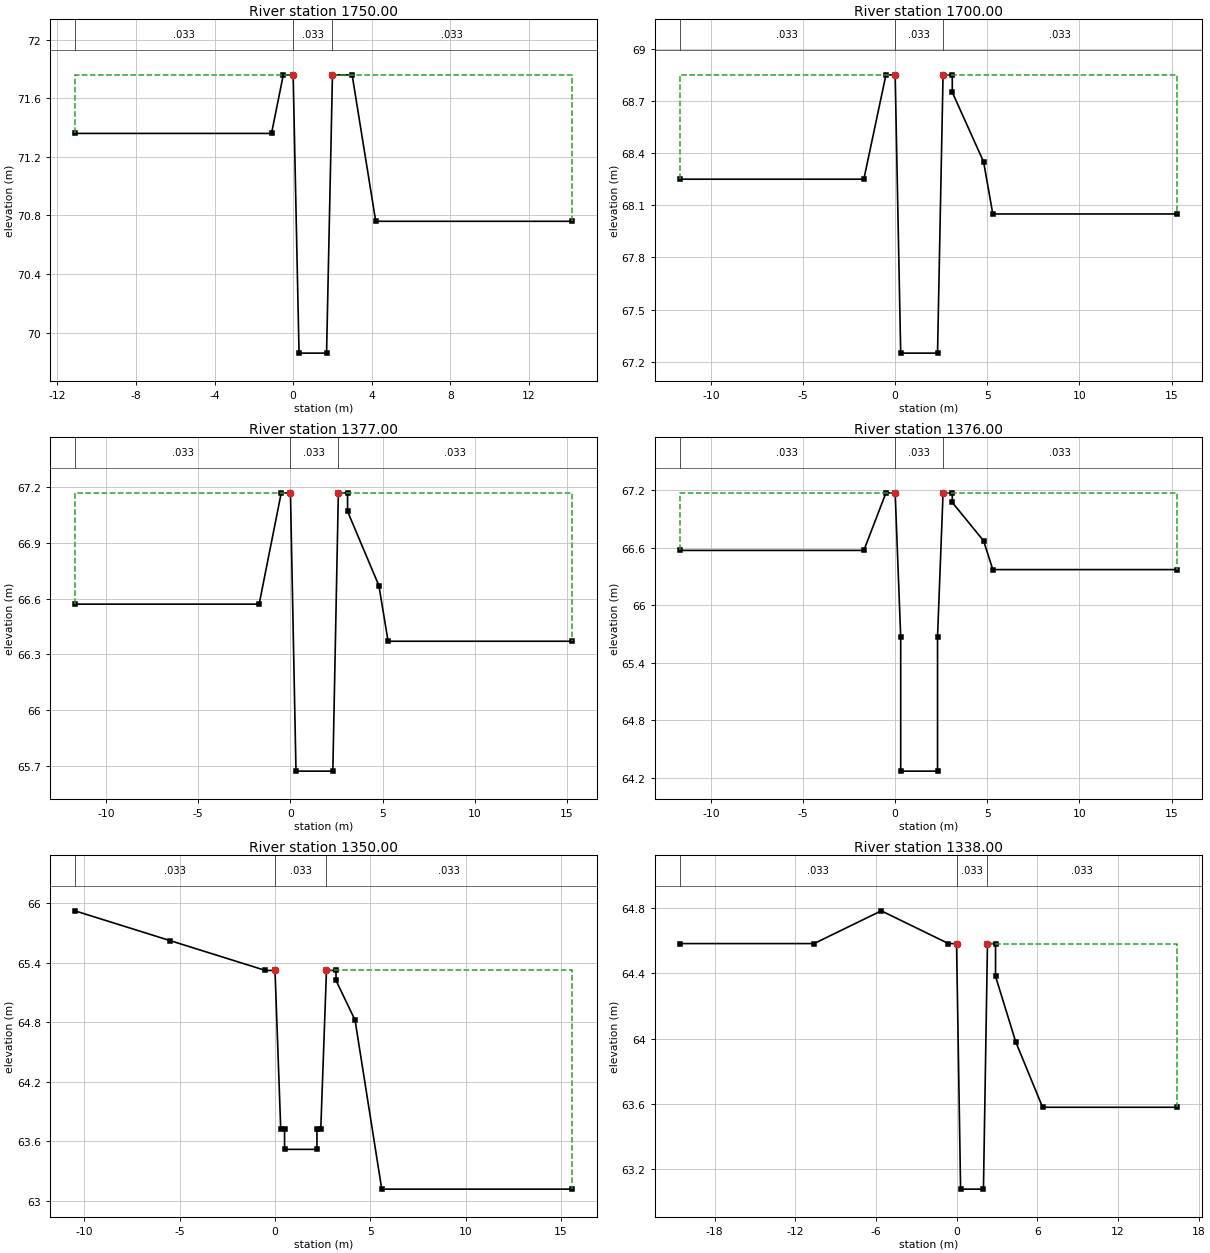
Type RM Length L Ch R = 1 ,1750.00 ,50,50,50
BEGIN DESCRIPTION:
34
END DESCRIPTION:
#Sta/Elev= 10
   -11.1   71.36    -1.1   71.36     -.5   71.76       0   71.76      .3   69.86
     1.7   69.86       2   71.76       3   71.76     4.2   70.76    14.2   70.76
#Mann= 3 , 0 , 0
   -11.1    .033       0       0    .033       0       2    .033       0
#XS Ineff= 2 , 0
               0   71.76       2           71.76
Permanent Ineff=
       F       F
Bank Sta=0,2
XS Rating Curve= 0
Exp/Cntr=.3,.1

Type RM Length L Ch R = 1 ,1700.00 ,23,323,23
BEGIN DESCRIPTION:
33
END DESCRIPTION:
#Sta/Elev= 12
   -11.7   68.25    -1.7   68.25     -.5   68.85       0   68.85      .3   67.25
     2.3   67.25     2.6   68.85     3.1   68.85     3.1   68.75     4.8   68.35
     5.3   68.05    15.3   68.05
#Mann= 3 , 0 , 0
   -11.7    .033       0       0    .033       0     2.6    .033       0
#XS Ineff= 2 , 0
               0   68.85     2.6           68.85
Permanent Ineff=
       F       F
Bank Sta=0,2.6
XS Rating Curve= 0
Exp/Cntr=.3,.1

Type RM Length L Ch R = 1 ,1377.00 ,1,1,1
BEGIN DESCRIPTION:
32.027
END DESCRIPTION:
#Sta/Elev= 12
   -11.7   66.57    -1.7   66.57     -.5   67.17       0   67.17      .3   65.67
     2.3   65.67     2.6   67.17     3.1   67.17     3.1   67.07     4.8   66.67
     5.3   66.37    15.3   66.37
#Mann= 3 , 0 , 0
   -11.7    .033       0       0    .033       0     2.6    .033       0
#XS Ineff= 2 , 0
               0   67.17     2.6           67.17
Permanent Ineff=
       F       F
Bank Sta=0,2.6
XS Rating Curve= 0
Exp/Cntr=.3,.1

Type RM Length L Ch R = 1 ,1376.00 ,26,26,26
BEGIN DESCRIPTION:
32.026
END DESCRIPTION:
#Sta/Elev= 14
   -11.7   66.57    -1.7   66.57     -.5   67.17       0   67.17      .3   65.67
      .3   64.27     2.3   64.27     2.3   65.67     2.6   67.17     3.1   67.17
     3.1   67.07     4.8   66.67     5.3   66.37    15.3   66.37
#Mann= 3 , 0 , 0
   -11.7    .033       0       0    .033       0     2.6    .033       0
#XS Ineff= 2 , 0
               0   67.17     2.6           67.17
Permanent Ineff=
       F       F
Bank Sta=0,2.6
XS Rating Curve= 0
Exp/Cntr=.3,.1

Type RM Length L Ch R = 1 ,1350.00 ,12,12,12
BEGIN DESCRIPTION:
32
END DESCRIPTION:
#Sta/Elev= 16
   -10.5   65.92    -5.5   65.62     -.5   65.32       0   65.32      .3   63.72
      .5   63.72      .5   63.52     2.2   63.52     2.2   63.72     2.4   63.72
     2.7   65.32     3.2   65.32     3.2   65.22     4.2   64.82     5.6   63.12
    15.6   63.12
#Mann= 3 , 0 , 0
   -10.5    .033       0       0    .033       0     2.7    .033       0
#XS Ineff= 2 , 0
               0   65.32     2.7           65.32
Permanent Ineff=
       F       F
Bank Sta=0,2.7
XS Rating Curve= 0
Exp/Cntr=.3,.1

Type RM Length L Ch R = 1 ,1338.00 ,38,38,38
BEGIN DESCRIPTION:
31.038
END DESCRIPTION:
#Sta/Elev= 13
   -20.6   64.58   -10.6   64.58    -5.6   64.78     -.6   64.58       0   64.58
      .3   63.08       2   63.08     2.3   64.58     2.9   64.58     2.9   64.38
     4.4   63.98     6.4   63.58    16.4   63.58
#Mann= 3 , 0 , 0
   -20.6    .033       0       0    .033       0     2.3    .033       0
#XS Ineff= 2 , 0
               0   64.58     2.3           64.58
Permanent Ineff=
       F       F
Bank Sta=0,2.3
XS Rating Curve= 0
Exp/Cntr=.3,.1

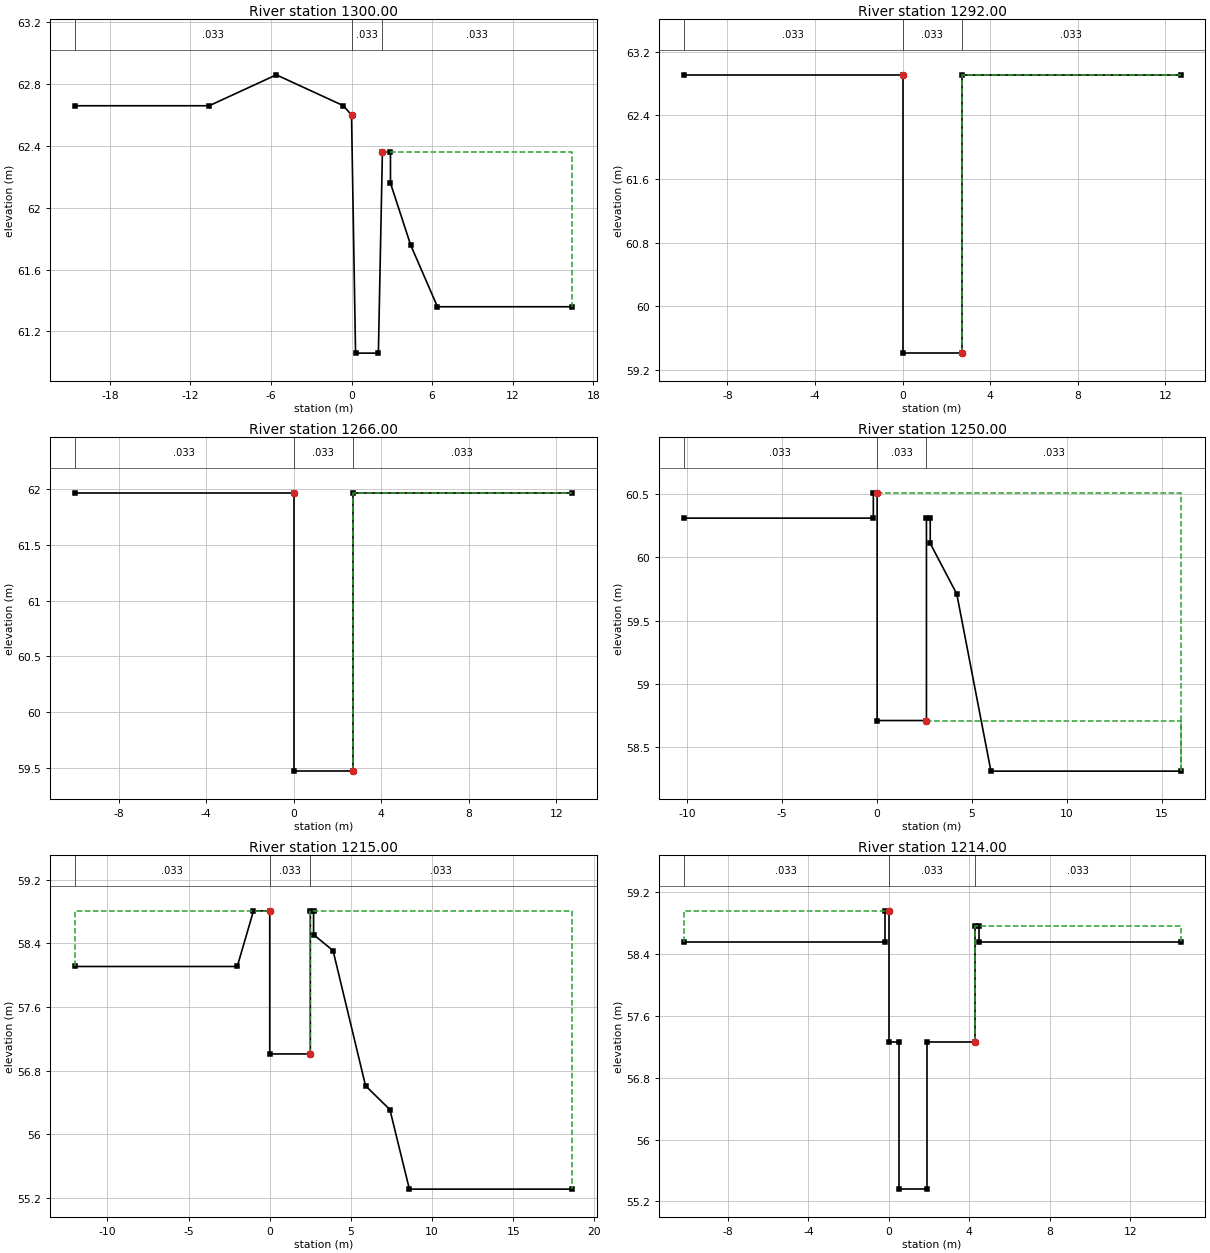
Type RM Length L Ch R = 1 ,1300.00 ,8,8,8
BEGIN DESCRIPTION:
31
END DESCRIPTION:
#Sta/Elev= 13
   -20.6   62.66   -10.6   62.66    -5.6   62.86     -.6   62.66       0    62.6
      .3   61.06       2   61.06     2.3   62.36     2.9   62.36     2.9   62.16
     4.4   61.76     6.4   61.36    16.4   61.36
#Mann= 3 , 0 , 0
   -20.6    .033       0       0    .033       0     2.3    .033       0
#XS Ineff= 2 , 0
               0    62.6     2.3           62.36
Permanent Ineff=
       F       F
Bank Sta=0,2.3
XS Rating Curve= 0
Exp/Cntr=.3,.1

Type RM Length L Ch R = 1 ,1292.00 ,26,26,26
BEGIN DESCRIPTION:
30.042
END DESCRIPTION:
#Sta/Elev= 6
     -10   62.91       0   62.91       0   59.41     2.7   59.41     2.7   62.91
    12.7   62.91
#Mann= 3 , 0 , 0
     -10    .033       0       0    .033       0     2.7    .033       0
#XS Ineff= 2 , 0
               0   62.91     2.7           62.91
Permanent Ineff=
       F       F
Bank Sta=0,2.7
XS Rating Curve= 0
Exp/Cntr=.3,.1

Type RM Length L Ch R = 1 ,1266.00 ,16,16,16
BEGIN DESCRIPTION:
30.016
END DESCRIPTION:
#Sta/Elev= 6
     -10   61.97       0   61.97       0   59.47     2.7   59.47     2.7   61.97
    12.7   61.97
#Mann= 3 , 0 , 0
     -10    .033       0       0    .033       0     2.7    .033       0
#XS Ineff= 2 , 0
               0   61.97     2.7           61.97
Permanent Ineff=
       F       F
Bank Sta=0,2.7
XS Rating Curve= 0
Exp/Cntr=.3,.1

Type RM Length L Ch R = 1 ,1250.00 ,35,35,35
BEGIN DESCRIPTION:
30
END DESCRIPTION:
#Sta/Elev= 12
   -10.2   60.31     -.2   60.31     -.2   60.51       0   60.51       0   58.71
     2.6   58.71     2.6   60.31     2.8   60.31     2.8   60.11     4.2   59.71
       6   58.31      16   58.31
#Mann= 3 , 0 , 0
   -10.2    .033       0       0    .033       0     2.6    .033       0
#XS Ineff= 2 , 0
       0       0   60.51     2.6       0   58.71
Permanent Ineff=
       F       F
Bank Sta=0,2.6
XS Rating Curve= 0
Exp/Cntr=.3,.1

Type RM Length L Ch R = 1 ,1215.00 ,1,1,1
BEGIN DESCRIPTION:
29.015
END DESCRIPTION:
#Sta/Elev= 14
     -12   58.11      -2   58.11      -1   58.81       0   58.81       0   57.01
     2.5   57.01     2.5   58.81     2.7   58.81     2.7   58.51     3.9   58.31
     5.9   56.61     7.4   56.31     8.6   55.31    18.6   55.31
#Mann= 3 , 0 , 0
     -12    .033       0       0    .033       0     2.5    .033       0
#XS Ineff= 2 , 0
               0   58.81     2.5           58.81
Permanent Ineff=
       F       F
Bank Sta=0,2.5
XS Rating Curve= 0
Exp/Cntr=.3,.1

Type RM Length L Ch R = 1 ,1214.00 ,14,14,14
BEGIN DESCRIPTION:
29.014
END DESCRIPTION:
#Sta/Elev= 14
   -10.2   58.56     -.2   58.56     -.2   58.96       0   58.96       0   57.26
      .5   57.26      .5   55.36     1.9   55.36     1.9   57.26     4.3   57.26
     4.3   58.76     4.5   58.76     4.5   58.56    14.5   58.56
#Mann= 3 , 0 , 0
   -10.2    .033       0       0    .033       0     4.3    .033       0
#XS Ineff= 2 , 0
               0   58.96     4.3           58.76
Permanent Ineff=
       F       F
Bank Sta=0,4.3
XS Rating Curve= 0
Exp/Cntr=.3,.1

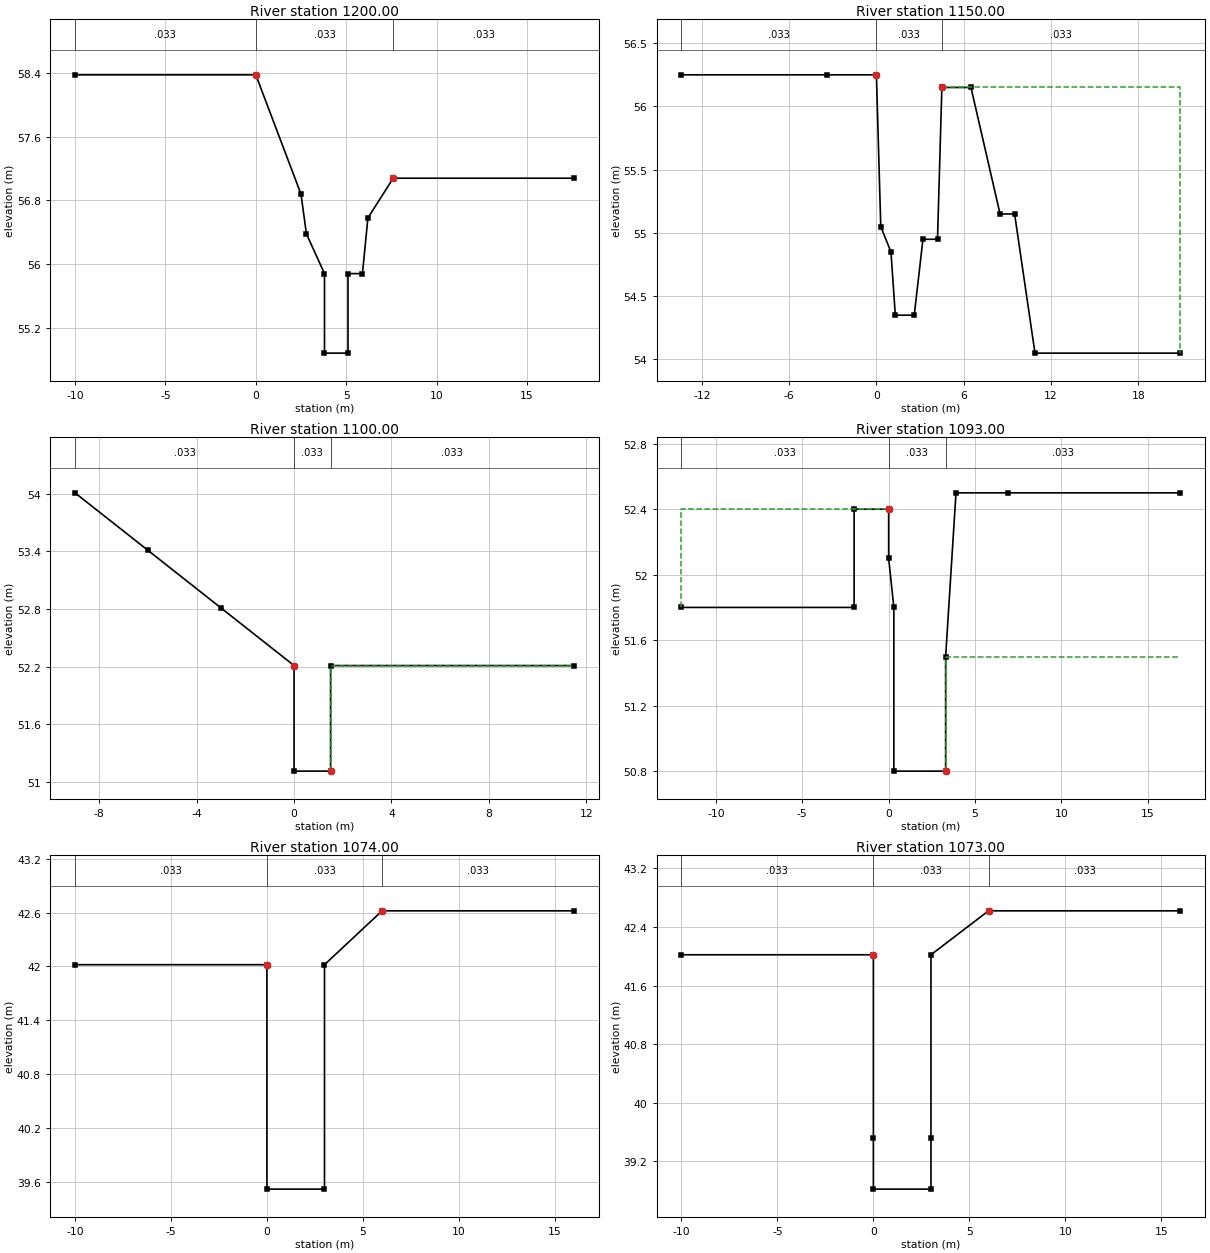
Type RM Length L Ch R = 1 ,1200.00 ,50,50,50
BEGIN DESCRIPTION:
29
END DESCRIPTION:
#Sta/Elev= 12
     -10   58.38       0   58.38     2.5   56.88     2.8   56.38     3.8   55.88
     3.8   54.88     5.1   54.88     5.1   55.88     5.9   55.88     6.2   56.58
     7.6   57.08    17.6   57.08
#Mann= 3 , 0 , 0
     -10    .033       0       0    .033       0     7.6    .033       0
#XS Ineff= 2 , 0
               0   58.38     7.6           57.08
Permanent Ineff=
       F       F
Bank Sta=0,7.6
XS Rating Curve= 0
Exp/Cntr=.3,.1

Type RM Length L Ch R = 1 ,1150.00 ,50,50,50
BEGIN DESCRIPTION:
28
END DESCRIPTION:
#Sta/Elev= 15
   -13.4   56.25    -3.4   56.25       0   56.25      .3   55.05       1   54.85
     1.3   54.35     2.6   54.35     3.2   54.95     4.2   54.95     4.5   56.15
     6.5   56.15     8.5   55.15     9.5   55.15    10.9   54.05    20.9   54.05
#Mann= 3 , 0 , 0
   -13.4    .033       0       0    .033       0     4.5    .033       0
#XS Ineff= 2 , 0
               0   56.25     4.5           56.15
Permanent Ineff=
       F       F
Bank Sta=0,4.5
XS Rating Curve= 0
Exp/Cntr=.3,.1

Type RM Length L Ch R = 1 ,1100.00 ,7,7,7
BEGIN DESCRIPTION:
27
END DESCRIPTION:
#Sta/Elev= 8
      -9   54.01      -6   53.41      -3   52.81       0   52.21       0   51.11
     1.5   51.11     1.5   52.21    11.5   52.21
#Mann= 3 , 0 , 0
      -9    .033       0       0    .033       0     1.5    .033       0
#XS Ineff= 2 , 0
               0   52.21     1.5           52.21
Permanent Ineff=
       F       F
Bank Sta=0,1.5
XS Rating Curve= 0
Exp/Cntr=.3,.1

Type RM Length L Ch R = 1 ,1093.00 ,19,19,19
BEGIN DESCRIPTION:
26.043
END DESCRIPTION:
#Sta/Elev= 12
     -12    51.8      -2    51.8      -2    52.4       0    52.4       0    52.1
      .3    51.8      .3    50.8     3.3    50.8     3.3    51.5     3.9    52.5
     6.9    52.5    16.9    52.5
#Mann= 3 , 0 , 0
     -12    .033       0       0    .033       0     3.3    .033       0
#XS Ineff= 2 , 0
               0    52.4     3.3            51.5
Permanent Ineff=
       F       F
Bank Sta=0,3.3
XS Rating Curve= 0
Exp/Cntr=.3,.1

Type RM Length L Ch R = 1 ,1074.00 ,1,1,1
BEGIN DESCRIPTION:
21.024
END DESCRIPTION:
#Sta/Elev= 7
     -10   42.02       0   42.02       0   39.52       3   39.52       3   42.02
       6   42.62      16   42.62
#Mann= 3 , 0 , 0
     -10    .033       0       0    .033       0       6    .033       0
#XS Ineff= 2 , 0
               0   42.02       6           42.62
Permanent Ineff=
       F       F
Bank Sta=0,6
XS Rating Curve= 0
Exp/Cntr=.3,.1

Type RM Length L Ch R = 1 ,1073.00 ,23,23,23
BEGIN DESCRIPTION:
21.023
END DESCRIPTION:
#Sta/Elev= 9
     -10   42.02       0   42.02       0   39.52       0   38.82       3   38.82
       3   39.52       3   42.02       6   42.62      16   42.62
#Mann= 3 , 0 , 0
     -10    .033       0       0    .033       0       6    .033       0
#XS Ineff= 2 , 0
               0   42.02       6           42.62
Permanent Ineff=
       F       F
Bank Sta=0,6
XS Rating Curve= 0
Exp/Cntr=.3,.1

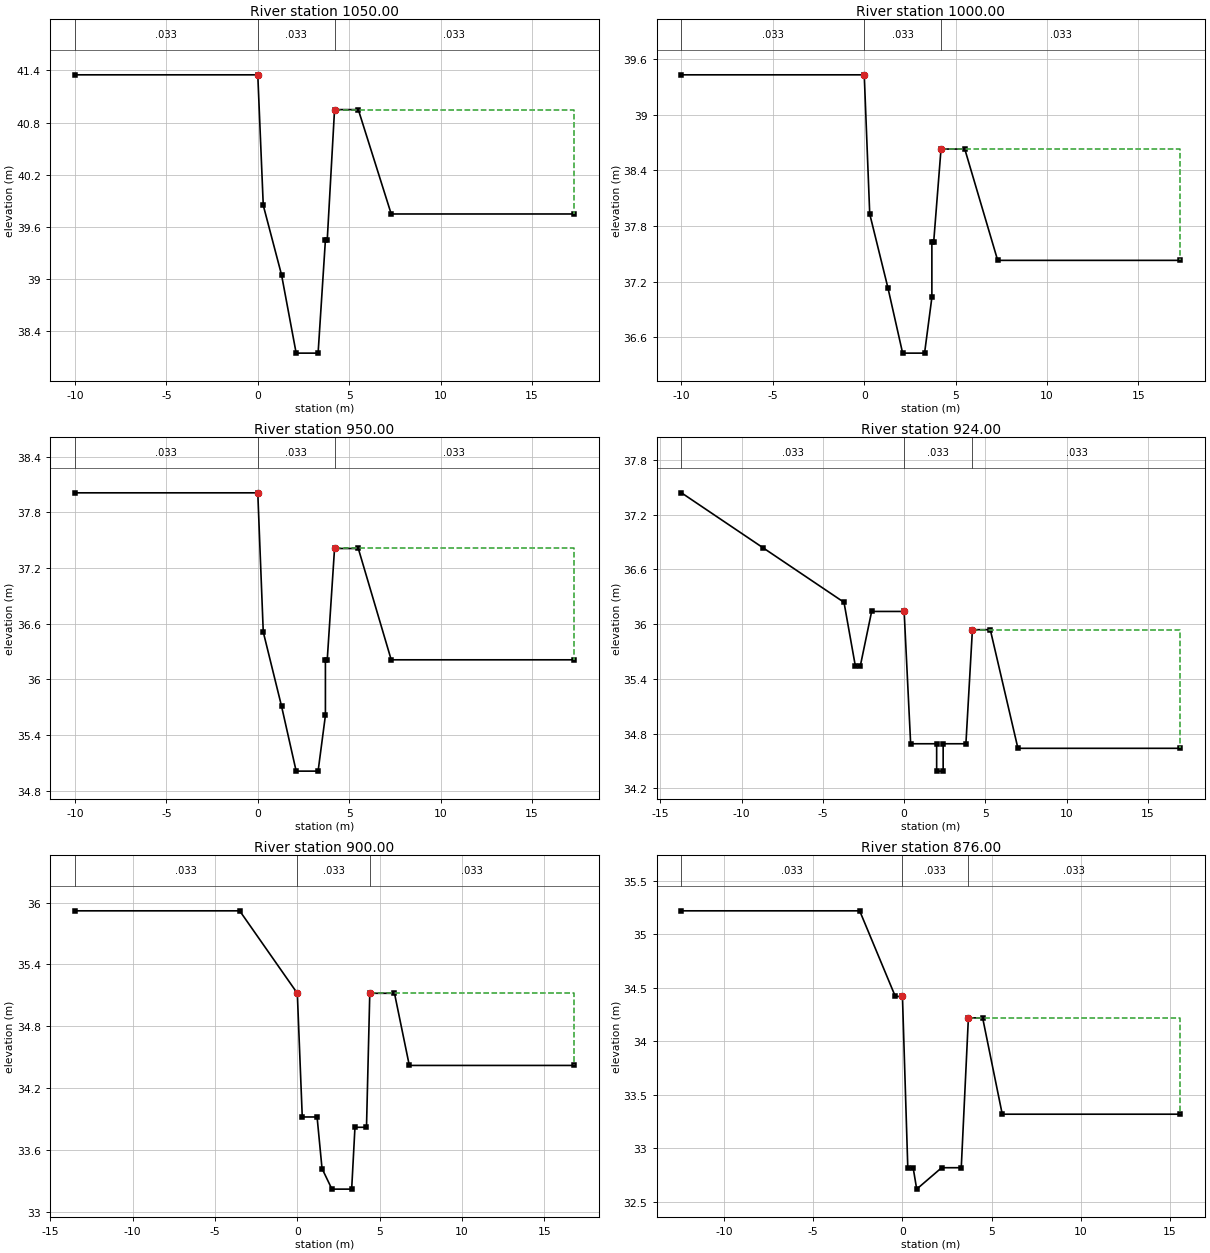
Type RM Length L Ch R = 1 ,1050.00 ,50,50,50
BEGIN DESCRIPTION:
21
END DESCRIPTION:
#Sta/Elev= 12
     -10   41.35       0   41.35      .3   39.85     1.3   39.05     2.1   38.15
     3.3   38.15     3.7   39.45     3.8   39.45     4.2   40.95     5.5   40.95
     7.3   39.75    17.3   39.75
#Mann= 3 , 0 , 0
     -10    .033       0       0    .033       0     4.2    .033       0
#XS Ineff= 2 , 0
               0   41.35     4.2           40.95
Permanent Ineff=
       F       F
Bank Sta=0,4.2
XS Rating Curve= 0
Exp/Cntr=.3,.1

Type RM Length L Ch R = 1 ,1000.00 ,50,50,50
BEGIN DESCRIPTION:
20
END DESCRIPTION:
#Sta/Elev= 13
     -10   39.43       0   39.43      .3   37.93     1.3   37.13     2.1   36.43
     3.3   36.43     3.7   37.03     3.7   37.63     3.8   37.63     4.2   38.63
     5.5   38.63     7.3   37.43    17.3   37.43
#Mann= 3 , 0 , 0
     -10    .033       0       0    .033       0     4.2    .033       0
#XS Ineff= 2 , 0
               0   39.43     4.2           38.63
Permanent Ineff=
       F       F
Bank Sta=0,4.2
XS Rating Curve= 0
Exp/Cntr=.3,.1

Type RM Length L Ch R = 1 ,950.00  ,26,26,26
BEGIN DESCRIPTION:
19
END DESCRIPTION:
#Sta/Elev= 13
     -10   38.01       0   38.01      .3   36.51     1.3   35.71     2.1   35.01
     3.3   35.01     3.7   35.61     3.7   36.21     3.8   36.21     4.2   37.41
     5.5   37.41     7.3   36.21    17.3   36.21
#Mann= 3 , 0 , 0
     -10    .033       0       0    .033       0     4.2    .033       0
#XS Ineff= 2 , 0
               0   38.01     4.2           37.41
Permanent Ineff=
       F       F
Bank Sta=0,4.2
XS Rating Curve= 0
Exp/Cntr=.3,.1

Type RM Length L Ch R = 1 ,924.00  ,24,24,24
BEGIN DESCRIPTION:
18.024
END DESCRIPTION:
#Sta/Elev= 17
   -13.7   37.44    -8.7   36.84    -3.7   36.24      -3   35.54    -2.7   35.54
      -2   36.14       0   36.14      .4   34.69       2   34.69       2   34.39
     2.4   34.39     2.4   34.69     3.8   34.69     4.2   35.94     5.3   35.94
       7   34.64      17   34.64
#Mann= 3 , 0 , 0
   -13.7    .033       0       0    .033       0     4.2    .033       0
#XS Ineff= 2 , 0
               0   36.14     4.2           35.94
Permanent Ineff=
       F       F
Bank Sta=0,4.2
XS Rating Curve= 0
Exp/Cntr=.3,.1

Type RM Length L Ch R = 1 ,900.00  ,24,24,24
BEGIN DESCRIPTION:
18
END DESCRIPTION:
#Sta/Elev= 14
   -13.5   35.92    -3.5   35.92       0   35.12      .3   33.92     1.2   33.92
     1.5   33.42     2.1   33.22     3.3   33.22     3.5   33.82     4.2   33.82
     4.4   35.12     5.9   35.12     6.8   34.42    16.8   34.42
#Mann= 3 , 0 , 0
   -13.5    .033       0       0    .033       0     4.4    .033       0
#XS Ineff= 2 , 0
               0   35.12     4.4           35.12
Permanent Ineff=
       F       F
Bank Sta=0,4.4
XS Rating Curve= 0
Exp/Cntr=.3,.1

Type RM Length L Ch R = 1 ,876.00  ,1,1,1
BEGIN DESCRIPTION:
17.026
END DESCRIPTION:
#Sta/Elev= 13
   -12.4   35.22    -2.4   35.22     -.4   34.42       0   34.42      .3   32.82
      .6   32.82      .8   32.62     2.2   32.82     3.3   32.82     3.7   34.22
     4.5   34.22     5.6   33.32    15.6   33.32
#Mann= 3 , 0 , 0
   -12.4    .033       0       0    .033       0     3.7    .033       0
#XS Ineff= 2 , 0
               0   34.42     3.7           34.22
Permanent Ineff=
       F       F
Bank Sta=0,3.7
XS Rating Curve= 0
Exp/Cntr=.3,.1

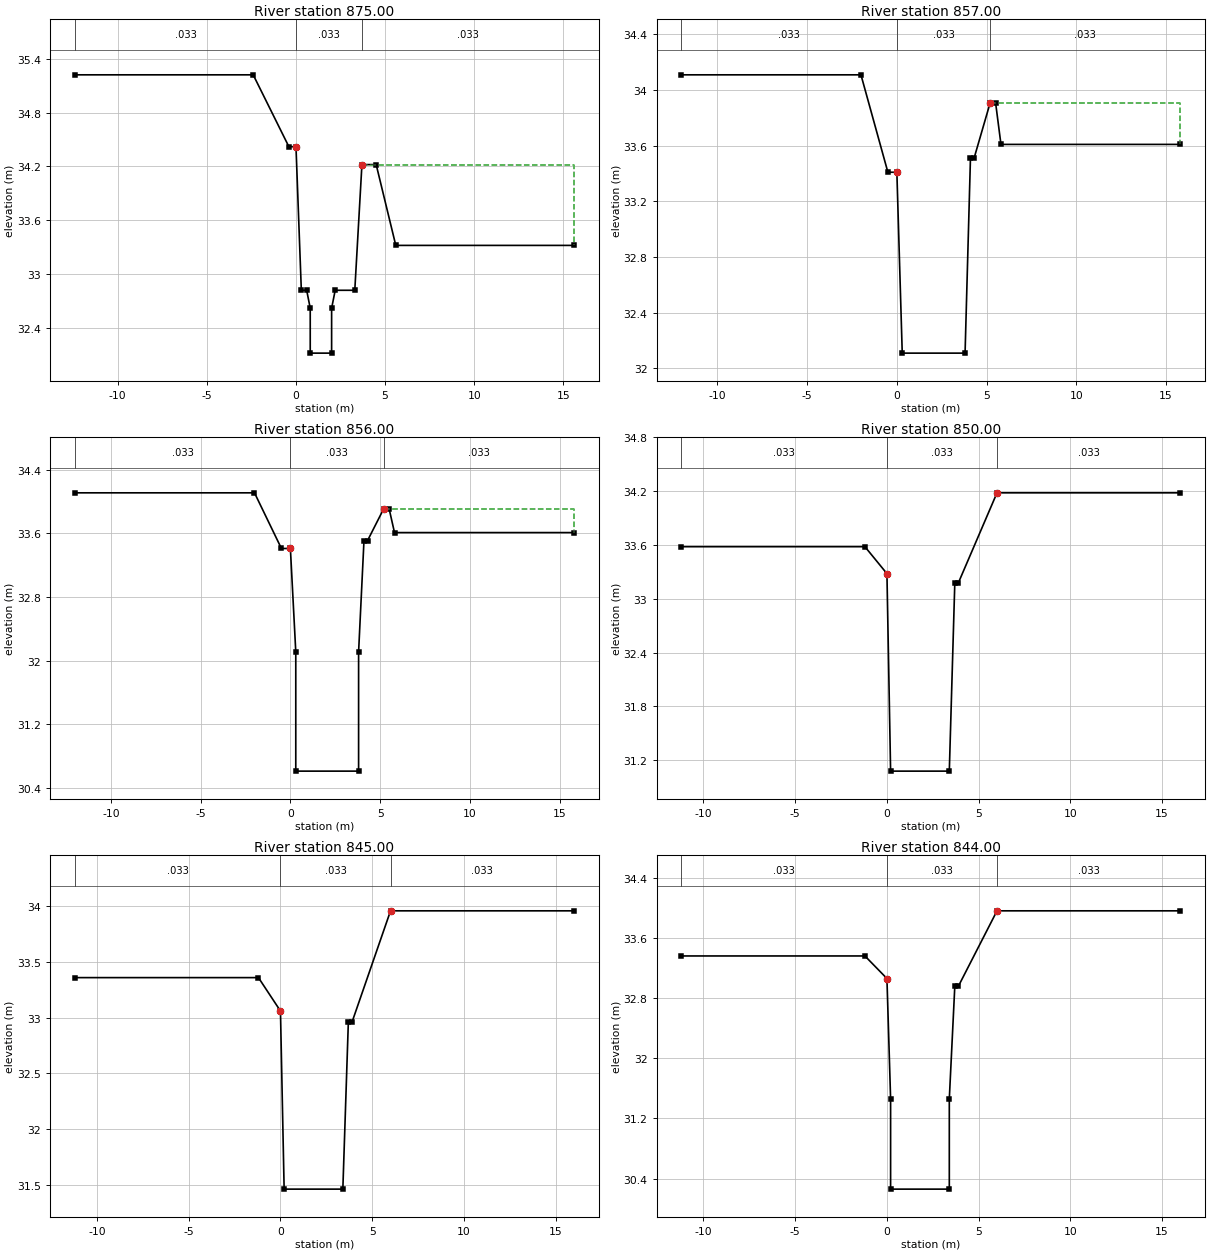
Type RM Length L Ch R = 1 ,875.00  ,18,18,18
BEGIN DESCRIPTION:
17.025
END DESCRIPTION:
#Sta/Elev= 16
   -12.4   35.22    -2.4   35.22     -.4   34.42       0   34.42      .3   32.82
      .6   32.82      .8   32.62      .8   32.12       2   32.12       2   32.62
     2.2   32.82     3.3   32.82     3.7   34.22     4.5   34.22     5.6   33.32
    15.6   33.32
#Mann= 3 , 0 , 0
   -12.4    .033       0       0    .033       0     3.7    .033       0
#XS Ineff= 2 , 0
               0   34.42     3.7           34.22
Permanent Ineff=
       F       F
Bank Sta=0,3.7
XS Rating Curve= 0
Exp/Cntr=.3,.1

Type RM Length L Ch R = 1 ,857.00  ,1,1,1
BEGIN DESCRIPTION:
17.007
END DESCRIPTION:
#Sta/Elev= 12
     -12   34.11      -2   34.11     -.5   33.41       0   33.41      .3   32.11
     3.8   32.11     4.1   33.51     4.3   33.51     5.2   33.91     5.5   33.91
     5.8   33.61    15.8   33.61
#Mann= 3 , 0 , 0
     -12    .033       0       0    .033       0     5.2    .033       0
#XS Ineff= 2 , 0
               0   33.41     5.2           33.91
Permanent Ineff=
       F       F
Bank Sta=0,5.2
XS Rating Curve= 0
Exp/Cntr=.3,.1

Type RM Length L Ch R = 1 ,856.00  ,6,6,6
BEGIN DESCRIPTION:
17.006
END DESCRIPTION:
#Sta/Elev= 14
     -12   34.11      -2   34.11     -.5   33.41       0   33.41      .3   32.11
      .3   30.61     3.8   30.61     3.8   32.11     4.1   33.51     4.3   33.51
     5.2   33.91     5.5   33.91     5.8   33.61    15.8   33.61
#Mann= 3 , 0 , 0
     -12    .033       0       0    .033       0     5.2    .033       0
#XS Ineff= 2 , 0
               0   33.41     5.2           33.91
Permanent Ineff=
       F       F
Bank Sta=0,5.2
XS Rating Curve= 0
Exp/Cntr=.3,.1

Type RM Length L Ch R = 1 ,850.00  ,5,5,5
BEGIN DESCRIPTION:
17
END DESCRIPTION:
#Sta/Elev= 9
   -11.2   33.58    -1.2   33.58       0   33.28      .2   31.08     3.4   31.08
     3.7   33.18     3.9   33.18       6   34.18      16   34.18
#Mann= 3 , 0 , 0
   -11.2    .033       0       0    .033       0       6    .033       0
#XS Ineff= 2 , 0
               0   33.28       6           34.18
Permanent Ineff=
       F       F
Bank Sta=0,6
XS Rating Curve= 0
Exp/Cntr=.3,.1

Type RM Length L Ch R = 1 ,845.00  ,1,1,1
BEGIN DESCRIPTION:
16.045
END DESCRIPTION:
#Sta/Elev= 9
   -11.2   33.36    -1.2   33.36       0   33.06      .2   31.46     3.4   31.46
     3.7   32.96     3.9   32.96       6   33.96      16   33.96
#Mann= 3 , 0 , 0
   -11.2    .033       0       0    .033       0       6    .033       0
#XS Ineff= 2 , 0
               0   33.06       6           33.96
Permanent Ineff=
       F       F
Bank Sta=0,6
XS Rating Curve= 0
Exp/Cntr=.3,.1

Type RM Length L Ch R = 1 ,844.00  ,44,44,44
BEGIN DESCRIPTION:
16.044
END DESCRIPTION:
#Sta/Elev= 11
   -11.2   33.36    -1.2   33.36       0   33.06      .2   31.46      .2   30.26
     3.4   30.26     3.4   31.46     3.7   32.96     3.9   32.96       6   33.96
      16   33.96
#Mann= 3 , 0 , 0
   -11.2    .033       0       0    .033       0       6    .033       0
#XS Ineff= 2 , 0
               0   33.06       6           33.96
Permanent Ineff=
       F       F
Bank Sta=0,6
XS Rating Curve= 0
Exp/Cntr=.3,.1

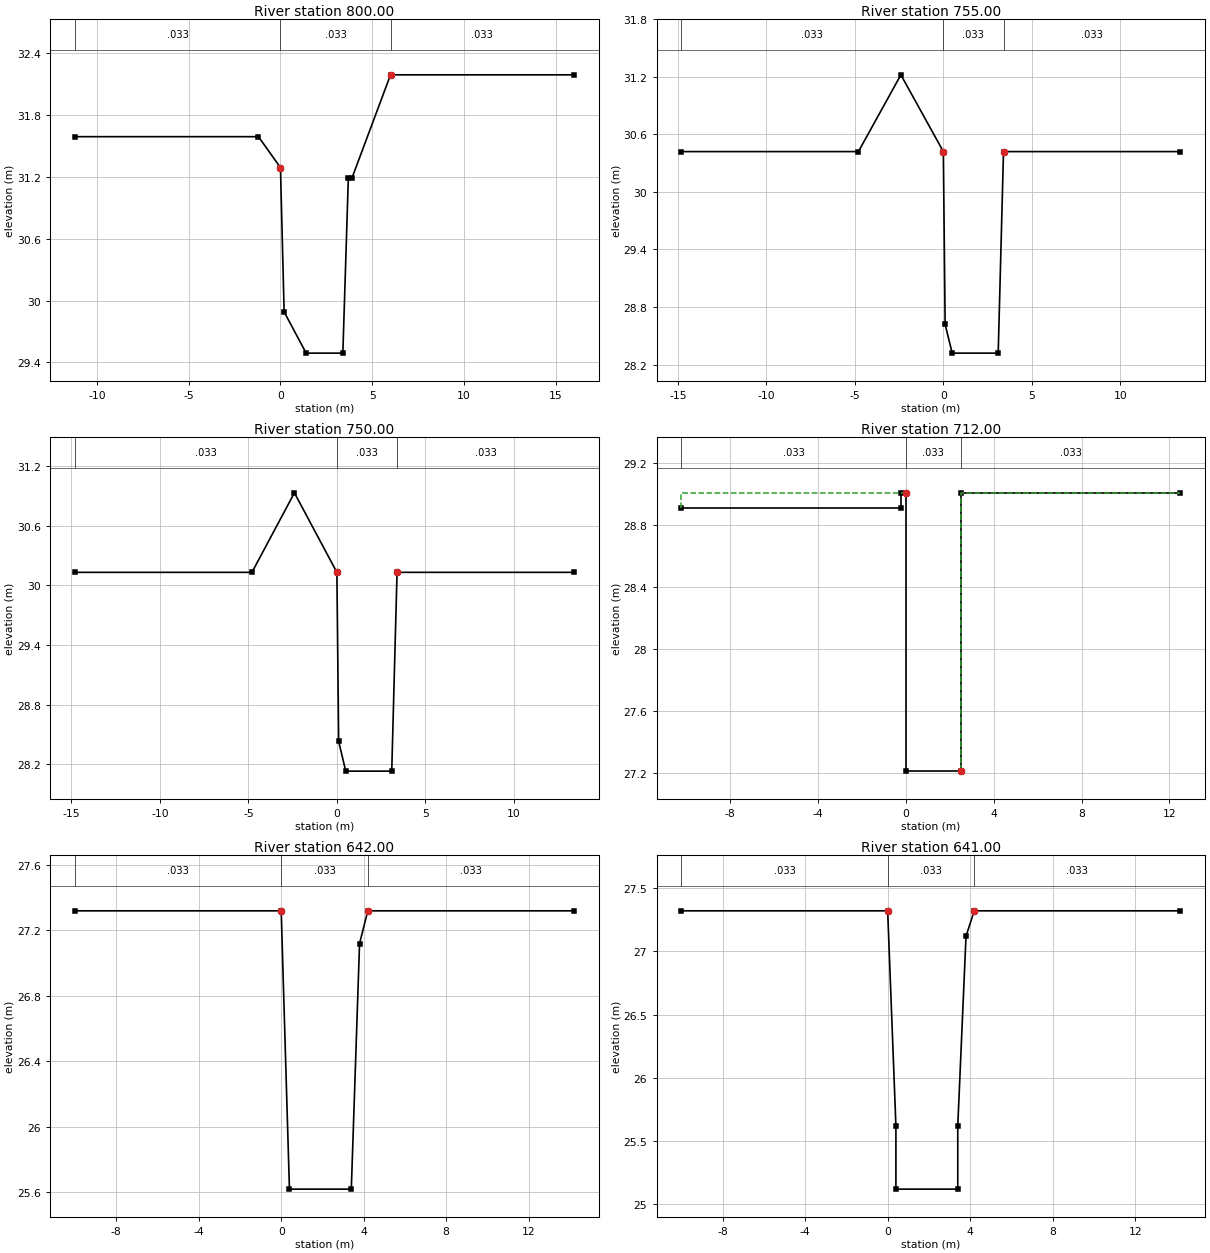
Type RM Length L Ch R = 1 ,800.00  ,45,45,45
BEGIN DESCRIPTION:
16
END DESCRIPTION:
#Sta/Elev= 10
   -11.2   31.59    -1.2   31.59       0   31.29      .2   29.89     1.4   29.49
     3.4   29.49     3.7   31.19     3.9   31.19       6   32.19      16   32.19
#Mann= 3 , 0 , 0
   -11.2    .033       0       0    .033       0       6    .033       0
#XS Ineff= 2 , 0
               0   31.29       6           32.19
Permanent Ineff=
       F       F
Bank Sta=0,6
XS Rating Curve= 0
Exp/Cntr=.3,.1

Type RM Length L Ch R = 1 ,755.00  ,5,5,5
BEGIN DESCRIPTION:
15.005
END DESCRIPTION:
#Sta/Elev= 9
   -14.8   30.42    -4.8   30.42    -2.4   31.22       0   30.42      .1   28.62
      .5   28.32     3.1   28.32     3.4   30.42    13.4   30.42
#Mann= 3 , 0 , 0
   -14.8    .033       0       0    .033       0     3.4    .033       0
#XS Ineff= 2 , 0
               0   30.42     3.4           30.42
Permanent Ineff=
       F       F
Bank Sta=0,3.4
XS Rating Curve= 0
Exp/Cntr=.3,.1

Type RM Length L Ch R = 1 ,750.00  ,38,38,38
BEGIN DESCRIPTION:
15
END DESCRIPTION:
#Sta/Elev= 9
   -14.8   30.13    -4.8   30.13    -2.4   30.93       0   30.13      .1   28.43
      .5   28.13     3.1   28.13     3.4   30.13    13.4   30.13
#Mann= 3 , 0 , 0
   -14.8    .033       0       0    .033       0     3.4    .033       0
#XS Ineff= 2 , 0
               0   30.13     3.4           30.13
Permanent Ineff=
       F       F
Bank Sta=0,3.4
XS Rating Curve= 0
Exp/Cntr=.3,.1

Type RM Length L Ch R = 1 ,712.00  ,70,70,70
BEGIN DESCRIPTION:
14.012
END DESCRIPTION:
#Sta/Elev= 8
   -10.2   28.91     -.2   28.91     -.2   29.01       0   29.01       0   27.21
     2.5   27.21     2.5   29.01    12.5   29.01
#Mann= 3 , 0 , 0
   -10.2    .033       0       0    .033       0     2.5    .033       0
#XS Ineff= 2 , 0
               0   29.01     2.5           29.01
Permanent Ineff=
       F       F
Bank Sta=0,2.5
XS Rating Curve= 0
Exp/Cntr=.3,.1

Type RM Length L Ch R = 1 ,642.00  ,1,1,1
BEGIN DESCRIPTION:
12.042
END DESCRIPTION:
#Sta/Elev= 7
     -10   27.32       0   27.32      .4   25.62     3.4   25.62     3.8   27.12
     4.2   27.32    14.2   27.32
#Mann= 3 , 0 , 0
     -10    .033       0       0    .033       0     4.2    .033       0
#XS Ineff= 2 , 0
               0   27.32     4.2           27.32
Permanent Ineff=
       F       F
Bank Sta=0,4.2
XS Rating Curve= 0
Exp/Cntr=.3,.1

Type RM Length L Ch R = 1 ,641.00  ,41,41,41
BEGIN DESCRIPTION:
12.041
END DESCRIPTION:
#Sta/Elev= 9
     -10   27.32       0   27.32      .4   25.62      .4   25.12     3.4   25.12
     3.4   25.62     3.8   27.12     4.2   27.32    14.2   27.32
#Mann= 3 , 0 , 0
     -10    .033       0       0    .033       0     4.2    .033       0
#XS Ineff= 2 , 0
               0   27.32     4.2           27.32
Permanent Ineff=
       F       F
Bank Sta=0,4.2
XS Rating Curve= 0
Exp/Cntr=.3,.1