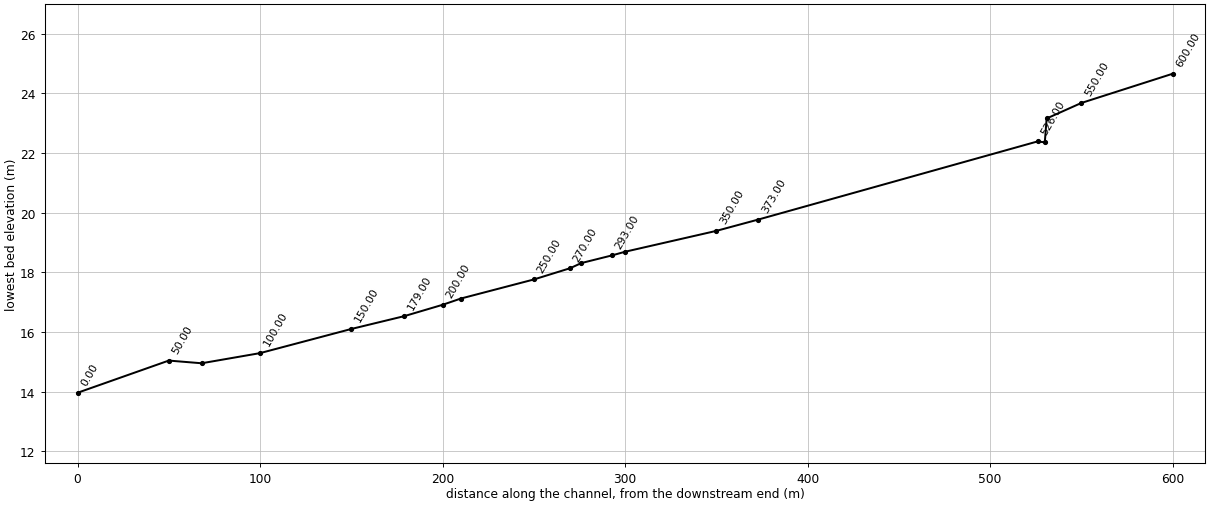
HEC-RAS study HGC.prj: HGC

--- HGC.g01 (geometry) --- (continued)

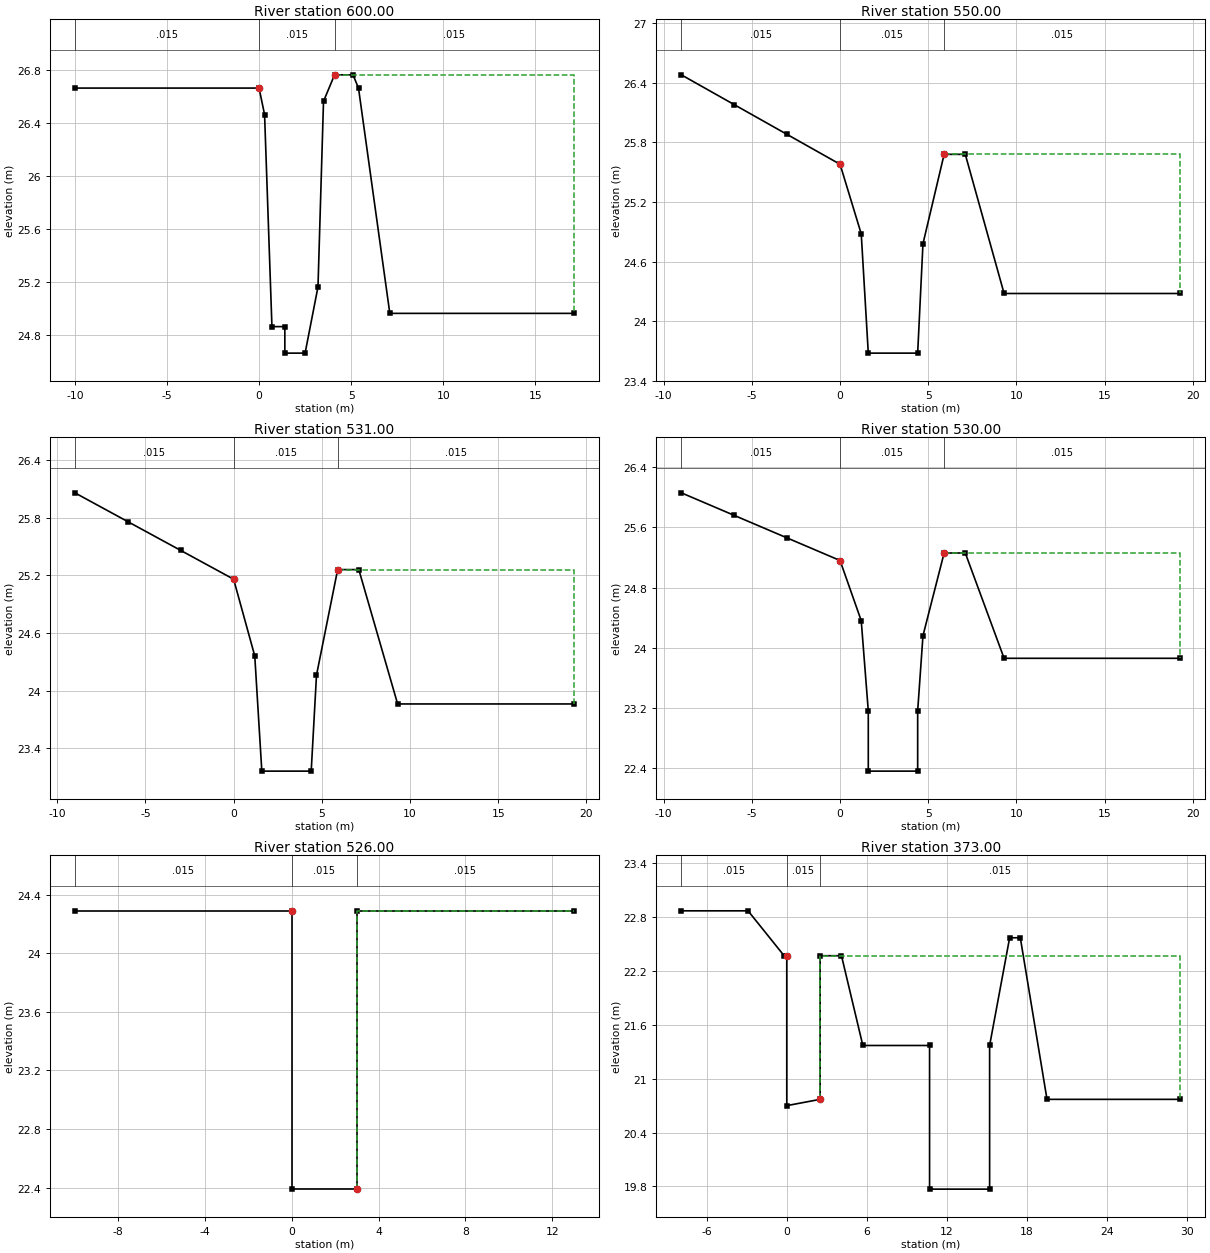
Type RM Length L Ch R = 1 ,600.00  ,50,50,50
BEGIN DESCRIPTION:
12
END DESCRIPTION:
#Sta/Elev= 14
     -10   26.66       0   26.66      .3   26.46      .7   24.86     1.4   24.86
     1.4   24.66     2.5   24.66     3.2   25.16     3.5   26.56     4.1   26.76
     5.1   26.76     5.4   26.66     7.1   24.96    17.1   24.96
#Mann= 3 , 0 , 0
     -10    .015       0       0    .015       0     4.1    .015       0
#XS Ineff= 2 , 0
               0   26.66     4.1           26.76
Permanent Ineff=
       F       F
Bank Sta=0,4.1
XS Rating Curve= 0
Exp/Cntr=.3,.1

Type RM Length L Ch R = 1 ,550.00  ,19,19,19
BEGIN DESCRIPTION:
11
END DESCRIPTION:
#Sta/Elev= 12
      -9   26.48      -6   26.18      -3   25.88       0   25.58     1.2   24.88
     1.6   23.68     4.4   23.68     4.7   24.78     5.9   25.68     7.1   25.68
     9.3   24.28    19.3   24.28
#Mann= 3 , 0 , 0
      -9    .015       0       0    .015       0     5.9    .015       0
#XS Ineff= 2 , 0
               0   25.58     5.9           25.68
Permanent Ineff=
       F       F
Bank Sta=0,5.9
XS Rating Curve= 0
Exp/Cntr=.3,.1

Type RM Length L Ch R = 1 ,531.00  ,1,1,1
BEGIN DESCRIPTION:
10.031
END DESCRIPTION:
#Sta/Elev= 12
      -9   26.06      -6   25.76      -3   25.46       0   25.16     1.2   24.36
     1.6   23.16     4.4   23.16     4.7   24.16     5.9   25.26     7.1   25.26
     9.3   23.86    19.3   23.86
#Mann= 3 , 0 , 0
      -9    .015       0       0    .015       0     5.9    .015       0
#XS Ineff= 2 , 0
               0   25.16     5.9           25.26
Permanent Ineff=
       F       F
Bank Sta=0,5.9
XS Rating Curve= 0
Exp/Cntr=.3,.1

Type RM Length L Ch R = 1 ,530.00  ,4,4,4
BEGIN DESCRIPTION:
10.03
END DESCRIPTION:
#Sta/Elev= 14
      -9   26.06      -6   25.76      -3   25.46       0   25.16     1.2   24.36
     1.6   23.16     1.6   22.36     4.4   22.36     4.4   23.16     4.7   24.16
     5.9   25.26     7.1   25.26     9.3   23.86    19.3   23.86
#Mann= 3 , 0 , 0
      -9    .015       0       0    .015       0     5.9    .015       0
#XS Ineff= 2 , 0
               0   25.16     5.9           25.26
Permanent Ineff=
       F       F
Bank Sta=0,5.9
XS Rating Curve= 0
Exp/Cntr=.3,.1

Type RM Length L Ch R = 1 ,526.00  ,153,153,153
BEGIN DESCRIPTION:
10.026
END DESCRIPTION:
#Sta/Elev= 6
     -10   24.29       0   24.29       0   22.39       3   22.39       3   24.29
      13   24.29
#Mann= 3 , 0 , 0
     -10    .015       0       0    .015       0       3    .015       0
#XS Ineff= 2 , 0
               0   24.29       3           24.29
Permanent Ineff=
       F       F
Bank Sta=0,3
XS Rating Curve= 0
Exp/Cntr=.3,.1

Type RM Length L Ch R = 1 ,373.00  ,23,23,23
BEGIN DESCRIPTION:
7.023
END DESCRIPTION:
#Sta/Elev= 17
    -7.9   22.87    -2.9   22.87     -.2   22.37       0   22.37       0    20.7
     2.5   20.77     2.5   22.37     4.1   22.37     5.7   21.37    10.7   21.37
    10.7   19.77    15.2   19.77    15.2   21.37    16.7   22.57    17.5   22.57
    19.5   20.77    29.5   20.77
#Mann= 3 , 0 , 0
    -7.9    .015       0       0    .015       0     2.5    .015       0
#XS Ineff= 2 , 0
               0   22.37     2.5           22.37
Permanent Ineff=
       F       F
Bank Sta=0,2.5
XS Rating Curve= 0
Exp/Cntr=.3,.1

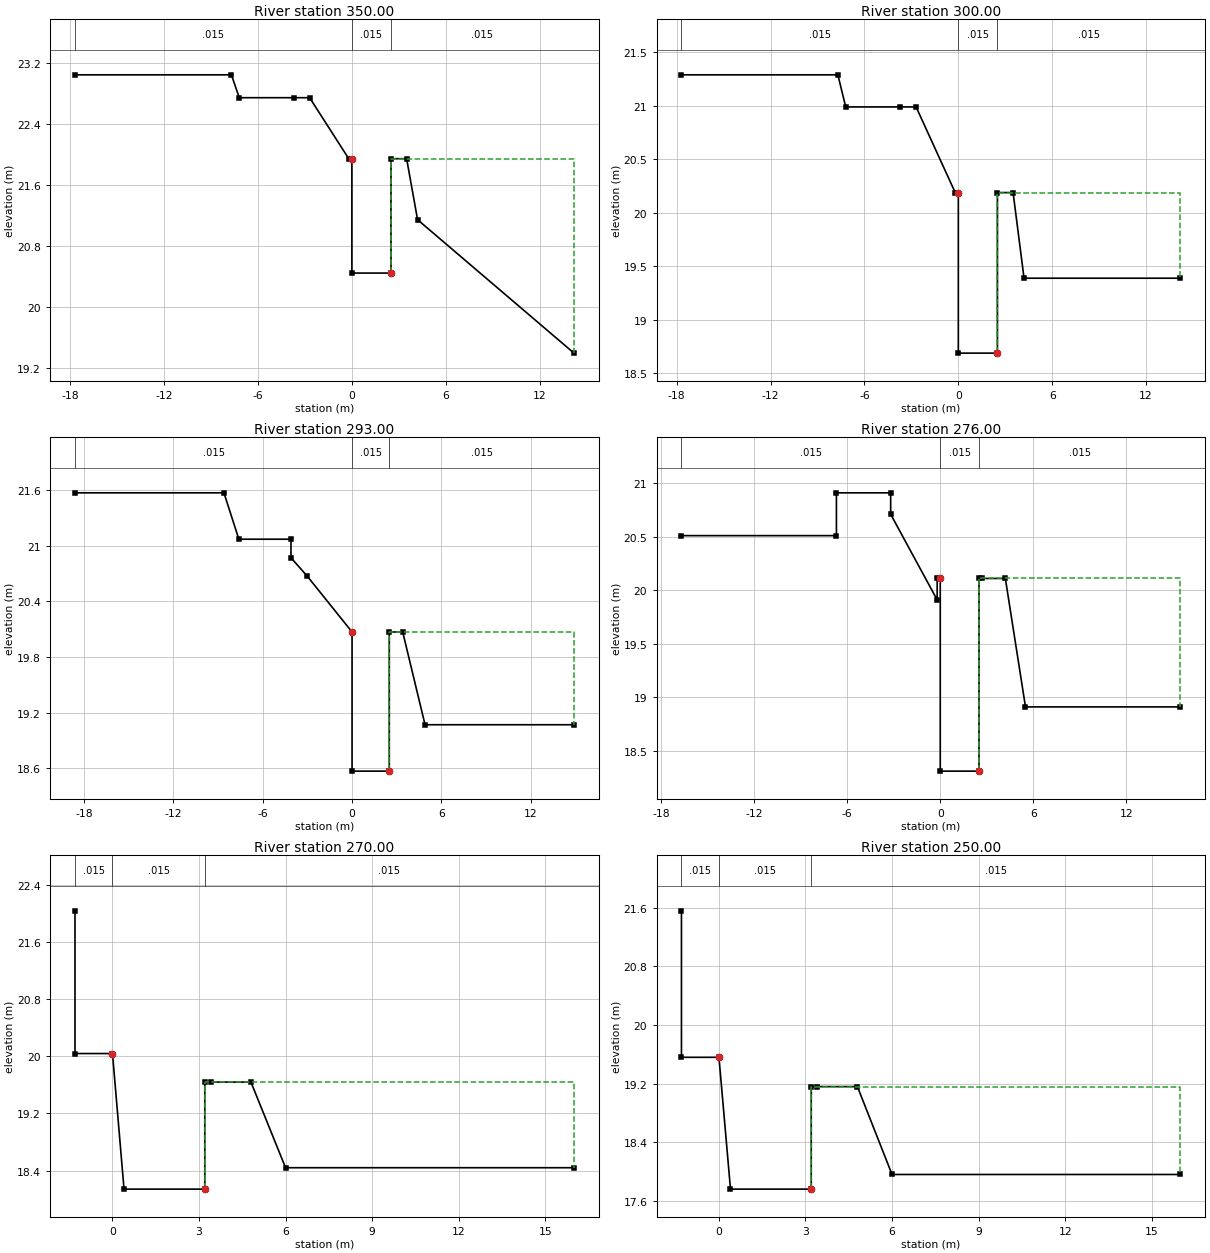
Type RM Length L Ch R = 1 ,350.00  ,50,50,50
BEGIN DESCRIPTION:
7
END DESCRIPTION:
#Sta/Elev= 13
   -17.7   23.04    -7.7   23.04    -7.2   22.74    -3.7   22.74    -2.7   22.74
     -.2   21.94       0   21.94       0   20.44     2.5   20.44     2.5   21.94
     3.5   21.94     4.2   21.14    14.2   19.39
#Mann= 3 , 0 , 0
   -17.7    .015       0       0    .015       0     2.5    .015       0
#XS Ineff= 2 , 0
               0   21.94     2.5           21.94
Permanent Ineff=
       F       F
Bank Sta=0,2.5
XS Rating Curve= 0
Exp/Cntr=.3,.1

Type RM Length L Ch R = 1 ,300.00  ,7,7,7
BEGIN DESCRIPTION:
6
END DESCRIPTION:
#Sta/Elev= 13
   -17.7   21.29    -7.7   21.29    -7.2   20.99    -3.7   20.99    -2.7   20.99
     -.2   20.19       0   20.19       0   18.69     2.5   18.69     2.5   20.19
     3.5   20.19     4.2   19.39    14.2   19.39
#Mann= 3 , 0 , 0
   -17.7    .015       0       0    .015       0     2.5    .015       0
#XS Ineff= 2 , 0
               0   20.19     2.5           20.19
Permanent Ineff=
       F       F
Bank Sta=0,2.5
XS Rating Curve= 0
Exp/Cntr=.3,.1

Type RM Length L Ch R = 1 ,293.00  ,17,17,17
BEGIN DESCRIPTION:
5.043
END DESCRIPTION:
#Sta/Elev= 13
   -18.6   21.57    -8.6   21.57    -7.6   21.07    -4.1   21.07    -4.1   20.87
      -3   20.67       0   20.07       0   18.57     2.5   18.57     2.5   20.07
     3.4   20.07     4.9   19.07    14.9   19.07
#Mann= 3 , 0 , 0
   -18.6    .015       0       0    .015       0     2.5    .015       0
#XS Ineff= 2 , 0
               0   20.07     2.5           20.07
Permanent Ineff=
       F       F
Bank Sta=0,2.5
XS Rating Curve= 0
Exp/Cntr=.3,.1

Type RM Length L Ch R = 1 ,276.00  ,6,6,6
BEGIN DESCRIPTION:
5.026
END DESCRIPTION:
#Sta/Elev= 15
   -16.7   20.51    -6.7   20.51    -6.7   20.91    -3.2   20.91    -3.2   20.71
     -.2   19.91     -.2   20.11       0   20.11       0   18.31     2.5   18.31
     2.5   20.11     2.7   20.11     4.2   20.11     5.5   18.91    15.5   18.91
#Mann= 3 , 0 , 0
   -16.7    .015       0       0    .015       0     2.5    .015       0
#XS Ineff= 2 , 0
               0   20.11     2.5           20.11
Permanent Ineff=
       F       F
Bank Sta=0,2.5
XS Rating Curve= 0
Exp/Cntr=.3,.1

Type RM Length L Ch R = 1 ,270.00  ,20,20,20
BEGIN DESCRIPTION:
5.02
END DESCRIPTION:
#Sta/Elev= 10
    -1.3   22.04    -1.3   20.04       0   20.04      .4   18.14     3.2   18.14
     3.2   19.64     3.4   19.64     4.8   19.64       6   18.44      16   18.44
#Mann= 3 , 0 , 0
    -1.3    .015       0       0    .015       0     3.2    .015       0
#XS Ineff= 2 , 0
               0   20.04     3.2           19.64
Permanent Ineff=
       F       F
Bank Sta=0,3.2
XS Rating Curve= 0
Exp/Cntr=.3,.1

Type RM Length L Ch R = 1 ,250.00  ,40,40,40
BEGIN DESCRIPTION:
5
END DESCRIPTION:
#Sta/Elev= 10
    -1.3   21.56    -1.3   19.56       0   19.56      .4   17.76     3.2   17.76
     3.2   19.16     3.4   19.16     4.8   19.16       6   17.96      16   17.96
#Mann= 3 , 0 , 0
    -1.3    .015       0       0    .015       0     3.2    .015       0
#XS Ineff= 2 , 0
               0   19.56     3.2           19.16
Permanent Ineff=
       F       F
Bank Sta=0,3.2
XS Rating Curve= 0
Exp/Cntr=.3,.1

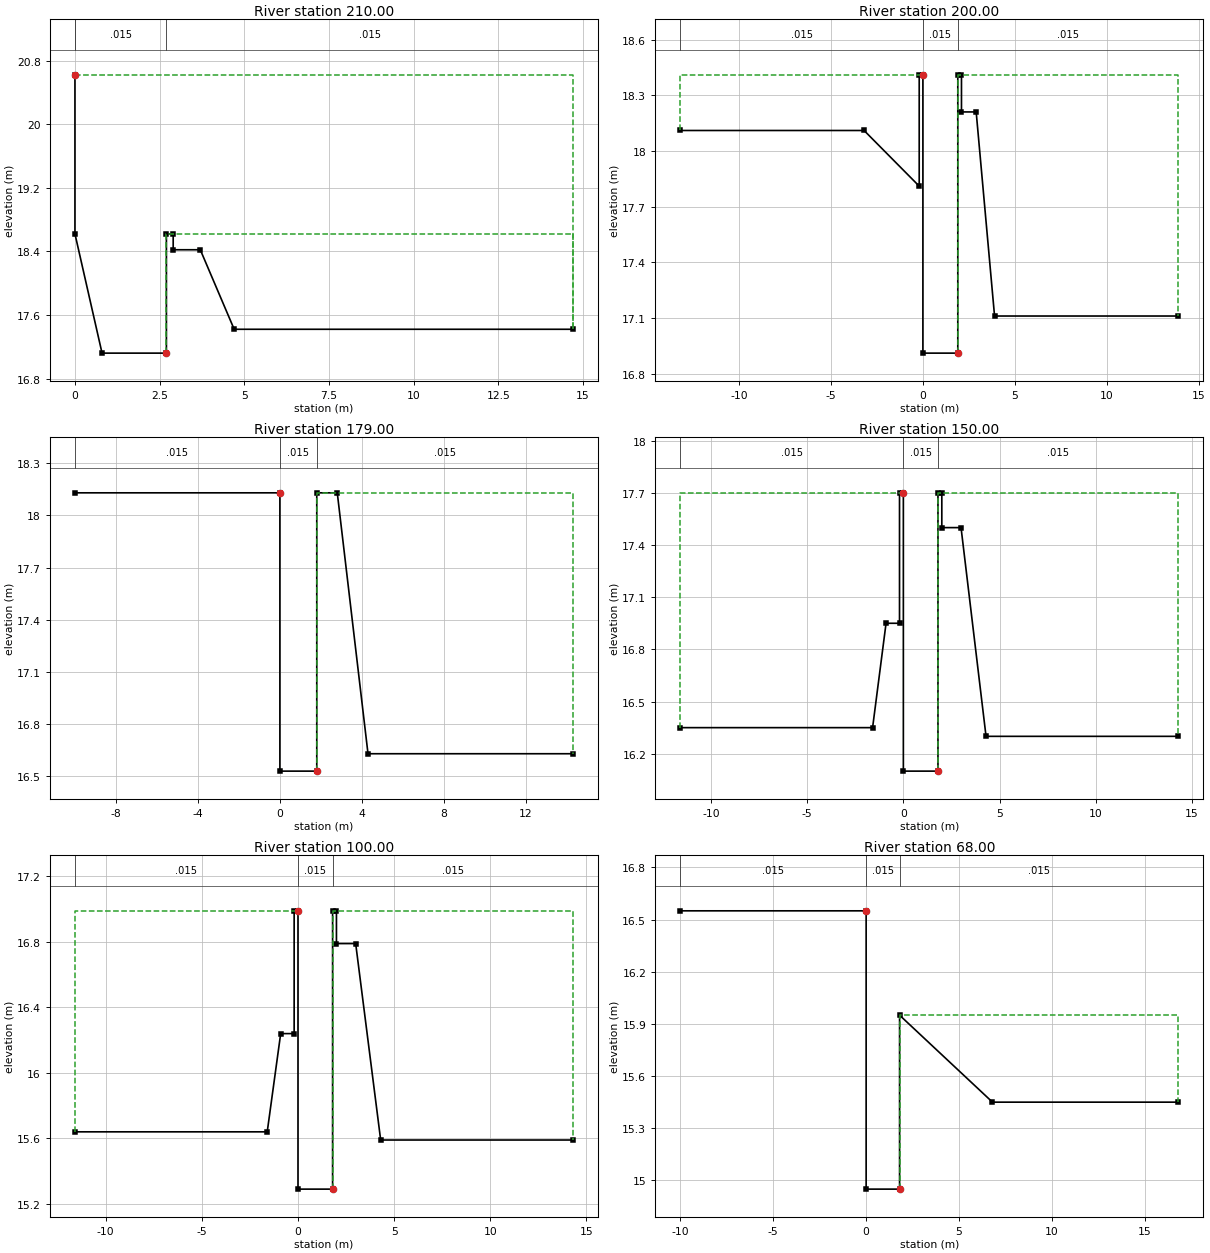
Type RM Length L Ch R = 1 ,210.00  ,10,10,10
BEGIN DESCRIPTION:
4.01
END DESCRIPTION:
#Sta/Elev= 10
       0   20.62       0   18.62      .8   17.12     2.7   17.12     2.7   18.62
     2.9   18.62     2.9   18.42     3.7   18.42     4.7   17.42    14.7   17.42
#Mann= 3 , 0 , 0
       0    .015       0       0    .015       0     2.7    .015       0
#XS Ineff= 2 , 0
               0   20.62     2.7           18.62
Permanent Ineff=
       F       F
Bank Sta=0,2.7
XS Rating Curve= 0
Exp/Cntr=.3,.1

Type RM Length L Ch R = 1 ,200.00  ,21,21,21
BEGIN DESCRIPTION:
4
END DESCRIPTION:
#Sta/Elev= 13
   -13.2   18.11    -3.2   18.11     -.2   17.81     -.2   18.41       0   18.41
       0   16.91     1.9   16.91     1.9   18.41     2.1   18.41     2.1   18.21
     2.9   18.21     3.9   17.11    13.9   17.11
#Mann= 3 , 0 , 0
   -13.2    .015       0       0    .015       0     1.9    .015       0
#XS Ineff= 2 , 0
               0   18.41     1.9           18.41
Permanent Ineff=
       F       F
Bank Sta=0,1.9
XS Rating Curve= 0
Exp/Cntr=.3,.1

Type RM Length L Ch R = 1 ,179.00  ,29,29,29
BEGIN DESCRIPTION:
3.029
END DESCRIPTION:
#Sta/Elev= 8
     -10   18.13       0   18.13       0   16.53     1.8   16.53     1.8   18.13
     2.8   18.13     4.3   16.63    14.3   16.63
#Mann= 3 , 0 , 0
     -10    .015       0       0    .015       0     1.8    .015       0
#XS Ineff= 2 , 0
               0   18.13     1.8           18.13
Permanent Ineff=
       F       F
Bank Sta=0,1.8
XS Rating Curve= 0
Exp/Cntr=.3,.1

Type RM Length L Ch R = 1 ,150.00  ,50,50,50
BEGIN DESCRIPTION:
3
END DESCRIPTION:
#Sta/Elev= 14
   -11.6   16.35    -1.6   16.35     -.9   16.95     -.2   16.95     -.2    17.7
       0    17.7       0    16.1     1.8    16.1     1.8    17.7       2    17.7
       2    17.5       3    17.5     4.3    16.3    14.3    16.3
#Mann= 3 , 0 , 0
   -11.6    .015       0       0    .015       0     1.8    .015       0
#XS Ineff= 2 , 0
               0    17.7     1.8            17.7
Permanent Ineff=
       F       F
Bank Sta=0,1.8
XS Rating Curve= 0
Exp/Cntr=.3,.1

Type RM Length L Ch R = 1 ,100.00  ,32,32,32
BEGIN DESCRIPTION:
2
END DESCRIPTION:
#Sta/Elev= 14
   -11.6   15.64    -1.6   15.64     -.9   16.24     -.2   16.24     -.2   16.99
       0   16.99       0   15.29     1.8   15.29     1.8   16.99       2   16.99
       2   16.79       3   16.79     4.3   15.59    14.3   15.59
#Mann= 3 , 0 , 0
   -11.6    .015       0       0    .015       0     1.8    .015       0
#XS Ineff= 2 , 0
               0   16.99     1.8           16.99
Permanent Ineff=
       F       F
Bank Sta=0,1.8
XS Rating Curve= 0
Exp/Cntr=.3,.1

Type RM Length L Ch R = 1 ,68.00   ,18,18,18
BEGIN DESCRIPTION:
1.018
END DESCRIPTION:
#Sta/Elev= 7
     -10   16.55       0   16.55       0   14.95     1.8   14.95     1.8   15.95
     6.8   15.45    16.8   15.45
#Mann= 3 , 0 , 0
     -10    .015       0       0    .015       0     1.8    .015       0
#XS Ineff= 2 , 0
               0   16.55     1.8           15.95
Permanent Ineff=
       F       F
Bank Sta=0,1.8
XS Rating Curve= 0
Exp/Cntr=.3,.1

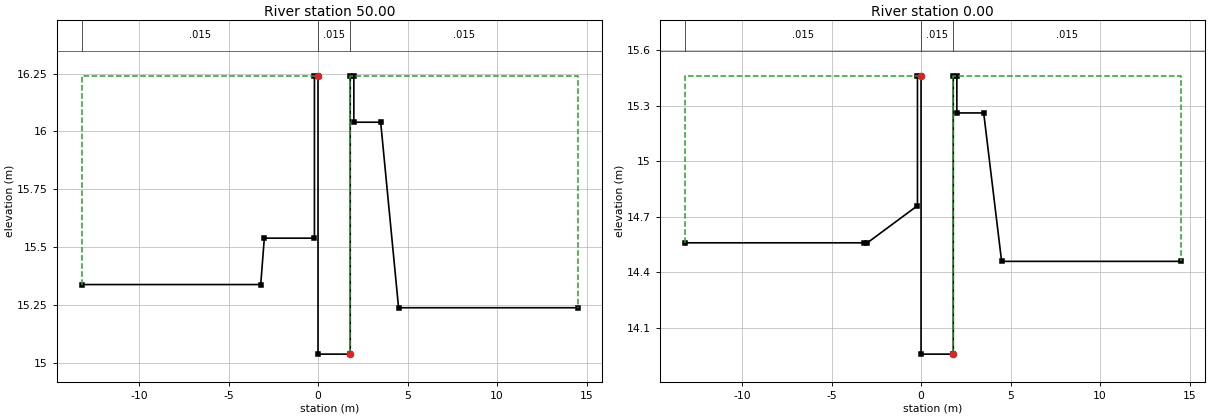
Type RM Length L Ch R = 1 ,50.00   ,50,50,50
BEGIN DESCRIPTION:
1
END DESCRIPTION:
#Sta/Elev= 14
   -13.2   15.34    -3.2   15.34      -3   15.54     -.2   15.54     -.2   16.24
       0   16.24       0   15.04     1.8   15.04     1.8   16.24       2   16.24
       2   16.04     3.5   16.04     4.5   15.24    14.5   15.24
#Mann= 3 , 0 , 0
   -13.2    .015       0       0    .015       0     1.8    .015       0
#XS Ineff= 2 , 0
               0   16.24     1.8           16.24
Permanent Ineff=
       F       F
Bank Sta=0,1.8
XS Rating Curve= 0
Exp/Cntr=.3,.1

Type RM Length L Ch R = 1 ,0.00    ,0,0,0
BEGIN DESCRIPTION:
0
END DESCRIPTION:
#Sta/Elev= 14
   -13.2   14.56    -3.2   14.56      -3   14.56     -.2   14.76     -.2   15.46
       0   15.46       0   13.96     1.8   13.96     1.8   15.46       2   15.46
       2   15.26     3.5   15.26     4.5   14.46    14.5   14.46
#Mann= 3 , 0 , 0
   -13.2    .015       0       0    .015       0     1.8    .015       0
#XS Ineff= 2 , 0
               0   15.46     1.8           15.46
Permanent Ineff=
       F       F
Bank Sta=0,1.8
XS Rating Curve= 0
Exp/Cntr=.3,.1

Chan Stop Cuts=-1