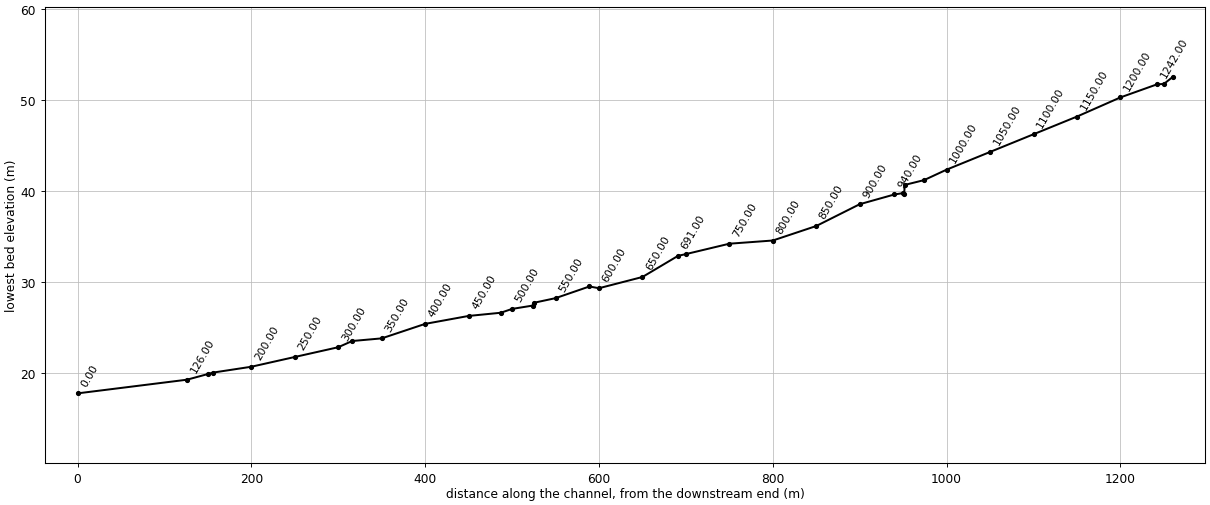
--- SONG.prj (project) ---

Proj Title=SONG
Current Plan=p01
Default Exp/Contr=.3,.1
SI Units
Geom File=g01
Flow File=f01
Plan File=p01
Y Axis Title=Elevation
X Axis Title(PF)=Main Channel Distance
X Axis Title(XS)=Station
BEGIN DESCRIPTION:
           BACK WATER COMPUTATION
      APPLICATION OF HEC-2 BY Samju Construction Engineering
      SONGJUNG-STREEM : 30 YR
END DESCRIPTION:
DSS Export Rating Curves= 0
DSS Export Rating Curve Sorted= 0
DSS Export Volume Flow Curves= 0
DXF OffsetX= 0
DXF OffsetY= 0
DXF ScaleX= 1
DXF ScaleY= 10

--- SONG.p01 (plan) ---

Plan Title=Imported Plan 01
Version=Version 3.0.1  Mar 2001
Short Identifier=Imported Pla
Geom File=g01
Flow File=f01
Subcritical Flow
K Sum by GR= 0
Std Step Tol= 0.003
Critical Tol= 0.003
Num of Std Step Trials= 20
Max Error Tol= 0.1
Flow Tol Ratio= 0.001
Split Flow NTrial= 30
Split Flow Tol= 0.02
Split Flow Ratio= 0.02
Log Output Level= 0
Friction Slope Method= 1
Unsteady Friction Slope Method= 2
Parabolic Critical Depth
Global Vel Dist= 0 , 0 , 0
Global Log Level= 0
CheckData=True
Encroach Param=-1 ,0,0, 0
Computation Interval=1HOUR
Output Interval=1HOUR
Run HTab= 0
Run UNet= 0
Run PostProcess= 0
UNET Theta= 1
UNET ZTol= 0.02
UNET ZSATol= 0.1
UNET MxIter= 20
UNET MaxInSteps= 20
UNET DtIC= 0
UNET DtMin= 0
UNET MaxCRTS= 20
UNET WFStab= 2
UNET SFStab= 1
UNET WFX= 1
UNET SFX= 1
UNET Convert EG Bridges=-1
UNET Use Existing IB Tables=-1
Instantaneous Interval=1HOUR
Write IC File= 0
Write Velocity= 0
Write Detailed= 0

--- SONG.f01 (steady flow) ---

Flow Title=Imported Flow 01
Version=Version 3.0.1  Mar 2001
Number of Profiles= 5
Profile Names=10YR,20YR,30YR,50YR,80YR
River Rch & RM=RIVER-1,Reach-1         ,25.01
    8.35     9.2     9.7   10.32    10.9
River Rch & RM=SONGJUNG,SONGJUNG        ,1260.00
    8.35     9.2     9.7   10.32    10.9
Boundary for River Rch & Prof#=SONGJUNG,SONGJUNG        , 1
Up Type= 0
Dn Type= 3
Dn Slope=.028
Boundary for River Rch & Prof#=SONGJUNG,SONGJUNG        , 2
Up Type= 0
Dn Type= 3
Dn Slope=.028
Boundary for River Rch & Prof#=SONGJUNG,SONGJUNG        , 3
Up Type= 0
Dn Type= 3
Dn Slope=.028
Boundary for River Rch & Prof#=SONGJUNG,SONGJUNG        , 4
Up Type= 0
Dn Type= 3
Dn Slope=.028
Boundary for River Rch & Prof#=SONGJUNG,SONGJUNG        , 5
Up Type= 0
Dn Type= 3
Dn Slope=.028
DSS Import GetInterval= 0
DSS Import GetPeak= 0
DSS Import FillOption= 0

--- SONG.g01 (geometry) ---

Geom Title=Imported Geom 01
Version=Version 3.0.1  Mar 2001

River Reach=SONGJUNG        ,SONGJUNG
Reach XY= 2
              .5             .95              .5             .05

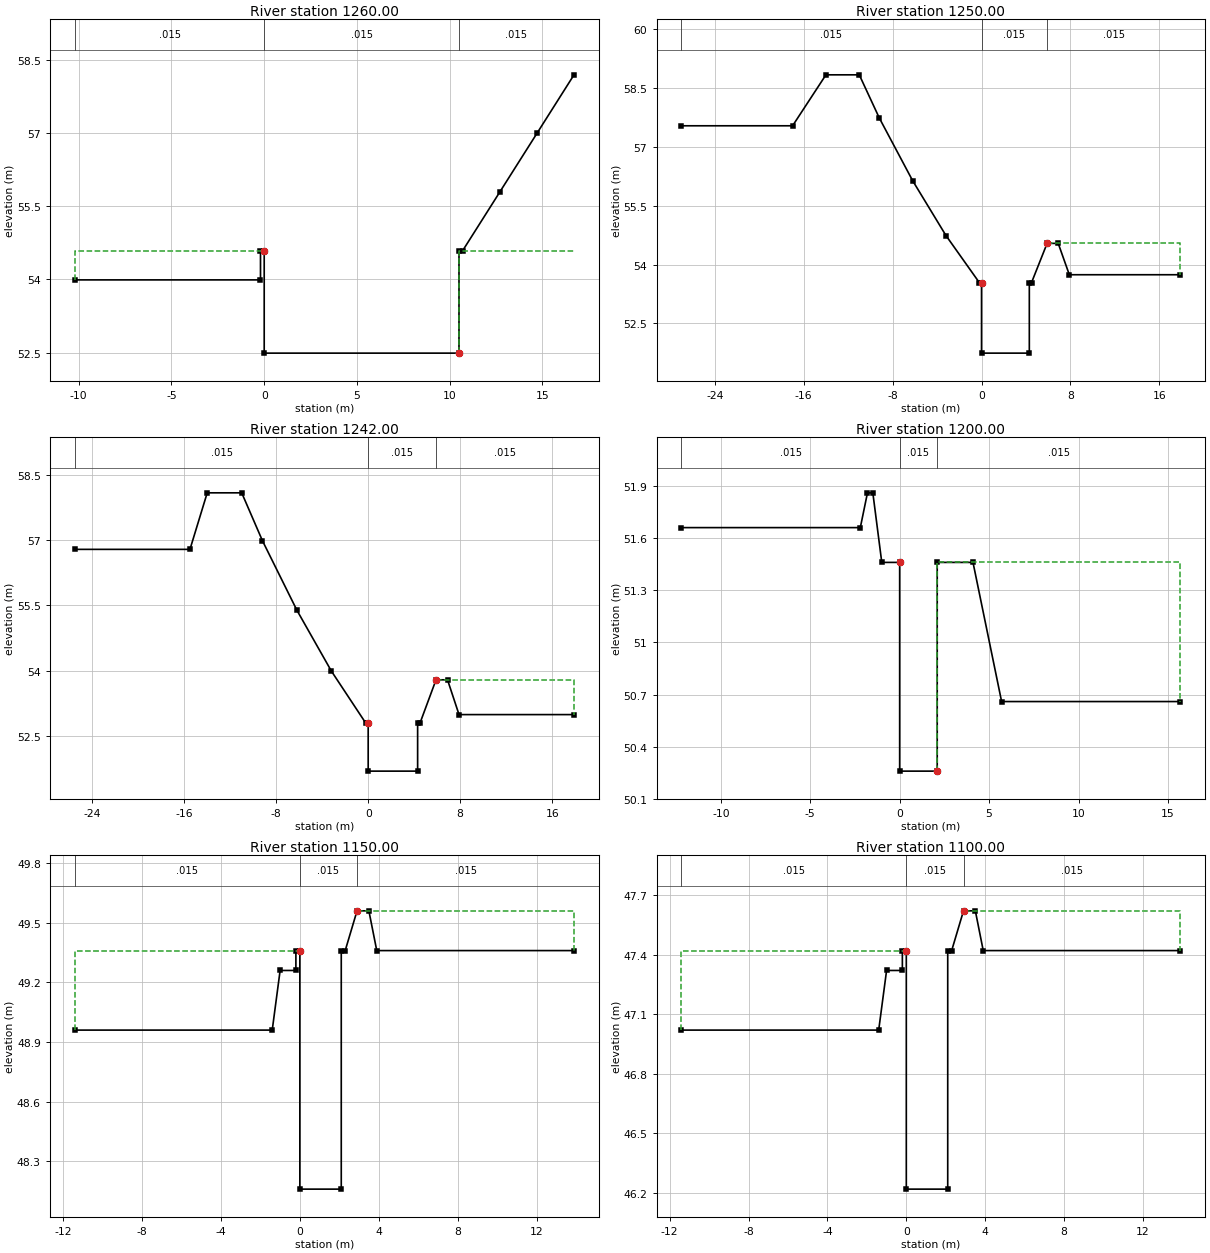
Type RM Length L Ch R = 1 ,1260.00 ,10,10,10
BEGIN DESCRIPTION:
25.01
END DESCRIPTION:
#Sta/Elev= 11
   -10.2   53.99     -.2   53.99     -.2   54.59       0   54.59       0   52.49
    10.5   52.49    10.5   54.59    10.7   54.59    12.7   55.79    14.7   56.99
    16.7   58.19
#Mann= 3 , 0 , 0
   -10.2    .015       0       0    .015       0    10.5    .015       0
#XS Ineff= 2 , 0
               0   54.59    10.5           54.59
Permanent Ineff=
       F       F
Bank Sta=0,10.5
XS Rating Curve= 0
Exp/Cntr=.3,.1

Type RM Length L Ch R = 1 ,1250.00 ,8,8,8
BEGIN DESCRIPTION:
25
END DESCRIPTION:
#Sta/Elev= 17
     -27   57.54     -17   57.54     -14   58.84     -11   58.84    -9.2   57.74
    -6.2   56.14    -3.2   54.74     -.2   53.54       0   53.54       0   51.74
     4.3   51.74     4.3   53.54     4.5   53.54     5.9   54.54     6.9   54.54
     7.9   53.74    17.9   53.74
#Mann= 3 , 0 , 0
     -27    .015       0       0    .015       0     5.9    .015       0
#XS Ineff= 2 , 0
               0   53.54     5.9           54.54
Permanent Ineff=
       F       F
Bank Sta=0,5.9
XS Rating Curve= 0
Exp/Cntr=.3,.1

Type RM Length L Ch R = 1 ,1242.00 ,42,42,42
BEGIN DESCRIPTION:
24.042
END DESCRIPTION:
#Sta/Elev= 17
   -25.5   56.79   -15.5   56.79     -14   58.09     -11   58.09    -9.2   56.99
    -6.2   55.39    -3.2   53.99     -.2   52.79       0   52.79       0   51.69
     4.3   51.69     4.3   52.79     4.5   52.79     5.9   53.79     6.9   53.79
     7.9   52.99    17.9   52.99
#Mann= 3 , 0 , 0
   -25.5    .015       0       0    .015       0     5.9    .015       0
#XS Ineff= 2 , 0
               0   52.79     5.9           53.79
Permanent Ineff=
       F       F
Bank Sta=0,5.9
XS Rating Curve= 0
Exp/Cntr=.3,.1

Type RM Length L Ch R = 1 ,1200.00 ,50,50,50
BEGIN DESCRIPTION:
24
END DESCRIPTION:
#Sta/Elev= 12
   -12.2   51.66    -2.2   51.66    -1.8   51.86    -1.5   51.86      -1   51.46
       0   51.46       0   50.26     2.1   50.26     2.1   51.46     4.1   51.46
     5.7   50.66    15.7   50.66
#Mann= 3 , 0 , 0
   -12.2    .015       0       0    .015       0     2.1    .015       0
#XS Ineff= 2 , 0
               0   51.46     2.1           51.46
Permanent Ineff=
       F       F
Bank Sta=0,2.1
XS Rating Curve= 0
Exp/Cntr=.3,.1

Type RM Length L Ch R = 1 ,1150.00 ,50,50,50
BEGIN DESCRIPTION:
23
END DESCRIPTION:
#Sta/Elev= 14
   -11.4   48.96    -1.4   48.96      -1   49.26     -.2   49.26     -.2   49.36
       0   49.36       0   48.16     2.1   48.16     2.1   49.36     2.3   49.36
     2.9   49.56     3.5   49.56     3.9   49.36    13.9   49.36
#Mann= 3 , 0 , 0
   -11.4    .015       0       0    .015       0     2.9    .015       0
#XS Ineff= 2 , 0
               0   49.36     2.9           49.56
Permanent Ineff=
       F       F
Bank Sta=0,2.9
XS Rating Curve= 0
Exp/Cntr=.3,.1

Type RM Length L Ch R = 1 ,1100.00 ,50,50,50
BEGIN DESCRIPTION:
22
END DESCRIPTION:
#Sta/Elev= 14
   -11.4   47.02    -1.4   47.02      -1   47.32     -.2   47.32     -.2   47.42
       0   47.42       0   46.22     2.1   46.22     2.1   47.42     2.3   47.42
     2.9   47.62     3.5   47.62     3.9   47.42    13.9   47.42
#Mann= 3 , 0 , 0
   -11.4    .015       0       0    .015       0     2.9    .015       0
#XS Ineff= 2 , 0
               0   47.42     2.9           47.62
Permanent Ineff=
       F       F
Bank Sta=0,2.9
XS Rating Curve= 0
Exp/Cntr=.3,.1

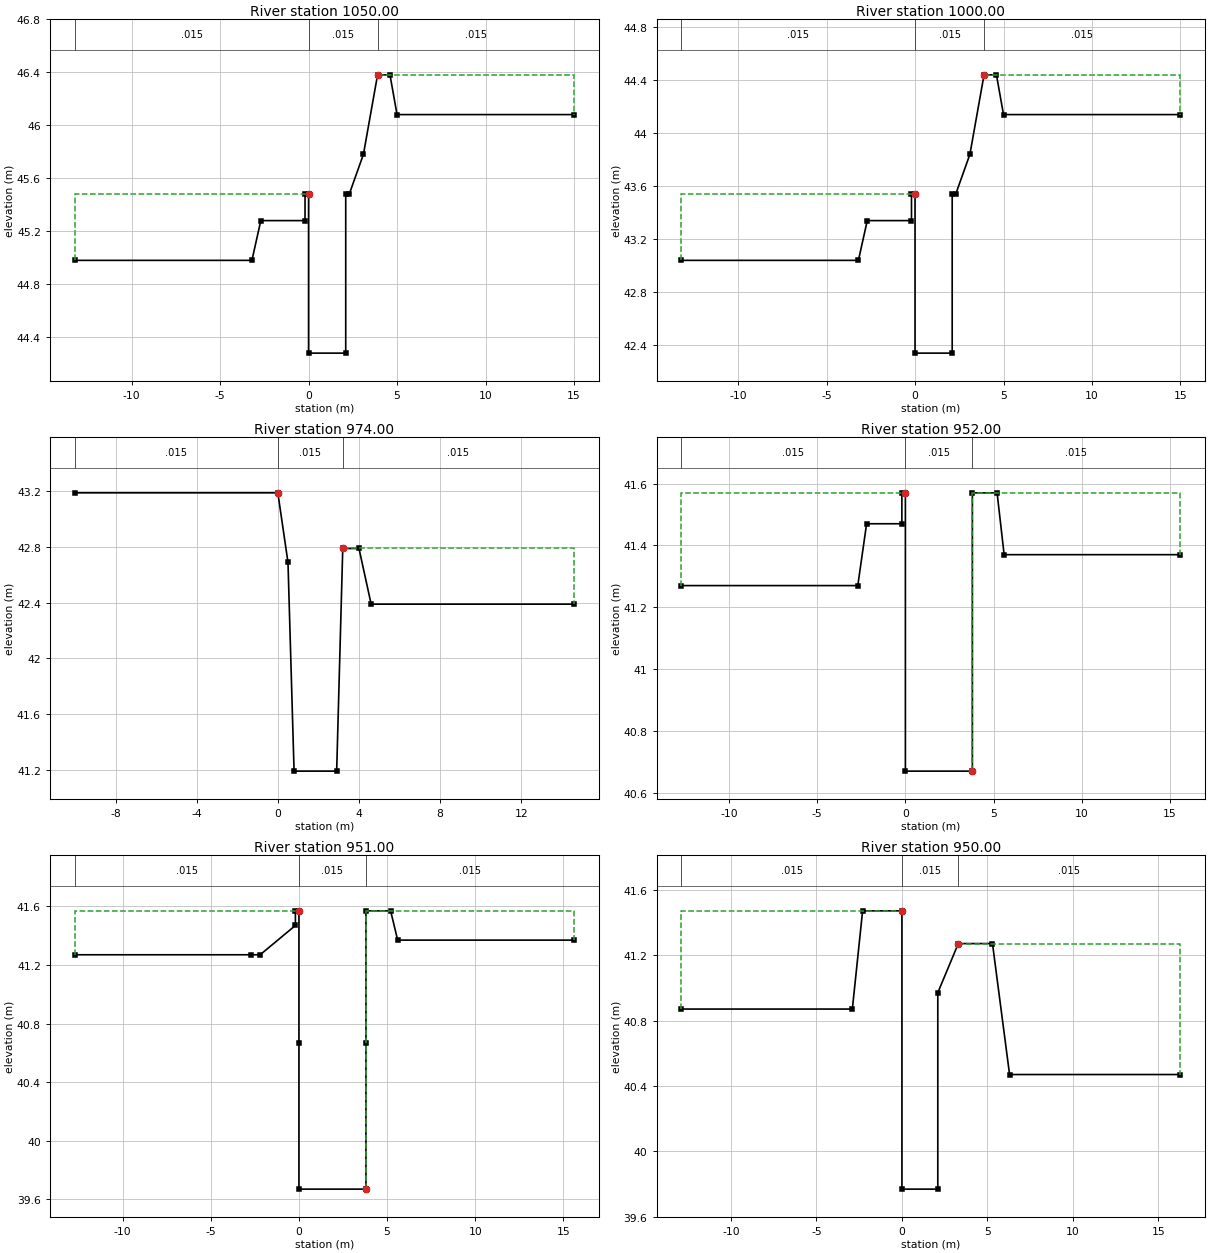
Type RM Length L Ch R = 1 ,1050.00 ,50,50,50
BEGIN DESCRIPTION:
21
END DESCRIPTION:
#Sta/Elev= 15
   -13.2   44.98    -3.2   44.98    -2.7   45.28     -.2   45.28     -.2   45.48
       0   45.48       0   44.28     2.1   44.28     2.1   45.48     2.3   45.48
     3.1   45.78     3.9   46.38     4.6   46.38       5   46.08      15   46.08
#Mann= 3 , 0 , 0
   -13.2    .015       0       0    .015       0     3.9    .015       0
#XS Ineff= 2 , 0
               0   45.48     3.9           46.38
Permanent Ineff=
       F       F
Bank Sta=0,3.9
XS Rating Curve= 0
Exp/Cntr=.3,.1

Type RM Length L Ch R = 1 ,1000.00 ,26,26,26
BEGIN DESCRIPTION:
20
END DESCRIPTION:
#Sta/Elev= 15
   -13.2   43.04    -3.2   43.04    -2.7   43.34     -.2   43.34     -.2   43.54
       0   43.54       0   42.34     2.1   42.34     2.1   43.54     2.3   43.54
     3.1   43.84     3.9   44.44     4.6   44.44       5   44.14      15   44.14
#Mann= 3 , 0 , 0
   -13.2    .015       0       0    .015       0     3.9    .015       0
#XS Ineff= 2 , 0
               0   43.54     3.9           44.44
Permanent Ineff=
       F       F
Bank Sta=0,3.9
XS Rating Curve= 0
Exp/Cntr=.3,.1

Type RM Length L Ch R = 1 ,974.00  ,22,22,22
BEGIN DESCRIPTION:
19.024
END DESCRIPTION:
#Sta/Elev= 9
     -10   43.19       0   43.19      .5   42.69      .8   41.19     2.9   41.19
     3.2   42.79       4   42.79     4.6   42.39    14.6   42.39
#Mann= 3 , 0 , 0
     -10    .015       0       0    .015       0     3.2    .015       0
#XS Ineff= 2 , 0
               0   43.19     3.2           42.79
Permanent Ineff=
       F       F
Bank Sta=0,3.2
XS Rating Curve= 0
Exp/Cntr=.3,.1

Type RM Length L Ch R = 1 ,952.00  ,1,1,1
BEGIN DESCRIPTION:
19.002
END DESCRIPTION:
#Sta/Elev= 12
   -12.7   41.27    -2.7   41.27    -2.2   41.47     -.2   41.47     -.2   41.57
       0   41.57       0   40.67     3.8   40.67     3.8   41.57     5.2   41.57
     5.6   41.37    15.6   41.37
#Mann= 3 , 0 , 0
   -12.7    .015       0       0    .015       0     3.8    .015       0
#XS Ineff= 2 , 0
               0   41.57     3.8           41.57
Permanent Ineff=
       F       F
Bank Sta=0,3.8
XS Rating Curve= 0
Exp/Cntr=.3,.1

Type RM Length L Ch R = 1 ,951.00  ,1,1,1
BEGIN DESCRIPTION:
19.001
END DESCRIPTION:
#Sta/Elev= 14
   -12.7   41.27    -2.7   41.27    -2.2   41.27     -.2   41.47     -.2   41.57
       0   41.57       0   40.67       0   39.67     3.8   39.67     3.8   40.67
     3.8   41.57     5.2   41.57     5.6   41.37    15.6   41.37
#Mann= 3 , 0 , 0
   -12.7    .015       0       0    .015       0     3.8    .015       0
#XS Ineff= 2 , 0
               0   41.57     3.8           41.57
Permanent Ineff=
       F       F
Bank Sta=0,3.8
XS Rating Curve= 0
Exp/Cntr=.3,.1

Type RM Length L Ch R = 1 ,950.00  ,10,10,10
BEGIN DESCRIPTION:
19
END DESCRIPTION:
#Sta/Elev= 11
   -12.9   40.87    -2.9   40.87    -2.3   41.47       0   41.47       0   39.77
     2.1   39.77     2.1   40.97     3.3   41.27     5.3   41.27     6.3   40.47
    16.3   40.47
#Mann= 3 , 0 , 0
   -12.9    .015       0       0    .015       0     3.3    .015       0
#XS Ineff= 2 , 0
               0   41.47     3.3           41.27
Permanent Ineff=
       F       F
Bank Sta=0,3.3
XS Rating Curve= 0
Exp/Cntr=.3,.1

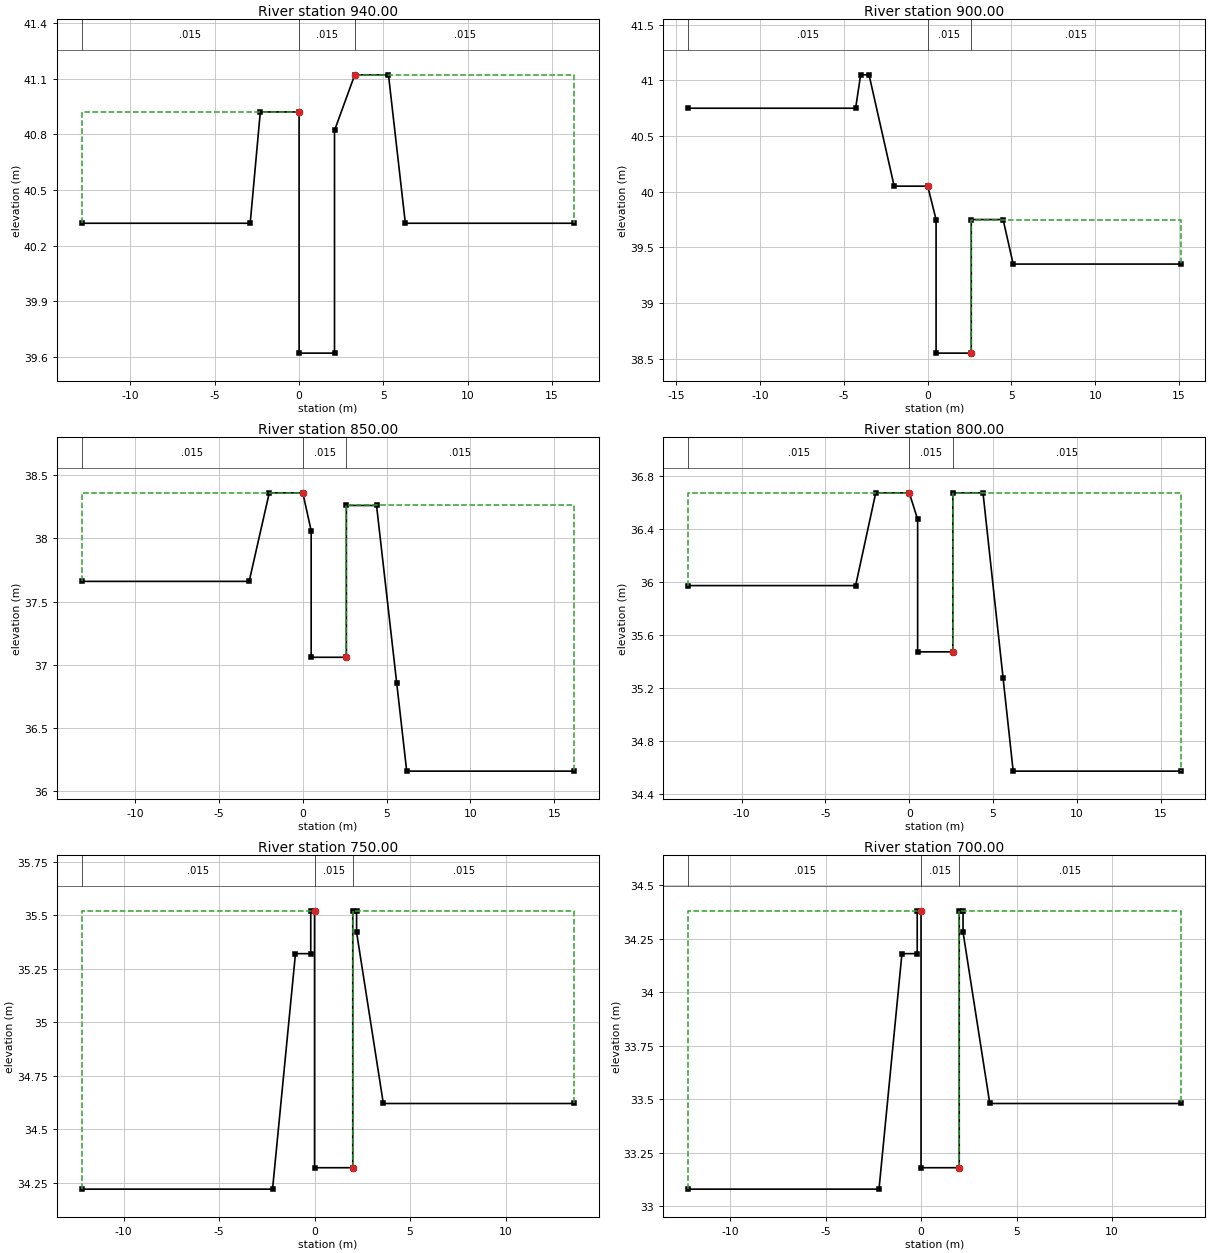
Type RM Length L Ch R = 1 ,940.00  ,40,40,40
BEGIN DESCRIPTION:
18.04
END DESCRIPTION:
#Sta/Elev= 11
   -12.9   40.32    -2.9   40.32    -2.3   40.92       0   40.92       0   39.62
     2.1   39.62     2.1   40.82     3.3   41.12     5.3   41.12     6.3   40.32
   16.32   40.32
#Mann= 3 , 0 , 0
   -12.9    .015       0       0    .015       0     3.3    .015       0
#XS Ineff= 2 , 0
               0   40.92     3.3           41.12
Permanent Ineff=
       F       F
Bank Sta=0,3.3
XS Rating Curve= 0
Exp/Cntr=.3,.1

Type RM Length L Ch R = 1 ,900.00  ,50,50,50
BEGIN DESCRIPTION:
18
END DESCRIPTION:
#Sta/Elev= 13
   -14.3   40.75    -4.3   40.75      -4   41.05    -3.5   41.05      -2   40.05
       0   40.05      .5   39.75      .5   38.55     2.6   38.55     2.6   39.75
     4.5   39.75     5.1   39.35    15.1   39.35
#Mann= 3 , 0 , 0
   -14.3    .015       0       0    .015       0     2.6    .015       0
#XS Ineff= 2 , 0
               0   40.05     2.6           39.75
Permanent Ineff=
       F       F
Bank Sta=0,2.6
XS Rating Curve= 0
Exp/Cntr=.3,.1

Type RM Length L Ch R = 1 ,850.00  ,50,50,50
BEGIN DESCRIPTION:
17
END DESCRIPTION:
#Sta/Elev= 12
   -13.2   37.66    -3.2   37.66      -2   38.36       0   38.36      .5   38.06
      .5   37.06     2.6   37.06     2.6   38.26     4.4   38.26     5.6   36.86
     6.2   36.16    16.2   36.16
#Mann= 3 , 0 , 0
   -13.2    .015       0       0    .015       0     2.6    .015       0
#XS Ineff= 2 , 0
               0   38.36     2.6           38.26
Permanent Ineff=
       F       F
Bank Sta=0,2.6
XS Rating Curve= 0
Exp/Cntr=.3,.1

Type RM Length L Ch R = 1 ,800.00  ,50,50,50
BEGIN DESCRIPTION:
16
END DESCRIPTION:
#Sta/Elev= 12
   -13.2   35.97    -3.2   35.97      -2   36.67       0   36.67      .5   36.47
      .5   35.47     2.6   35.47     2.6   36.67     4.4   36.67     5.6   35.27
     6.2   34.57    16.2   34.57
#Mann= 3 , 0 , 0
   -13.2    .015       0       0    .015       0     2.6    .015       0
#XS Ineff= 2 , 0
               0   36.67     2.6           36.67
Permanent Ineff=
       F       F
Bank Sta=0,2.6
XS Rating Curve= 0
Exp/Cntr=.3,.1

Type RM Length L Ch R = 1 ,750.00  ,50,50,50
BEGIN DESCRIPTION:
15
END DESCRIPTION:
#Sta/Elev= 13
   -12.2   34.22    -2.2   34.22      -1   35.32     -.2   35.32     -.2   35.52
       0   35.52       0   34.32       2   34.32       2   35.52     2.2   35.52
     2.2   35.42     3.6   34.62    13.6   34.62
#Mann= 3 , 0 , 0
   -12.2    .015       0       0    .015       0       2    .015       0
#XS Ineff= 2 , 0
               0   35.52       2           35.52
Permanent Ineff=
       F       F
Bank Sta=0,2
XS Rating Curve= 0
Exp/Cntr=.3,.1

Type RM Length L Ch R = 1 ,700.00  ,9,9,9
BEGIN DESCRIPTION:
14
END DESCRIPTION:
#Sta/Elev= 13
   -12.2   33.08    -2.2   33.08      -1   34.18     -.2   34.18     -.2   34.38
       0   34.38       0   33.18       2   33.18       2   34.38     2.2   34.38
     2.2   34.28     3.6   33.48    13.6   33.48
#Mann= 3 , 0 , 0
   -12.2    .015       0       0    .015       0       2    .015       0
#XS Ineff= 2 , 0
               0   34.38       2           34.38
Permanent Ineff=
       F       F
Bank Sta=0,2
XS Rating Curve= 0
Exp/Cntr=.3,.1

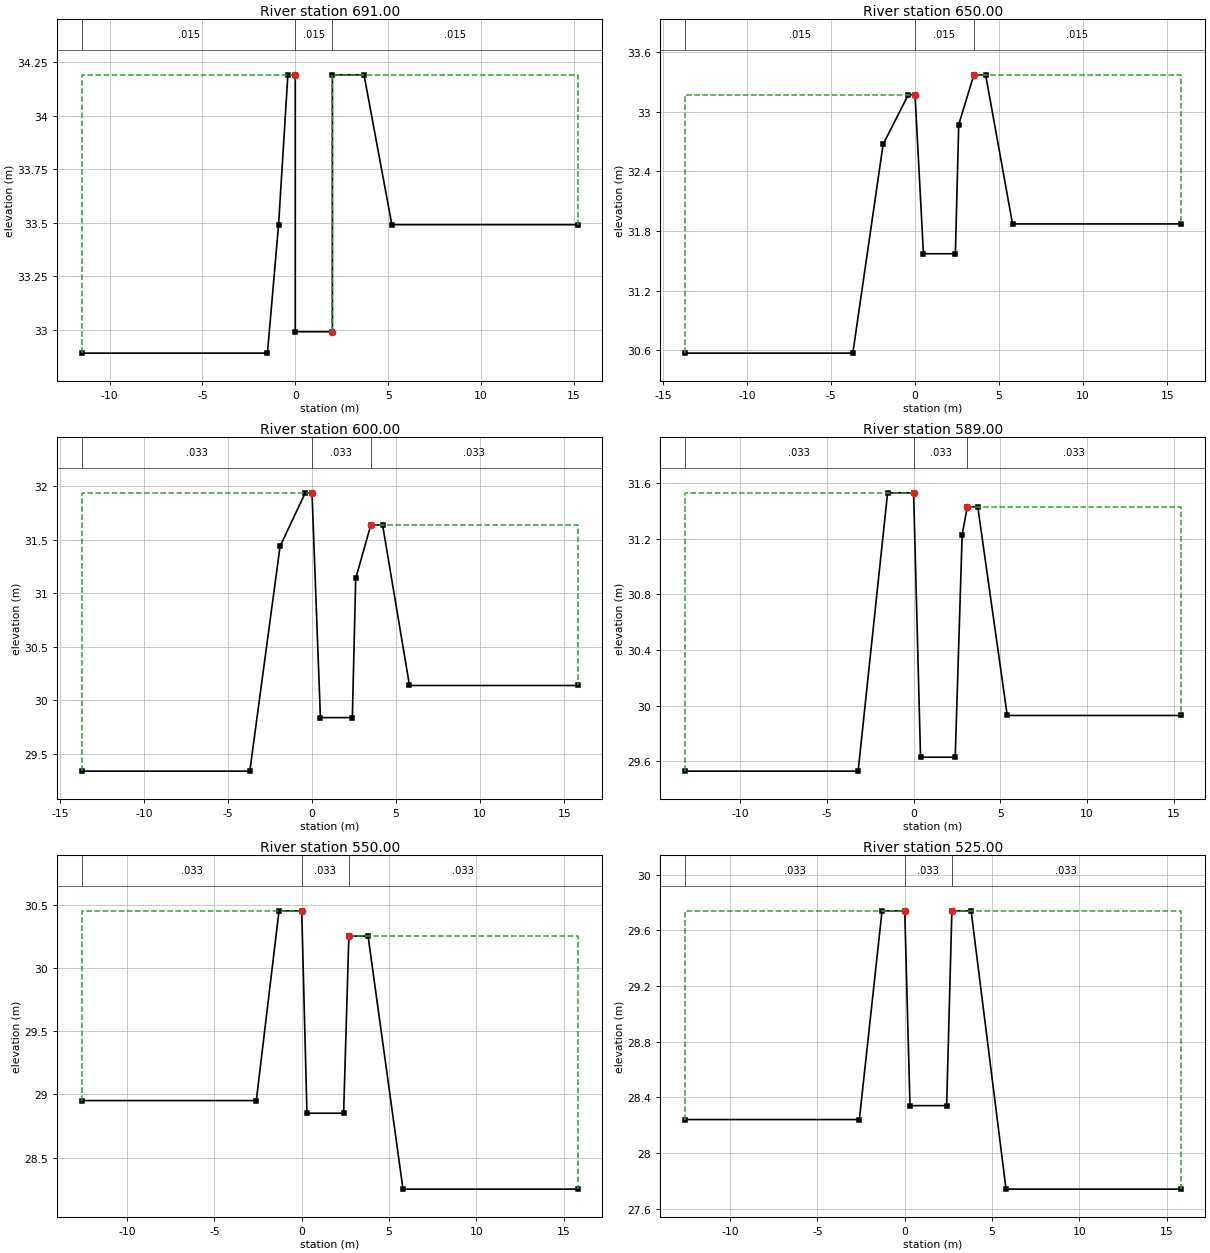
Type RM Length L Ch R = 1 ,691.00  ,41,41,41
BEGIN DESCRIPTION:
13.041
END DESCRIPTION:
#Sta/Elev= 11
   -11.5   32.89    -1.5   32.89     -.9   33.49     -.4   34.19       0   34.19
       0   32.99       2   32.99       2   34.19     3.7   34.19     5.2   33.49
    15.2   33.49
#Mann= 3 , 0 , 0
   -11.5    .015       0       0    .015       0       2    .015       0
#XS Ineff= 2 , 0
               0   34.19       2           34.19
Permanent Ineff=
       F       F
Bank Sta=0,2
XS Rating Curve= 0
Exp/Cntr=.3,.1

Type RM Length L Ch R = 1 ,650.00  ,50,50,50
BEGIN DESCRIPTION:
13
END DESCRIPTION:
#Sta/Elev= 12
   -13.7   30.57    -3.7   30.57    -1.9   32.67     -.4   33.17       0   33.17
      .5   31.57     2.4   31.57     2.6   32.87     3.5   33.37     4.2   33.37
     5.8   31.87    15.8   31.87
#Mann= 3 , 0 , 0
   -13.7    .015       0       0    .015       0     3.5    .015       0
#XS Ineff= 2 , 0
               0   33.17     3.5           33.37
Permanent Ineff=
       F       F
Bank Sta=0,3.5
XS Rating Curve= 0
Exp/Cntr=.3,.1

Type RM Length L Ch R = 1 ,600.00  ,11,11,11
BEGIN DESCRIPTION:
12
END DESCRIPTION:
#Sta/Elev= 12
   -13.7   29.34    -3.7   29.34    -1.9   31.44     -.4   31.94       0   31.94
      .5   29.84     2.4   29.84     2.6   31.14     3.5   31.64     4.2   31.64
     5.8   30.14    15.8   30.14
#Mann= 3 , 0 , 0
   -13.7    .033       0       0    .033       0     3.5    .033       0
#XS Ineff= 2 , 0
               0   31.94     3.5           31.64
Permanent Ineff=
       F       F
Bank Sta=0,3.5
XS Rating Curve= 0
Exp/Cntr=.3,.1

Type RM Length L Ch R = 1 ,589.00  ,39,39,39
BEGIN DESCRIPTION:
11.039
END DESCRIPTION:
#Sta/Elev= 11
   -13.2   29.53    -3.2   29.53    -1.5   31.53       0   31.53      .4   29.63
     2.4   29.63     2.8   31.23     3.1   31.43     3.7   31.43     5.4   29.93
    15.4   29.93
#Mann= 3 , 0 , 0
   -13.2    .033       0       0    .033       0     3.1    .033       0
#XS Ineff= 2 , 0
               0   31.53     3.1           31.43
Permanent Ineff=
       F       F
Bank Sta=0,3.1
XS Rating Curve= 0
Exp/Cntr=.3,.1

Type RM Length L Ch R = 1 ,550.00  ,25,25,25
BEGIN DESCRIPTION:
11
END DESCRIPTION:
#Sta/Elev= 10
   -12.6   28.95    -2.6   28.95    -1.3   30.45       0   30.45      .3   28.85
     2.4   28.85     2.7   30.25     3.8   30.25     5.8   28.25    15.8   28.25
#Mann= 3 , 0 , 0
   -12.6    .033       0       0    .033       0     2.7    .033       0
#XS Ineff= 2 , 0
               0   30.45     2.7           30.25
Permanent Ineff=
       F       F
Bank Sta=0,2.7
XS Rating Curve= 0
Exp/Cntr=.3,.1

Type RM Length L Ch R = 1 ,525.00  ,1,1,1
BEGIN DESCRIPTION:
10.025
END DESCRIPTION:
#Sta/Elev= 10
   -12.6   28.24    -2.6   28.24    -1.3   29.74       0   29.74      .3   28.34
     2.4   28.34     2.7   29.74     3.8   29.74     5.8   27.74    15.8   27.74
#Mann= 3 , 0 , 0
   -12.6    .033       0       0    .033       0     2.7    .033       0
#XS Ineff= 2 , 0
               0   29.74     2.7           29.74
Permanent Ineff=
       F       F
Bank Sta=0,2.7
XS Rating Curve= 0
Exp/Cntr=.3,.1

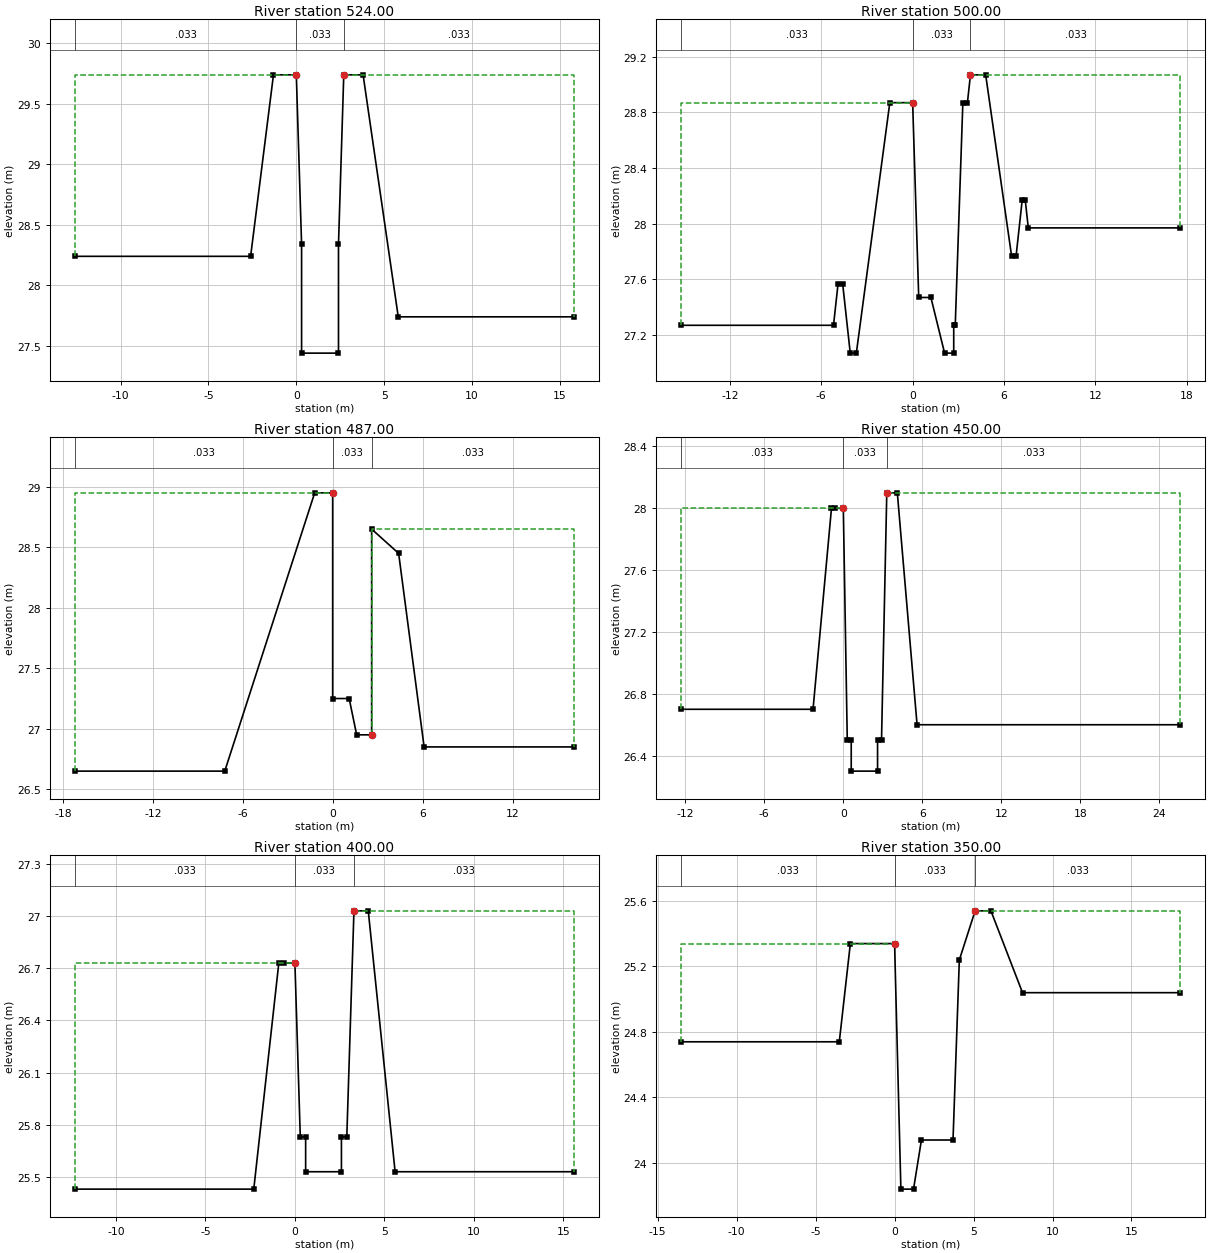
Type RM Length L Ch R = 1 ,524.00  ,24,24,24
BEGIN DESCRIPTION:
10.024
END DESCRIPTION:
#Sta/Elev= 12
   -12.6   28.24    -2.6   28.24    -1.3   29.74       0   29.74      .3   28.34
      .3   27.44     2.4   27.44     2.4   28.34     2.7   29.74     3.8   29.74
     5.8   27.74    15.8   27.74
#Mann= 3 , 0 , 0
   -12.6    .033       0       0    .033       0     2.7    .033       0
#XS Ineff= 2 , 0
               0   29.74     2.7           29.74
Permanent Ineff=
       F       F
Bank Sta=0,2.7
XS Rating Curve= 0
Exp/Cntr=.3,.1

Type RM Length L Ch R = 1 ,500.00  ,13,13,13
BEGIN DESCRIPTION:
10
END DESCRIPTION:
#Sta/Elev= 24
   -15.2   27.27    -5.2   27.27    -4.9   27.57    -4.6   27.57    -4.1   27.07
    -3.7   27.07    -1.5   28.87       0   28.87      .4   27.47     1.2   27.47
     2.1   27.07     2.7   27.07     2.7   27.27     2.8   27.27     3.3   28.87
     3.6   28.87     3.8   29.07     4.8   29.07     6.5   27.77     6.8   27.77
     7.2   28.17     7.4   28.17     7.6   27.97    17.6   27.97
#Mann= 3 , 0 , 0
   -15.2    .033       0       0    .033       0     3.8    .033       0
#XS Ineff= 2 , 0
               0   28.87     3.8           29.07
Permanent Ineff=
       F       F
Bank Sta=0,3.8
XS Rating Curve= 0
Exp/Cntr=.3,.1

Type RM Length L Ch R = 1 ,487.00  ,37,37,37
BEGIN DESCRIPTION:
9.037
END DESCRIPTION:
#Sta/Elev= 12
   -17.2   26.65    -7.2   26.65    -1.2   28.95       0   28.95       0   27.25
     1.1   27.25     1.6   26.95     2.6   26.95     2.6   28.65     4.4   28.45
     6.1   26.85    16.1   26.85
#Mann= 3 , 0 , 0
   -17.2    .033       0       0    .033       0     2.6    .033       0
#XS Ineff= 2 , 0
               0   28.95     2.6           28.65
Permanent Ineff=
       F       F
Bank Sta=0,2.6
XS Rating Curve= 0
Exp/Cntr=.3,.1

Type RM Length L Ch R = 1 ,450.00  ,50,50,50
BEGIN DESCRIPTION:
9
END DESCRIPTION:
#Sta/Elev= 15
   -12.3    26.7    -2.3    26.7     -.9      28     -.6      28       0      28
      .3    26.5      .6    26.5      .6    26.3     2.6    26.3     2.6    26.5
     2.9    26.5     3.3    28.1     4.1    28.1     5.6    26.6    25.6    26.6
#Mann= 3 , 0 , 0
   -12.3    .033       0       0    .033       0     3.3    .033       0
#XS Ineff= 2 , 0
               0      28     3.3            28.1
Permanent Ineff=
       F       F
Bank Sta=0,3.3
XS Rating Curve= 0
Exp/Cntr=.3,.1

Type RM Length L Ch R = 1 ,400.00  ,50,50,50
BEGIN DESCRIPTION:
8
END DESCRIPTION:
#Sta/Elev= 15
   -12.3   25.43    -2.3   25.43     -.9   26.73     -.6   26.73       0   26.73
      .3   25.73      .6   25.73      .6   25.53     2.6   25.53     2.6   25.73
     2.9   25.73     3.3   27.03     4.1   27.03     5.6   25.53    15.6   25.53
#Mann= 3 , 0 , 0
   -12.3    .033       0       0    .033       0     3.3    .033       0
#XS Ineff= 2 , 0
               0   26.73     3.3           27.03
Permanent Ineff=
       F       F
Bank Sta=0,3.3
XS Rating Curve= 0
Exp/Cntr=.3,.1

Type RM Length L Ch R = 1 ,350.00  ,34,34,34
BEGIN DESCRIPTION:
7
END DESCRIPTION:
#Sta/Elev= 13
   -13.5   24.74    -3.5   24.74    -2.8   25.34       0   25.34      .4   23.84
     1.2   23.84     1.7   24.14     3.7   24.14     4.1   25.24     5.1   25.54
     6.1   25.54     8.1   25.04    18.1   25.04
#Mann= 3 , 0 , 0
   -13.5    .033       0       0    .033       0     5.1    .033       0
#XS Ineff= 2 , 0
               0   25.34     5.1           25.54
Permanent Ineff=
       F       F
Bank Sta=0,5.1
XS Rating Curve= 0
Exp/Cntr=.3,.1

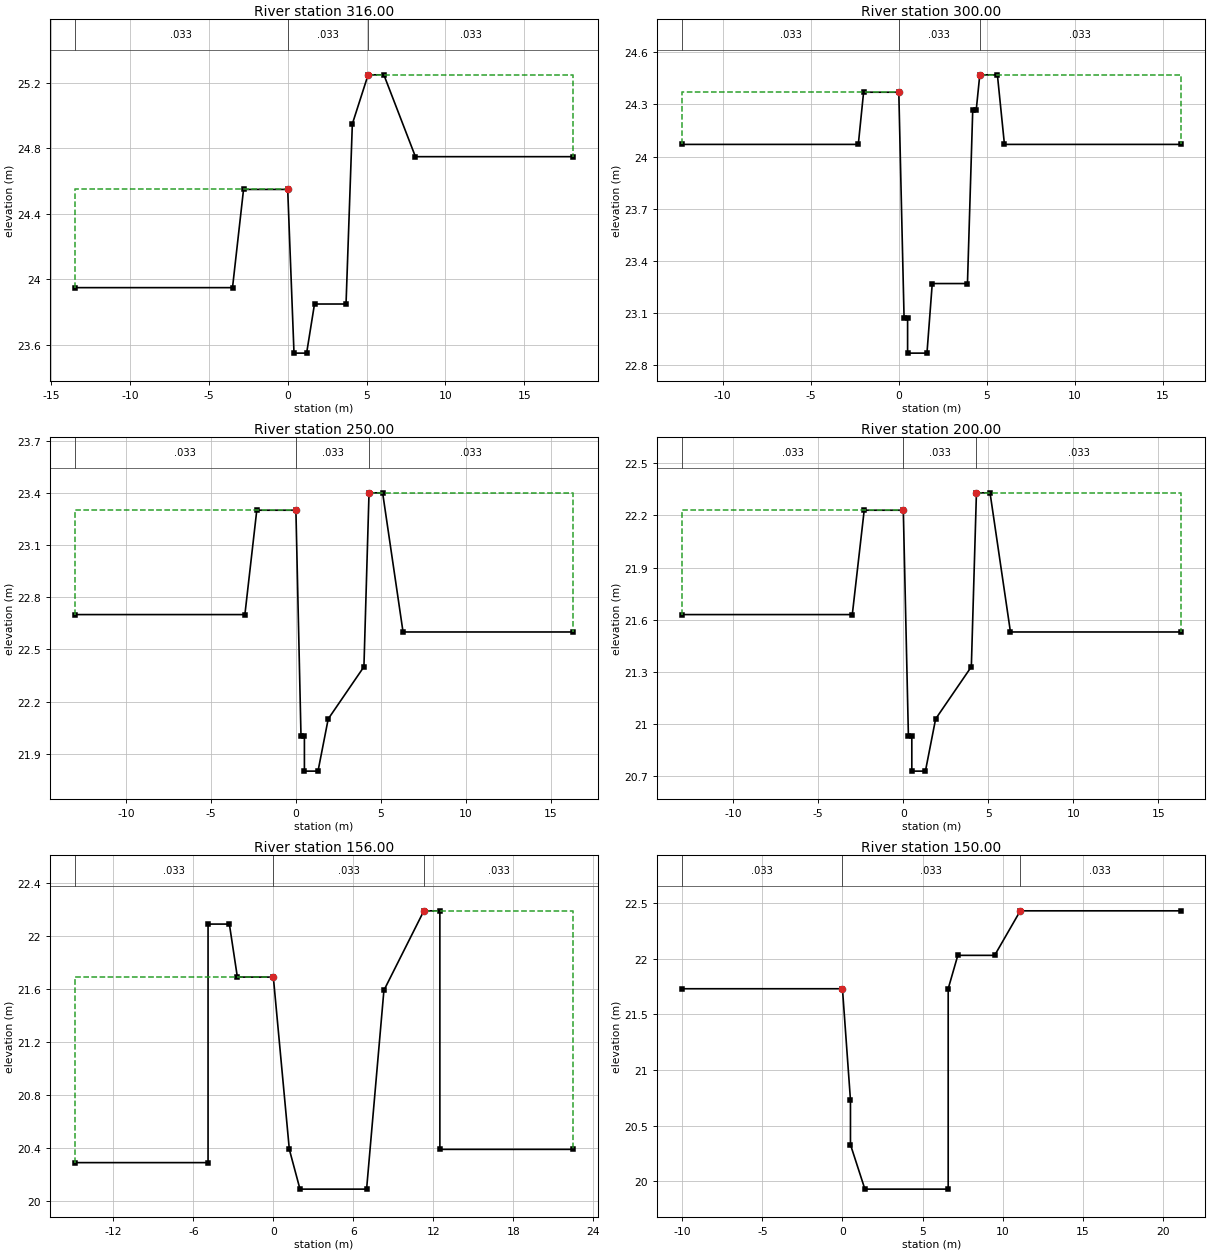
Type RM Length L Ch R = 1 ,316.00  ,16,16,16
BEGIN DESCRIPTION:
6.016
END DESCRIPTION:
#Sta/Elev= 13
   -13.5   23.95    -3.5   23.95    -2.8   24.55       0   24.55      .4   23.55
     1.2   23.55     1.7   23.85     3.7   23.85     4.1   24.95     5.1   25.25
     6.1   25.25     8.1   24.75    18.1   24.75
#Mann= 3 , 0 , 0
   -13.5    .033       0       0    .033       0     5.1    .033       0
#XS Ineff= 2 , 0
               0   24.55     5.1           25.25
Permanent Ineff=
       F       F
Bank Sta=0,5.1
XS Rating Curve= 0
Exp/Cntr=.3,.1

Type RM Length L Ch R = 1 ,300.00  ,50,50,50
BEGIN DESCRIPTION:
6
END DESCRIPTION:
#Sta/Elev= 16
   -12.3   24.07    -2.3   24.07      -2   24.37       0   24.37      .3   23.07
      .5   23.07      .5   22.87     1.6   22.87     1.9   23.27     3.9   23.27
     4.2   24.27     4.4   24.27     4.6   24.47     5.6   24.47       6   24.07
      16   24.07
#Mann= 3 , 0 , 0
   -12.3    .033       0       0    .033       0     4.6    .033       0
#XS Ineff= 2 , 0
               0   24.37     4.6           24.47
Permanent Ineff=
       F       F
Bank Sta=0,4.6
XS Rating Curve= 0
Exp/Cntr=.3,.1

Type RM Length L Ch R = 1 ,250.00  ,50,50,50
BEGIN DESCRIPTION:
5
END DESCRIPTION:
#Sta/Elev= 14
     -13    22.7      -3    22.7    -2.3    23.3       0    23.3      .3      22
      .5      22      .5    21.8     1.3    21.8     1.9    22.1       4    22.4
     4.3    23.4     5.1    23.4     6.3    22.6    16.3    22.6
#Mann= 3 , 0 , 0
     -13    .033       0       0    .033       0     4.3    .033       0
#XS Ineff= 2 , 0
               0    23.3     4.3            23.4
Permanent Ineff=
       F       F
Bank Sta=0,4.3
XS Rating Curve= 0
Exp/Cntr=.3,.1

Type RM Length L Ch R = 1 ,200.00  ,44,44,44
BEGIN DESCRIPTION:
4
END DESCRIPTION:
#Sta/Elev= 14
     -13   21.63      -3   21.63    -2.3   22.23       0   22.23      .3   20.93
      .5   20.93      .5   20.73     1.3   20.73     1.9   21.03       4   21.33
     4.3   22.33     5.1   22.33     6.3   21.53    16.3   21.53
#Mann= 3 , 0 , 0
     -13    .033       0       0    .033       0     4.3    .033       0
#XS Ineff= 2 , 0
               0   22.23     4.3           22.33
Permanent Ineff=
       F       F
Bank Sta=0,4.3
XS Rating Curve= 0
Exp/Cntr=.3,.1

Type RM Length L Ch R = 1 ,156.00  ,6,6,6
BEGIN DESCRIPTION:
3.006
END DESCRIPTION:
#Sta/Elev= 14
   -14.9   20.29    -4.9   20.29    -4.9   22.09    -3.3   22.09    -2.7   21.69
       0   21.69     1.2   20.39       2   20.09       7   20.09     8.3   21.59
    11.3   22.19    12.5   22.19    12.5   20.39    22.5   20.39
#Mann= 3 , 0 , 0
   -14.9    .033       0       0    .033       0    11.3    .033       0
#XS Ineff= 2 , 0
               0   21.69    11.3           22.19
Permanent Ineff=
       F       F
Bank Sta=0,11.3
XS Rating Curve= 0
Exp/Cntr=.3,.1

Type RM Length L Ch R = 1 ,150.00  ,24,24,24
BEGIN DESCRIPTION:
3
END DESCRIPTION:
#Sta/Elev= 11
     -10   21.73       0   21.73      .5   20.73      .5   20.33     1.4   19.93
     6.6   19.93     6.6   21.73     7.2   22.03     9.5   22.03    11.1   22.43
    21.1   22.43
#Mann= 3 , 0 , 0
     -10    .033       0       0    .033       0    11.1    .033       0
#XS Ineff= 2 , 0
               0   21.73    11.1           22.43
Permanent Ineff=
       F       F
Bank Sta=0,11.1
XS Rating Curve= 0
Exp/Cntr=.3,.1

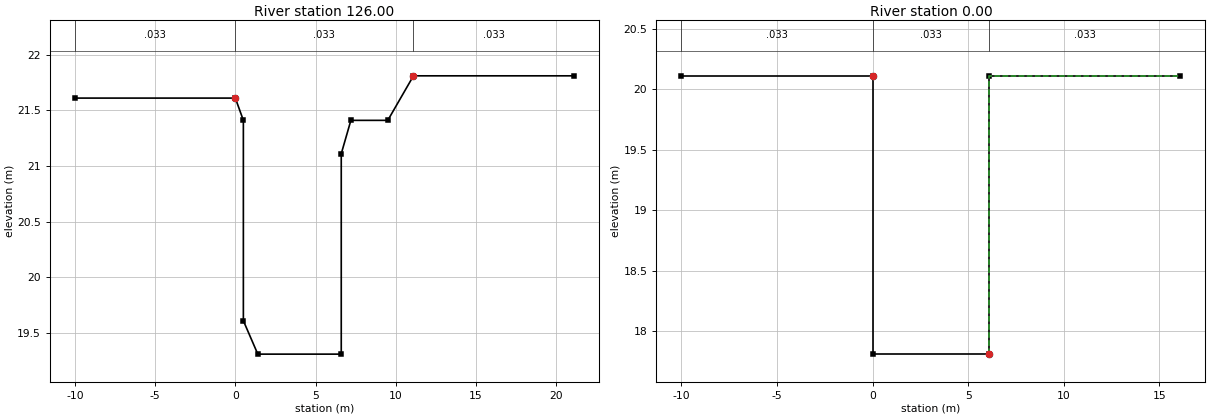
Type RM Length L Ch R = 1 ,126.00  ,126,126,126
BEGIN DESCRIPTION:
2.026
END DESCRIPTION:
#Sta/Elev= 11
     -10   21.61       0   21.61      .5   21.41      .5   19.61     1.4   19.31
     6.6   19.31     6.6   21.11     7.2   21.41     9.5   21.41    11.1   21.81
    21.1   21.81
#Mann= 3 , 0 , 0
     -10    .033       0       0    .033       0    11.1    .033       0
#XS Ineff= 2 , 0
               0   21.61    11.1           21.81
Permanent Ineff=
       F       F
Bank Sta=0,11.1
XS Rating Curve= 0
Exp/Cntr=.3,.1

Type RM Length L Ch R = 1 ,0.00    ,0,0,0
BEGIN DESCRIPTION:
0
END DESCRIPTION:
#Sta/Elev= 6
     -10   20.11       0   20.11       0   17.81     6.1   17.81     6.1   20.11
    16.1   20.11
#Mann= 3 , 0 , 0
     -10    .033       0       0    .033       0     6.1    .033       0
#XS Ineff= 2 , 0
               0   20.11     6.1           20.11
Permanent Ineff=
       F       F
Bank Sta=0,6.1
XS Rating Curve= 0
Exp/Cntr=.3,.1

Chan Stop Cuts=-1