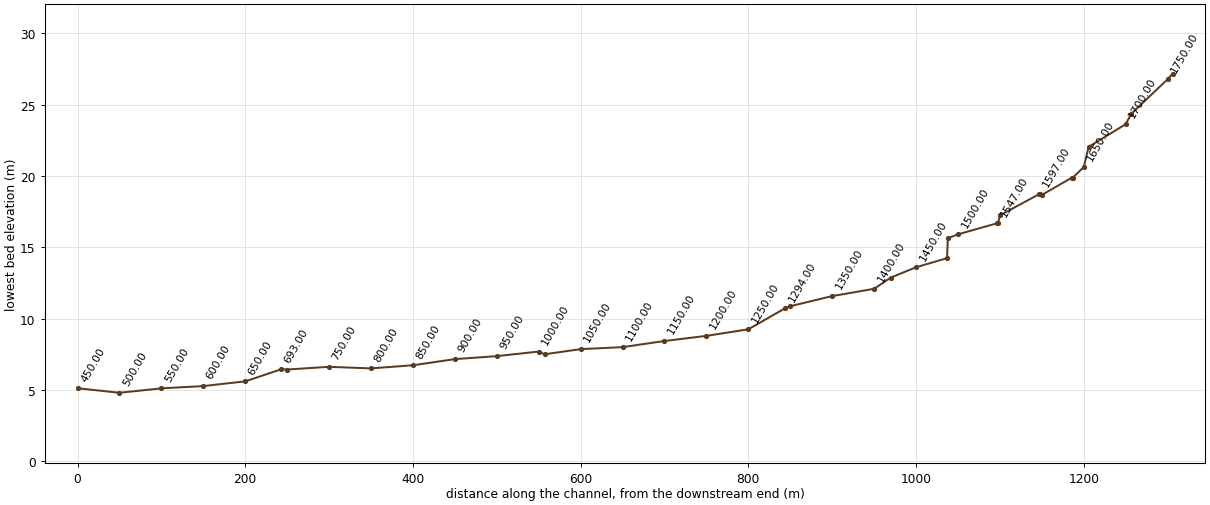
--- SKC.prj (project) ---

Proj Title=SKC
Current Plan=p01
Default Exp/Contr=.3,.1
SI Units
Geom File=g01
Flow File=f01
Plan File=p01
Y Axis Title=Elevation
X Axis Title(PF)=Main Channel Distance
X Axis Title(XS)=Station
BEGIN DESCRIPTION:
           BACK WATER COMPUTATION
      APPLICATION OF HEC-2 BY Samju Construction Engineering
      SAKOK-STREEM : 30 YR
END DESCRIPTION:
DSS File=dss
DSS Export Rating Curves= 0
DSS Export Rating Curve Sorted= 0
DSS Export Volume Flow Curves= 0
DXF OffsetX= 0
DXF OffsetY= 0
DXF ScaleX= 1
DXF ScaleY= 10

--- SKC.p01 (plan) ---

Plan Title=Imported Plan 01
Version=Version 3.0.1  Mar 2001
Short Identifier=Imported Pla
Geom File=g01
Flow File=f01
Subcritical Flow
K Sum by GR= 0
Std Step Tol= 0.003
Critical Tol= 0.003
Num of Std Step Trials= 20
Max Error Tol= 0.1
Flow Tol Ratio= 0.001
Split Flow NTrial= 30
Split Flow Tol= 0.02
Split Flow Ratio= 0.02
Log Output Level= 0
Friction Slope Method= 1
Unsteady Friction Slope Method= 2
Parabolic Critical Depth
Global Vel Dist= 0 , 0 , 0
Global Log Level= 0
CheckData=True
Encroach Param=-1 ,0,0, 0
Computation Interval=1HOUR
Output Interval=1HOUR
Run HTab= 0
Run UNet= 0
Run PostProcess= 0
UNET Theta= 1
UNET ZTol= 0.02
UNET ZSATol= 0.1
UNET MxIter= 20
UNET MaxInSteps= 20
UNET DtIC= 0
UNET DtMin= 0
UNET MaxCRTS= 20
UNET WFStab= 2
UNET SFStab= 1
UNET WFX= 1
UNET SFX= 1
UNET Convert EG Bridges=-1
UNET Use Existing IB Tables=-1
Instantaneous Interval=1HOUR
DSS File=dss
Write IC File= 0
Write Velocity= 0
Write Detailed= 0

--- SKC.f01 (steady flow) ---

Flow Title=Imported Flow 01
Version=Version 3.0.1  Mar 2001
Number of Profiles= 5
Profile Names=PF 1,PF 2,PF 3,PF 4,PF 5
River Rch & RM=RIVER-1,Reach-1         ,35.006
    3.12    3.43    3.62    3.85    4.06
River Rch & RM=RIVER-1,Reach-1         ,19
    6.12    6.74     7.1    7.56    7.98
River Rch & RM=SAKOK,SAKOK           ,1756.00
    3.12    3.43    3.62    3.85    4.06
River Rch & RM=SAKOK,SAKOK           ,950.00
    6.12    6.74     7.1    7.56    7.98
Boundary for River Rch & Prof#=SAKOK,SAKOK           , 1
Up Type= 0
Dn Type= 3
Dn Slope=.016
Boundary for River Rch & Prof#=SAKOK,SAKOK           , 2
Up Type= 0
Dn Type= 3
Dn Slope=.016
Boundary for River Rch & Prof#=SAKOK,SAKOK           , 3
Up Type= 0
Dn Type= 3
Dn Slope=.016
Boundary for River Rch & Prof#=SAKOK,SAKOK           , 4
Up Type= 0
Dn Type= 3
Dn Slope=.016
Boundary for River Rch & Prof#=SAKOK,SAKOK           , 5
Up Type= 0
Dn Type= 3
Dn Slope=.016
DSS Import GetInterval= 0
DSS Import GetPeak= 0
DSS Import FillOption= 0

--- SKC.g01 (geometry) ---

Geom Title=Imported Geom 01
Version=Version 3.0.1  Mar 2001

River Reach=SAKOK           ,SAKOK
Reach XY= 2
              .5             .95              .5             .05

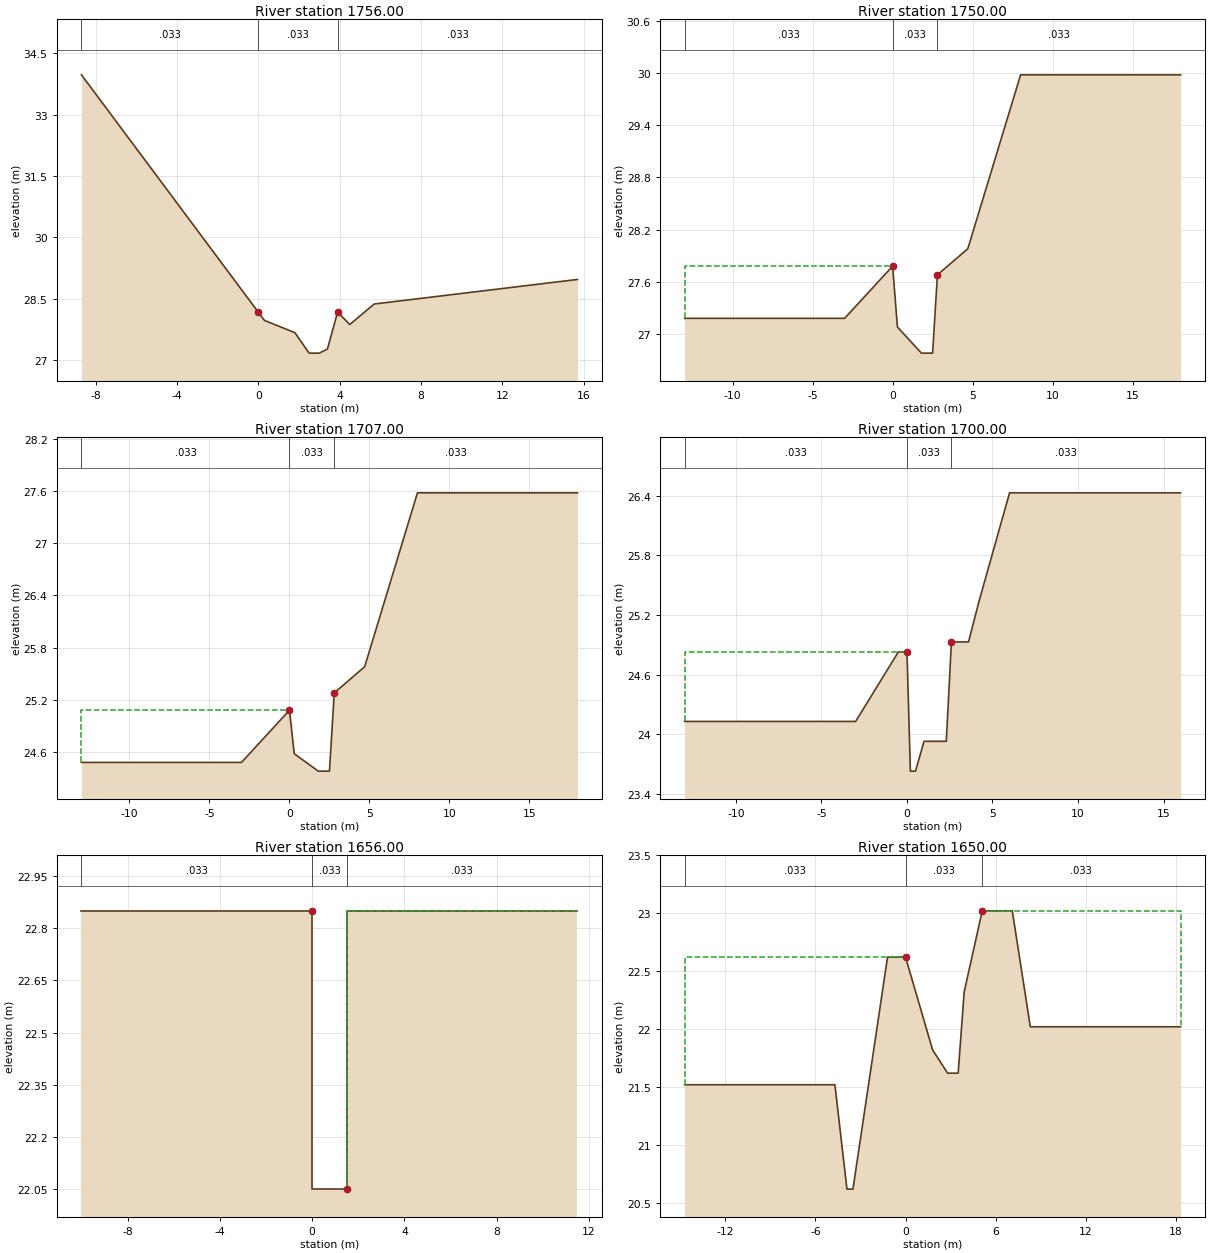
Type RM Length L Ch R = 1 ,1756.00 ,6,6,6
BEGIN DESCRIPTION:
35.006
END DESCRIPTION:
#Sta/Elev= 14
    -8.7   33.97    -5.7   31.97    -2.7   29.97       0   28.17      .3   27.97
     1.8   27.67     2.5   27.17       3   27.17     3.4   27.27     3.9   28.17
     4.5   27.87     5.7   28.37    10.7   28.67    15.7   28.97
#Mann= 3 , 0 , 0
    -8.7    .033       0       0    .033       0     3.9    .033       0
#XS Ineff= 2 , 0
               0   28.17     3.9           28.17
Permanent Ineff=
       F       F
Bank Sta=0,3.9
XS Rating Curve= 0
Exp/Cntr=.3,.1

Type RM Length L Ch R = 1 ,1750.00 ,43,43,43
BEGIN DESCRIPTION:
35
END DESCRIPTION:
#Sta/Elev= 10
     -13   27.18      -3   27.18       0   27.78      .3   27.08     1.8   26.78
     2.5   26.78     2.8   27.68     4.7   27.98       8   29.98      18   29.98
#Mann= 3 , 0 , 0
     -13    .033       0       0    .033       0     2.8    .033       0
#XS Ineff= 2 , 0
               0   27.78     2.8           27.68
Permanent Ineff=
       F       F
Bank Sta=0,2.8
XS Rating Curve= 0
Exp/Cntr=.3,.1

Type RM Length L Ch R = 1 ,1707.00 ,7,7,7
BEGIN DESCRIPTION:
34.007
END DESCRIPTION:
#Sta/Elev= 10
     -13   24.48      -3   24.48       0   25.08      .3   24.58     1.8   24.38
     2.5   24.38     2.8   25.28     4.7   25.58       8   27.58      18   27.58
#Mann= 3 , 0 , 0
     -13    .033       0       0    .033       0     2.8    .033       0
#XS Ineff= 2 , 0
               0   25.08     2.8           25.28
Permanent Ineff=
       F       F
Bank Sta=0,2.8
XS Rating Curve= 0
Exp/Cntr=.3,.1

Type RM Length L Ch R = 1 ,1700.00 ,44,44,44
BEGIN DESCRIPTION:
34
END DESCRIPTION:
#Sta/Elev= 13
     -13   24.13      -3   24.13     -.5   24.83       0   24.83      .2   23.63
      .5   23.63       1   23.93     2.3   23.93     2.6   24.93     3.6   24.93
     4.2   25.33       6   26.43      16   26.43
#Mann= 3 , 0 , 0
     -13    .033       0       0    .033       0     2.6    .033       0
#XS Ineff= 2 , 0
               0   24.83     2.6           24.93
Permanent Ineff=
       F       F
Bank Sta=0,2.6
XS Rating Curve= 0
Exp/Cntr=.3,.1

Type RM Length L Ch R = 1 ,1656.00 ,6,6,6
BEGIN DESCRIPTION:
33.006
END DESCRIPTION:
#Sta/Elev= 6
     -10   22.85       0   22.85       0   22.05     1.5   22.05     1.5   22.85
    11.5   22.85
#Mann= 3 , 0 , 0
     -10    .033       0       0    .033       0     1.5    .033       0
#XS Ineff= 2 , 0
               0   22.85     1.5           22.85
Permanent Ineff=
       F       F
Bank Sta=0,1.5
XS Rating Curve= 0
Exp/Cntr=.3,.1

Type RM Length L Ch R = 1 ,1650.00 ,13,13,13
BEGIN DESCRIPTION:
33
END DESCRIPTION:
#Sta/Elev= 14
   -14.7   21.52    -4.7   21.52    -3.9   20.62    -3.5   20.62    -1.2   22.62
       0   22.62     1.8   21.82     2.8   21.62     3.5   21.62     3.9   22.32
     5.1   23.02     7.1   23.02     8.3   22.02    18.3   22.02
#Mann= 3 , 0 , 0
   -14.7    .033       0       0    .033       0     5.1    .033       0
#XS Ineff= 2 , 0
               0   22.62     5.1           23.02
Permanent Ineff=
       F       F
Bank Sta=0,5.1
XS Rating Curve= 0
Exp/Cntr=.3,.1

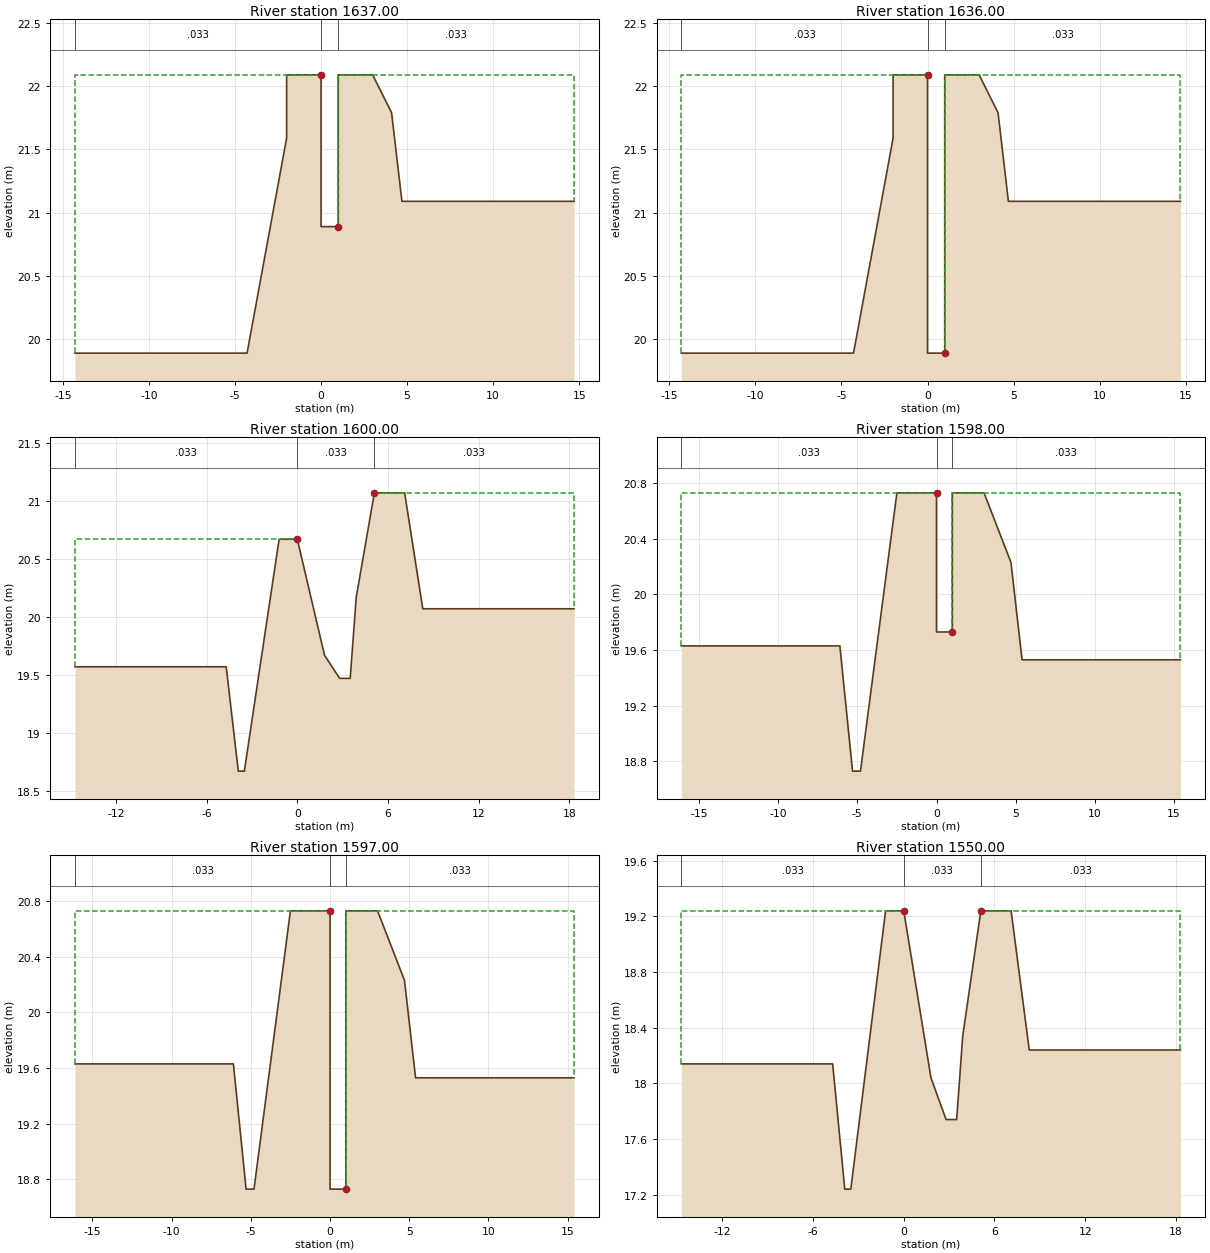
Type RM Length L Ch R = 1 ,1637.00 ,1,1,1
BEGIN DESCRIPTION:
32.037
END DESCRIPTION:
#Sta/Elev= 12
   -14.3   19.89    -4.3   19.89      -2   21.59      -2   22.09       0   22.09
       0   20.89       1   20.89       1   22.09       3   22.09     4.1   21.79
     4.7   21.09    14.7   21.09
#Mann= 3 , 0 , 0
   -14.3    .033       0       0    .033       0       1    .033       0
#XS Ineff= 2 , 0
               0   22.09       1           22.09
Permanent Ineff=
       F       F
Bank Sta=0,1
XS Rating Curve= 0
Exp/Cntr=.3,.1

Type RM Length L Ch R = 1 ,1636.00 ,36,36,36
BEGIN DESCRIPTION:
32.036
END DESCRIPTION:
#Sta/Elev= 14
   -14.3   19.89    -4.3   19.89      -2   21.59      -2   22.09       0   22.09
       0   20.89       0   19.89       1   19.89       1   20.89       1   22.09
       3   22.09     4.1   21.79     4.7   21.09    14.7   21.09
#Mann= 3 , 0 , 0
   -14.3    .033       0       0    .033       0       1    .033       0
#XS Ineff= 2 , 0
               0   22.09       1           22.09
Permanent Ineff=
       F       F
Bank Sta=0,1
XS Rating Curve= 0
Exp/Cntr=.3,.1

Type RM Length L Ch R = 1 ,1600.00 ,2,2,2
BEGIN DESCRIPTION:
32
END DESCRIPTION:
#Sta/Elev= 14
   -14.7   19.57    -4.7   19.57    -3.9   18.67    -3.5   18.67    -1.2   20.67
       0   20.67     1.8   19.67     2.8   19.47     3.5   19.47     3.9   20.17
     5.1   21.07     7.1   21.07     8.3   20.07    18.3   20.07
#Mann= 3 , 0 , 0
   -14.7    .033       0       0    .033       0     5.1    .033       0
#XS Ineff= 2 , 0
               0   20.67     5.1           21.07
Permanent Ineff=
       F       F
Bank Sta=0,5.1
XS Rating Curve= 0
Exp/Cntr=.3,.1

Type RM Length L Ch R = 1 ,1598.00 ,1,1,1
BEGIN DESCRIPTION:
31.048
END DESCRIPTION:
#Sta/Elev= 13
   -16.1   19.63    -6.1   19.63    -5.3   18.73    -4.8   18.73    -2.5   20.73
       0   20.73       0   19.73       1   19.73       1   20.73       3   20.73
     4.7   20.23     5.4   19.53    15.4   19.53
#Mann= 3 , 0 , 0
   -16.1    .033       0       0    .033       0       1    .033       0
#XS Ineff= 2 , 0
               0   20.73       1           20.73
Permanent Ineff=
       F       F
Bank Sta=0,1
XS Rating Curve= 0
Exp/Cntr=.3,.1

Type RM Length L Ch R = 1 ,1597.00 ,47,47,47
BEGIN DESCRIPTION:
31.047
END DESCRIPTION:
#Sta/Elev= 15
   -16.1   19.63    -6.1   19.63    -5.3   18.73    -4.8   18.73    -2.5   20.73
       0   20.73       0   19.73       0   18.73       1   18.73       1   19.73
       1   20.73       3   20.73     4.7   20.23     5.4   19.53    15.4   19.53
#Mann= 3 , 0 , 0
   -16.1    .033       0       0    .033       0       1    .033       0
#XS Ineff= 2 , 0
               0   20.73       1           20.73
Permanent Ineff=
       F       F
Bank Sta=0,1
XS Rating Curve= 0
Exp/Cntr=.3,.1

Type RM Length L Ch R = 1 ,1550.00 ,2,2,2
BEGIN DESCRIPTION:
31
END DESCRIPTION:
#Sta/Elev= 14
   -14.7   18.14    -4.7   18.14    -3.9   17.24    -3.5   17.24    -1.2   19.24
       0   19.24     1.8   18.04     2.8   17.74     3.5   17.74     3.9   18.34
     5.1   19.24     7.1   19.24     8.3   18.24    18.3   18.24
#Mann= 3 , 0 , 0
   -14.7    .033       0       0    .033       0     5.1    .033       0
#XS Ineff= 2 , 0
               0   19.24     5.1           19.24
Permanent Ineff=
       F       F
Bank Sta=0,5.1
XS Rating Curve= 0
Exp/Cntr=.3,.1

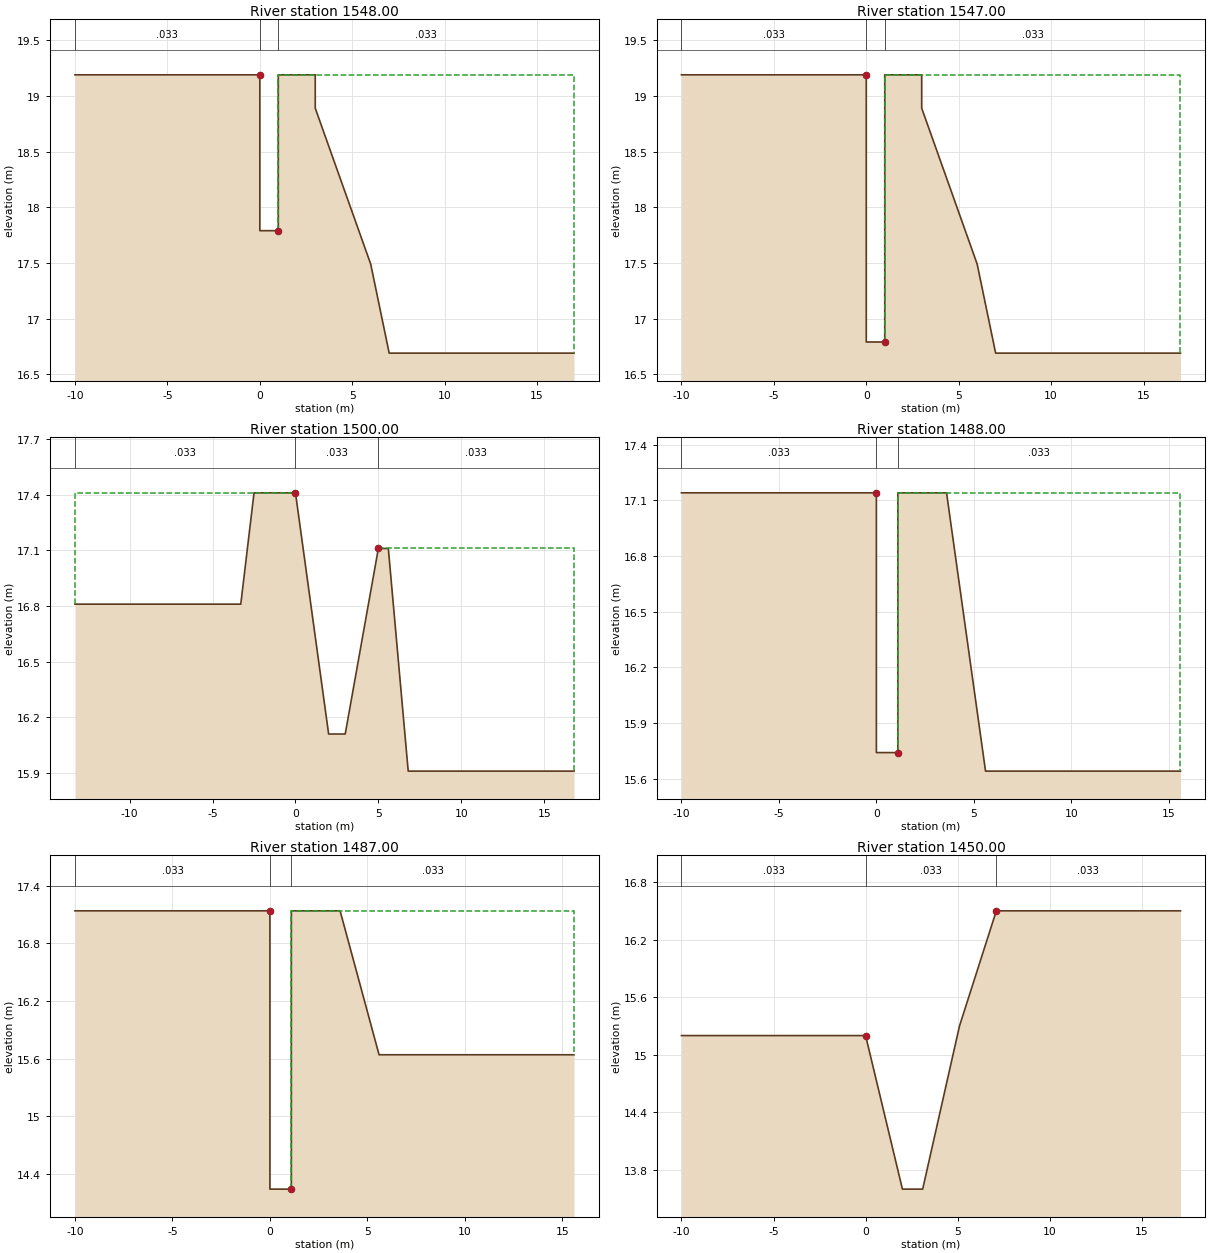
Type RM Length L Ch R = 1 ,1548.00 ,1,1,1
BEGIN DESCRIPTION:
30.048
END DESCRIPTION:
#Sta/Elev= 10
     -10   19.19       0   19.19       0   17.79       1   17.79       1   19.19
       3   19.19       3   18.89       6   17.49       7   16.69      17   16.69
#Mann= 3 , 0 , 0
     -10    .033       0       0    .033       0       1    .033       0
#XS Ineff= 2 , 0
               0   19.19       1           19.19
Permanent Ineff=
       F       F
Bank Sta=0,1
XS Rating Curve= 0
Exp/Cntr=.3,.1

Type RM Length L Ch R = 1 ,1547.00 ,47,47,47
BEGIN DESCRIPTION:
30.047
END DESCRIPTION:
#Sta/Elev= 12
     -10   19.19       0   19.19       0   17.79       0   16.79       1   16.79
       1   17.79       1   19.19       3   19.19       3   18.89       6   17.49
       7   16.69      17   16.69
#Mann= 3 , 0 , 0
     -10    .033       0       0    .033       0       1    .033       0
#XS Ineff= 2 , 0
               0   19.19       1           19.19
Permanent Ineff=
       F       F
Bank Sta=0,1
XS Rating Curve= 0
Exp/Cntr=.3,.1

Type RM Length L Ch R = 1 ,1500.00 ,12,12,12
BEGIN DESCRIPTION:
30
END DESCRIPTION:
#Sta/Elev= 10
   -13.3   16.81    -3.3   16.81    -2.5   17.41       0   17.41       2   16.11
       3   16.11       5   17.11     5.6   17.11     6.8   15.91    16.8   15.91
#Mann= 3 , 0 , 0
   -13.3    .033       0       0    .033       0       5    .033       0
#XS Ineff= 2 , 0
               0   17.41       5           17.11
Permanent Ineff=
       F       F
Bank Sta=0,5
XS Rating Curve= 0
Exp/Cntr=.3,.1

Type RM Length L Ch R = 1 ,1488.00 ,1,1,1
BEGIN DESCRIPTION:
29.038
END DESCRIPTION:
#Sta/Elev= 8
     -10   17.14       0   17.14       0   15.74     1.1   15.74     1.1   17.14
     3.6   17.14     5.6   15.64    15.6   15.64
#Mann= 3 , 0 , 0
     -10    .033       0       0    .033       0     1.1    .033       0
#XS Ineff= 2 , 0
               0   17.14     1.1           17.14
Permanent Ineff=
       F       F
Bank Sta=0,1.1
XS Rating Curve= 0
Exp/Cntr=.3,.1

Type RM Length L Ch R = 1 ,1487.00 ,37,37,37
BEGIN DESCRIPTION:
29.037
END DESCRIPTION:
#Sta/Elev= 10
     -10   17.14       0   17.14       0   15.74       0   14.24     1.1   14.24
     1.1   15.74     1.1   17.14     3.6   17.14     5.6   15.64    15.6   15.64
#Mann= 3 , 0 , 0
     -10    .033       0       0    .033       0     1.1    .033       0
#XS Ineff= 2 , 0
               0   17.14     1.1           17.14
Permanent Ineff=
       F       F
Bank Sta=0,1.1
XS Rating Curve= 0
Exp/Cntr=.3,.1

Type RM Length L Ch R = 1 ,1450.00 ,30,30,30
BEGIN DESCRIPTION:
29
END DESCRIPTION:
#Sta/Elev= 7
     -10    15.2       0    15.2       2    13.6     3.1    13.6     5.1    15.3
     7.1    16.5    17.1    16.5
#Mann= 3 , 0 , 0
     -10    .033       0       0    .033       0     7.1    .033       0
#XS Ineff= 2 , 0
               0    15.2     7.1            16.5
Permanent Ineff=
       F       F
Bank Sta=0,7.1
XS Rating Curve= 0
Exp/Cntr=.3,.1

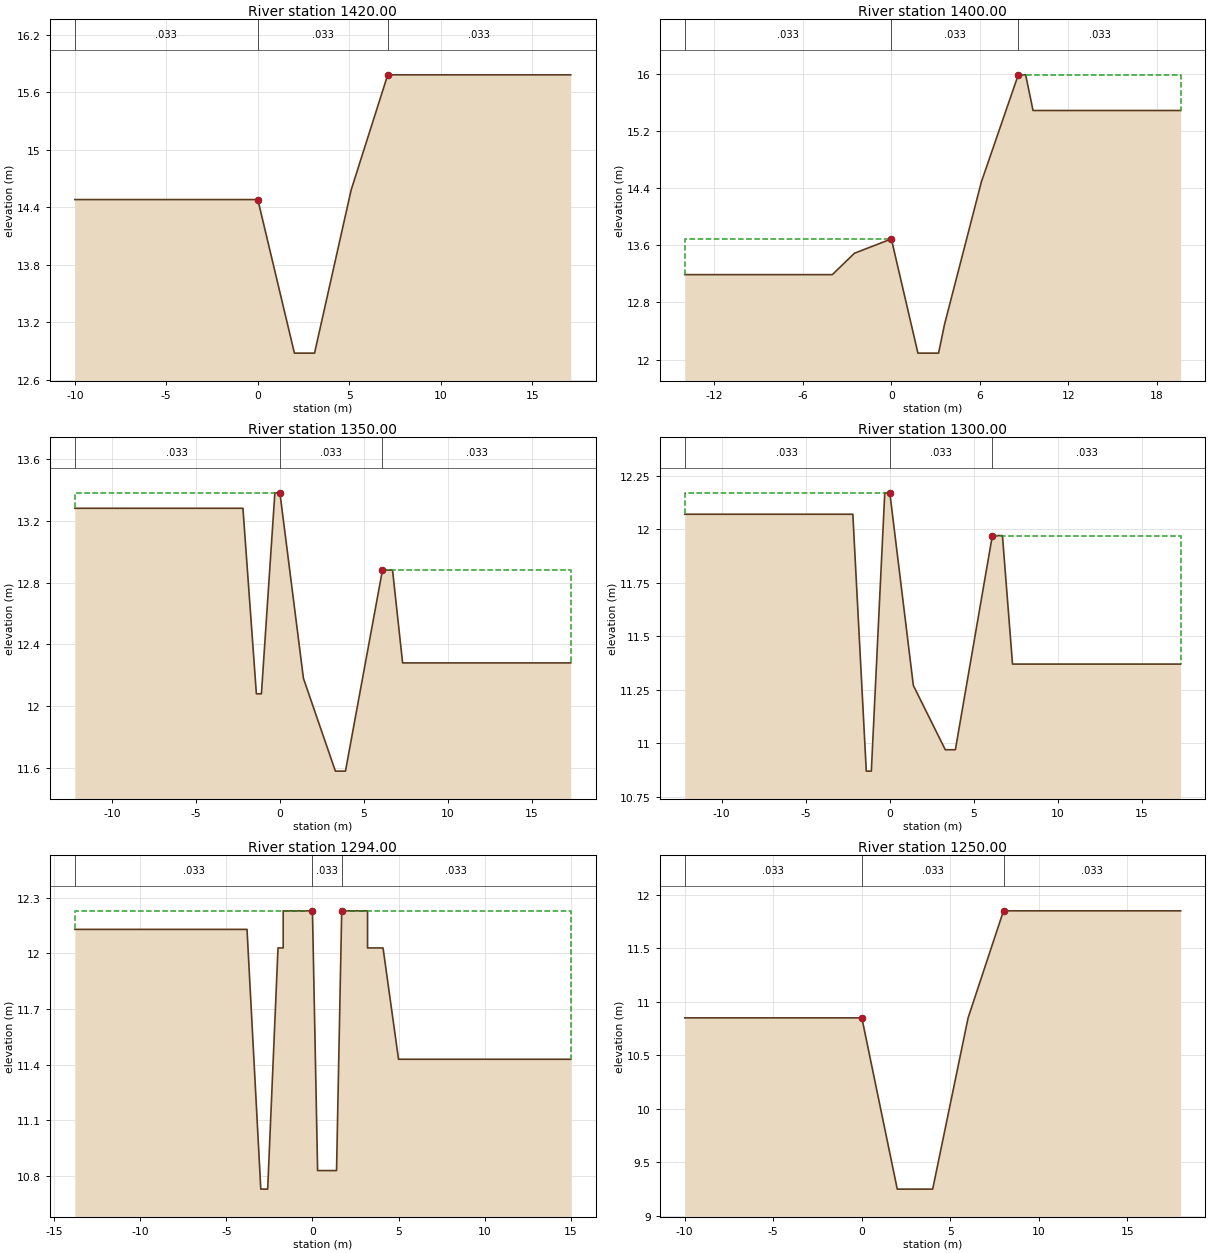
Type RM Length L Ch R = 1 ,1420.00 ,20,20,20
BEGIN DESCRIPTION:
28.02
END DESCRIPTION:
#Sta/Elev= 7
     -10   14.48       0   14.48       2   12.88     3.1   12.88     5.1   14.58
     7.1   15.78    17.1   15.78
#Mann= 3 , 0 , 0
     -10    .033       0       0    .033       0     7.1    .033       0
#XS Ineff= 2 , 0
               0   14.48     7.1           15.78
Permanent Ineff=
       F       F
Bank Sta=0,7.1
XS Rating Curve= 0
Exp/Cntr=.3,.1

Type RM Length L Ch R = 1 ,1400.00 ,50,50,50
BEGIN DESCRIPTION:
28
END DESCRIPTION:
#Sta/Elev= 12
     -14   13.19      -4   13.19    -2.5   13.49       0   13.69     1.8   12.09
     3.2   12.09     3.6   12.49     6.1   14.49     8.6   15.99     9.1   15.99
     9.6   15.49    19.6   15.49
#Mann= 3 , 0 , 0
     -14    .033       0       0    .033       0     8.6    .033       0
#XS Ineff= 2 , 0
               0   13.69     8.6           15.99
Permanent Ineff=
       F       F
Bank Sta=0,8.6
XS Rating Curve= 0
Exp/Cntr=.3,.1

Type RM Length L Ch R = 1 ,1350.00 ,50,50,50
BEGIN DESCRIPTION:
27
END DESCRIPTION:
#Sta/Elev= 13
   -12.2   13.28    -2.2   13.28    -1.4   12.08    -1.1   12.08     -.3   13.38
       0   13.38     1.4   12.18     3.3   11.58     3.9   11.58     6.1   12.88
     6.7   12.88     7.3   12.28    17.3   12.28
#Mann= 3 , 0 , 0
   -12.2    .033       0       0    .033       0     6.1    .033       0
#XS Ineff= 2 , 0
               0   13.38     6.1           12.88
Permanent Ineff=
       F       F
Bank Sta=0,6.1
XS Rating Curve= 0
Exp/Cntr=.3,.1

Type RM Length L Ch R = 1 ,1300.00 ,6,6,6
BEGIN DESCRIPTION:
26
END DESCRIPTION:
#Sta/Elev= 13
   -12.2   12.07    -2.2   12.07    -1.4   10.87    -1.1   10.87     -.3   12.17
       0   12.17     1.4   11.27     3.3   10.97     3.9   10.97     6.1   11.97
     6.7   11.97     7.3   11.37    17.3   11.37
#Mann= 3 , 0 , 0
   -12.2    .033       0       0    .033       0     6.1    .033       0
#XS Ineff= 2 , 0
               0   12.17     6.1           11.97
Permanent Ineff=
       F       F
Bank Sta=0,6.1
XS Rating Curve= 0
Exp/Cntr=.3,.1

Type RM Length L Ch R = 1 ,1294.00 ,44,44,44
BEGIN DESCRIPTION:
25.044
END DESCRIPTION:
#Sta/Elev= 16
   -13.8   12.13    -3.8   12.13      -3   10.73    -2.6   10.73      -2   12.03
    -1.7   12.03    -1.7   12.23       0   12.23      .3   10.83     1.4   10.83
     1.7   12.23     3.2   12.23     3.2   12.03     4.1   12.03       5   11.43
      15   11.43
#Mann= 3 , 0 , 0
   -13.8    .033       0       0    .033       0     1.7    .033       0
#XS Ineff= 2 , 0
               0   12.23     1.7           12.23
Permanent Ineff=
       F       F
Bank Sta=0,1.7
XS Rating Curve= 0
Exp/Cntr=.3,.1

Type RM Length L Ch R = 1 ,1250.00 ,50,50,50
BEGIN DESCRIPTION:
25
END DESCRIPTION:
#Sta/Elev= 7
     -10   10.85       0   10.85       2    9.25       4    9.25       6   10.85
       8   11.85      18   11.85
#Mann= 3 , 0 , 0
     -10    .033       0       0    .033       0       8    .033       0
#XS Ineff= 2 , 0
               0   10.85       8           11.85
Permanent Ineff=
       F       F
Bank Sta=0,8
XS Rating Curve= 0
Exp/Cntr=.3,.1

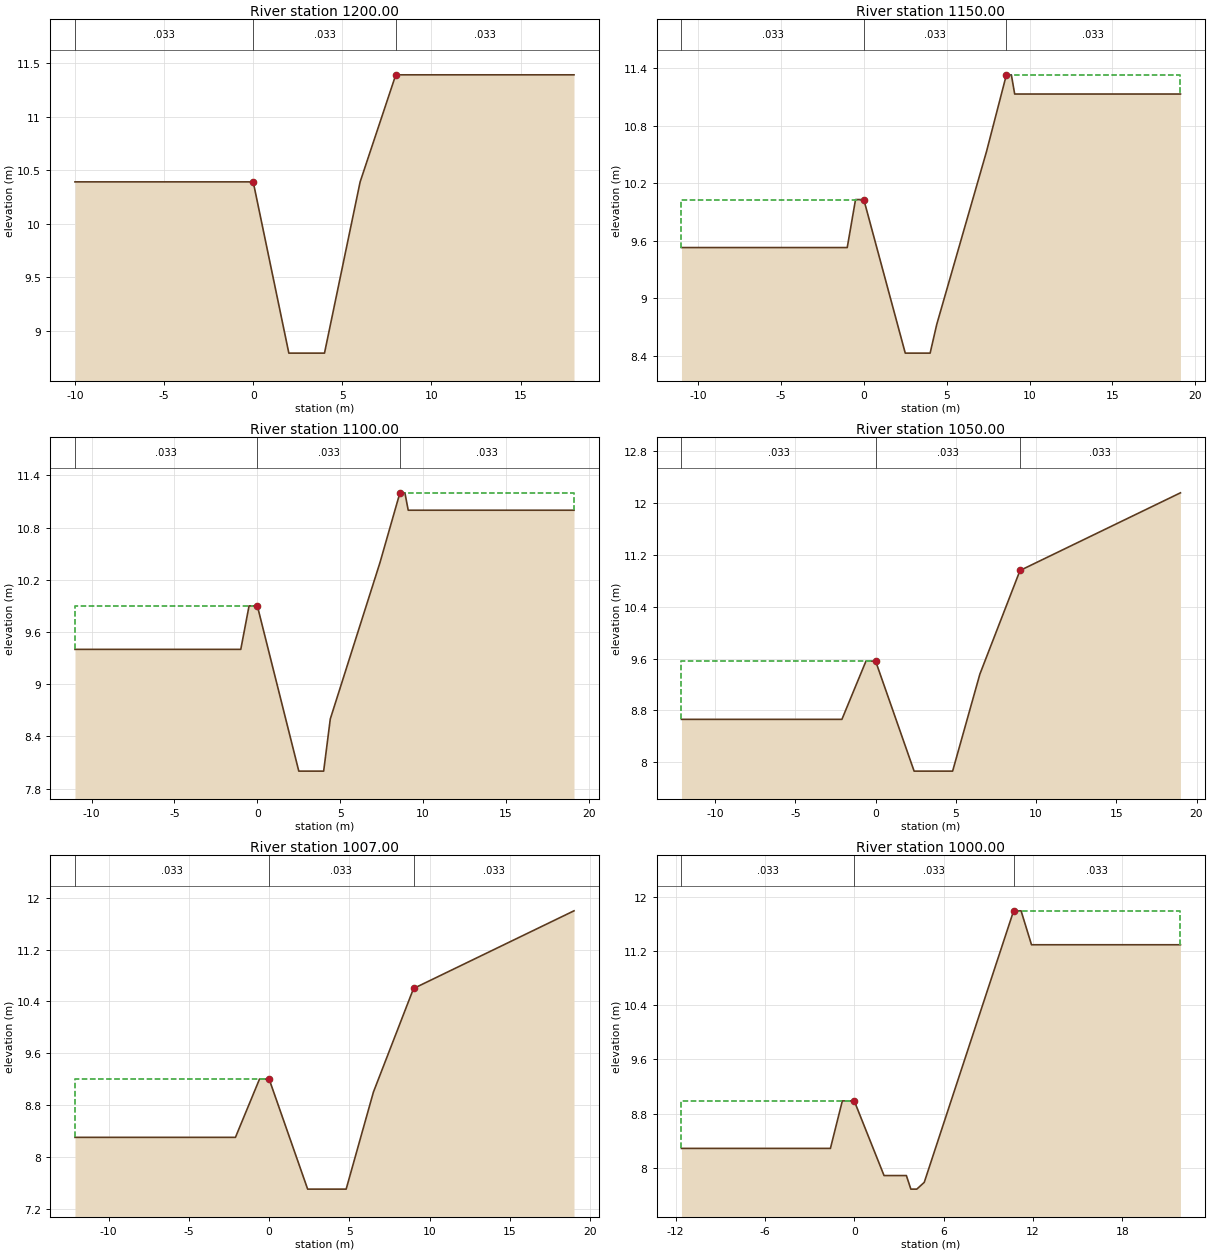
Type RM Length L Ch R = 1 ,1200.00 ,50,50,50
BEGIN DESCRIPTION:
24
END DESCRIPTION:
#Sta/Elev= 7
     -10   10.39       0   10.39       2    8.79       4    8.79       6   10.39
       8   11.39      18   11.39
#Mann= 3 , 0 , 0
     -10    .033       0       0    .033       0       8    .033       0
#XS Ineff= 2 , 0
               0   10.39       8           11.39
Permanent Ineff=
       F       F
Bank Sta=0,8
XS Rating Curve= 0
Exp/Cntr=.3,.1

Type RM Length L Ch R = 1 ,1150.00 ,50,50,50
BEGIN DESCRIPTION:
23
END DESCRIPTION:
#Sta/Elev= 12
     -11    9.53      -1    9.53     -.5   10.03       0   10.03     2.5    8.43
       4    8.43     4.4    8.73     7.4   10.53     8.6   11.33     8.9   11.33
     9.1   11.13    19.1   11.13
#Mann= 3 , 0 , 0
     -11    .033       0       0    .033       0     8.6    .033       0
#XS Ineff= 2 , 0
               0   10.03     8.6           11.33
Permanent Ineff=
       F       F
Bank Sta=0,8.6
XS Rating Curve= 0
Exp/Cntr=.3,.1

Type RM Length L Ch R = 1 ,1100.00 ,50,50,50
BEGIN DESCRIPTION:
22
END DESCRIPTION:
#Sta/Elev= 12
     -11     9.4      -1     9.4     -.5     9.9       0     9.9     2.5       8
       4       8     4.4     8.6     7.4    10.4     8.6    11.2     8.9    11.2
     9.1      11    19.1      11
#Mann= 3 , 0 , 0
     -11    .033       0       0    .033       0     8.6    .033       0
#XS Ineff= 2 , 0
               0     9.9     8.6            11.2
Permanent Ineff=
       F       F
Bank Sta=0,8.6
XS Rating Curve= 0
Exp/Cntr=.3,.1

Type RM Length L Ch R = 1 ,1050.00 ,43,43,43
BEGIN DESCRIPTION:
21
END DESCRIPTION:
#Sta/Elev= 10
   -12.1    8.66    -2.1    8.66     -.6    9.56       0    9.56     2.4    7.86
     4.8    7.86     6.5    9.36       9   10.96      14   11.56      19   12.16
#Mann= 3 , 0 , 0
   -12.1    .033       0       0    .033       0       9    .033       0
#XS Ineff= 2 , 0
               0    9.56       9           10.96
Permanent Ineff=
       F       F
Bank Sta=0,9
XS Rating Curve= 0
Exp/Cntr=.3,.1

Type RM Length L Ch R = 1 ,1007.00 ,7,7,7
BEGIN DESCRIPTION:
20.007
END DESCRIPTION:
#Sta/Elev= 10
   -12.1     8.3    -2.1     8.3     -.6     9.2       0     9.2     2.4     7.5
     4.8     7.5     6.5       9       9    10.6      14    11.2      19    11.8
#Mann= 3 , 0 , 0
   -12.1    .033       0       0    .033       0       9    .033       0
#XS Ineff= 2 , 0
               0     9.2       9            10.6
Permanent Ineff=
       F       F
Bank Sta=0,9
XS Rating Curve= 0
Exp/Cntr=.3,.1

Type RM Length L Ch R = 1 ,1000.00 ,50,50,50
BEGIN DESCRIPTION:
20
END DESCRIPTION:
#Sta/Elev= 14
   -11.6    8.29    -1.6    8.29     -.8    8.99       0    8.99       2    7.89
     3.5    7.89     3.8    7.69     4.2    7.69     4.7    7.79     7.7    9.79
    10.7   11.79    11.2   11.79    11.9   11.29    21.9   11.29
#Mann= 3 , 0 , 0
   -11.6    .033       0       0    .033       0    10.7    .033       0
#XS Ineff= 2 , 0
               0    8.99    10.7           11.79
Permanent Ineff=
       F       F
Bank Sta=0,10.7
XS Rating Curve= 0
Exp/Cntr=.3,.1

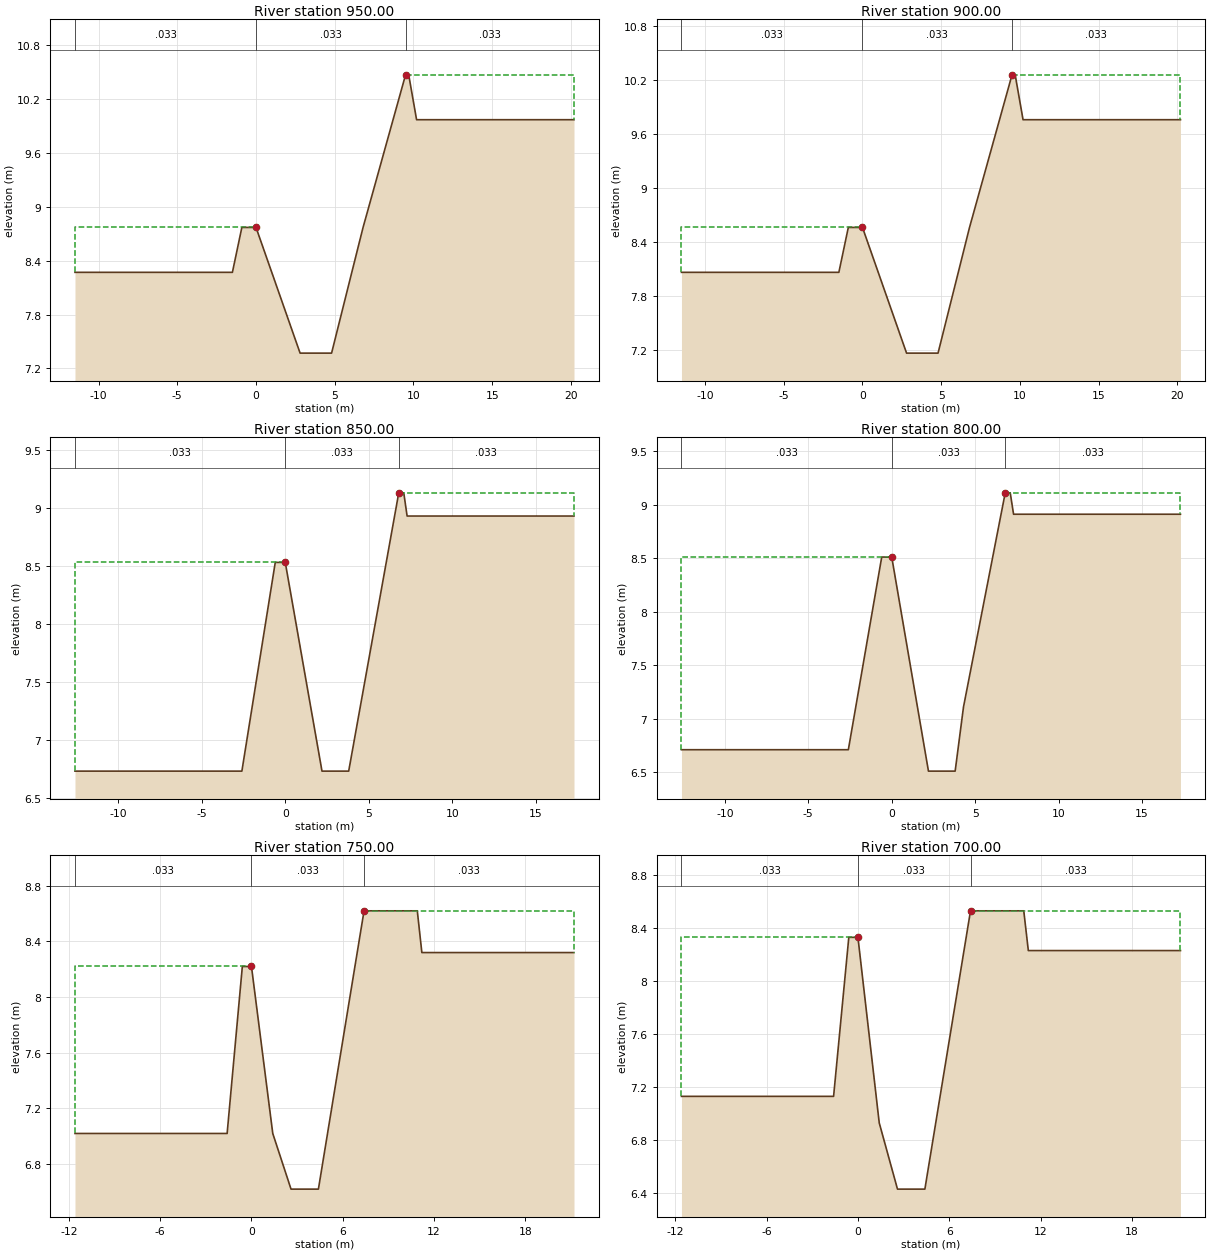
Type RM Length L Ch R = 1 ,950.00  ,50,50,50
BEGIN DESCRIPTION:
19
END DESCRIPTION:
#Sta/Elev= 11
   -11.5    8.27    -1.5    8.27     -.9    8.77       0    8.77     2.8    7.37
     4.8    7.37     6.8    8.77     9.5   10.47     9.7   10.47    10.2    9.97
    20.2    9.97
#Mann= 3 , 0 , 0
   -11.5    .033       0       0    .033       0     9.5    .033       0
#XS Ineff= 2 , 0
               0    8.77     9.5           10.47
Permanent Ineff=
       F       F
Bank Sta=0,9.5
XS Rating Curve= 0
Exp/Cntr=.3,.1

Type RM Length L Ch R = 1 ,900.00  ,50,50,50
BEGIN DESCRIPTION:
18
END DESCRIPTION:
#Sta/Elev= 11
   -11.5    8.06    -1.5    8.06     -.9    8.56       0    8.56     2.8    7.16
     4.8    7.16     6.8    8.56     9.5   10.26     9.7   10.26    10.2    9.76
    20.2    9.76
#Mann= 3 , 0 , 0
   -11.5    .033       0       0    .033       0     9.5    .033       0
#XS Ineff= 2 , 0
               0    8.56     9.5           10.26
Permanent Ineff=
       F       F
Bank Sta=0,9.5
XS Rating Curve= 0
Exp/Cntr=.3,.1

Type RM Length L Ch R = 1 ,850.00  ,50,50,50
BEGIN DESCRIPTION:
17
END DESCRIPTION:
#Sta/Elev= 11
   -12.6    6.73    -2.6    6.73     -.6    8.53       0    8.53     2.2    6.73
     3.8    6.73     4.3    7.13     6.8    9.13     7.1    9.13     7.3    8.93
    17.3    8.93
#Mann= 3 , 0 , 0
   -12.6    .033       0       0    .033       0     6.8    .033       0
#XS Ineff= 2 , 0
               0    8.53     6.8            9.13
Permanent Ineff=
       F       F
Bank Sta=0,6.8
XS Rating Curve= 0
Exp/Cntr=.3,.1

Type RM Length L Ch R = 1 ,800.00  ,50,50,50
BEGIN DESCRIPTION:
16
END DESCRIPTION:
#Sta/Elev= 11
   -12.6    6.71    -2.6    6.71     -.6    8.51       0    8.51     2.2    6.51
     3.8    6.51     4.3    7.11     6.8    9.11     7.1    9.11     7.3    8.91
    17.3    8.91
#Mann= 3 , 0 , 0
   -12.6    .033       0       0    .033       0     6.8    .033       0
#XS Ineff= 2 , 0
               0    8.51     6.8            9.11
Permanent Ineff=
       F       F
Bank Sta=0,6.8
XS Rating Curve= 0
Exp/Cntr=.3,.1

Type RM Length L Ch R = 1 ,750.00  ,50,50,50
BEGIN DESCRIPTION:
15
END DESCRIPTION:
#Sta/Elev= 11
   -11.6    7.02    -1.6    7.02     -.6    8.22       0    8.22     1.4    7.02
     2.6    6.62     4.4    6.62     7.4    8.62    10.9    8.62    11.2    8.32
    21.2    8.32
#Mann= 3 , 0 , 0
   -11.6    .033       0       0    .033       0     7.4    .033       0
#XS Ineff= 2 , 0
               0    8.22     7.4            8.62
Permanent Ineff=
       F       F
Bank Sta=0,7.4
XS Rating Curve= 0
Exp/Cntr=.3,.1

Type RM Length L Ch R = 1 ,700.00  ,7,7,7
BEGIN DESCRIPTION:
14
END DESCRIPTION:
#Sta/Elev= 11
   -11.6    7.13    -1.6    7.13     -.6    8.33       0    8.33     1.4    6.93
     2.6    6.43     4.4    6.43     7.4    8.53    10.9    8.53    11.2    8.23
    21.2    8.23
#Mann= 3 , 0 , 0
   -11.6    .033       0       0    .033       0     7.4    .033       0
#XS Ineff= 2 , 0
               0    8.33     7.4            8.53
Permanent Ineff=
       F       F
Bank Sta=0,7.4
XS Rating Curve= 0
Exp/Cntr=.3,.1

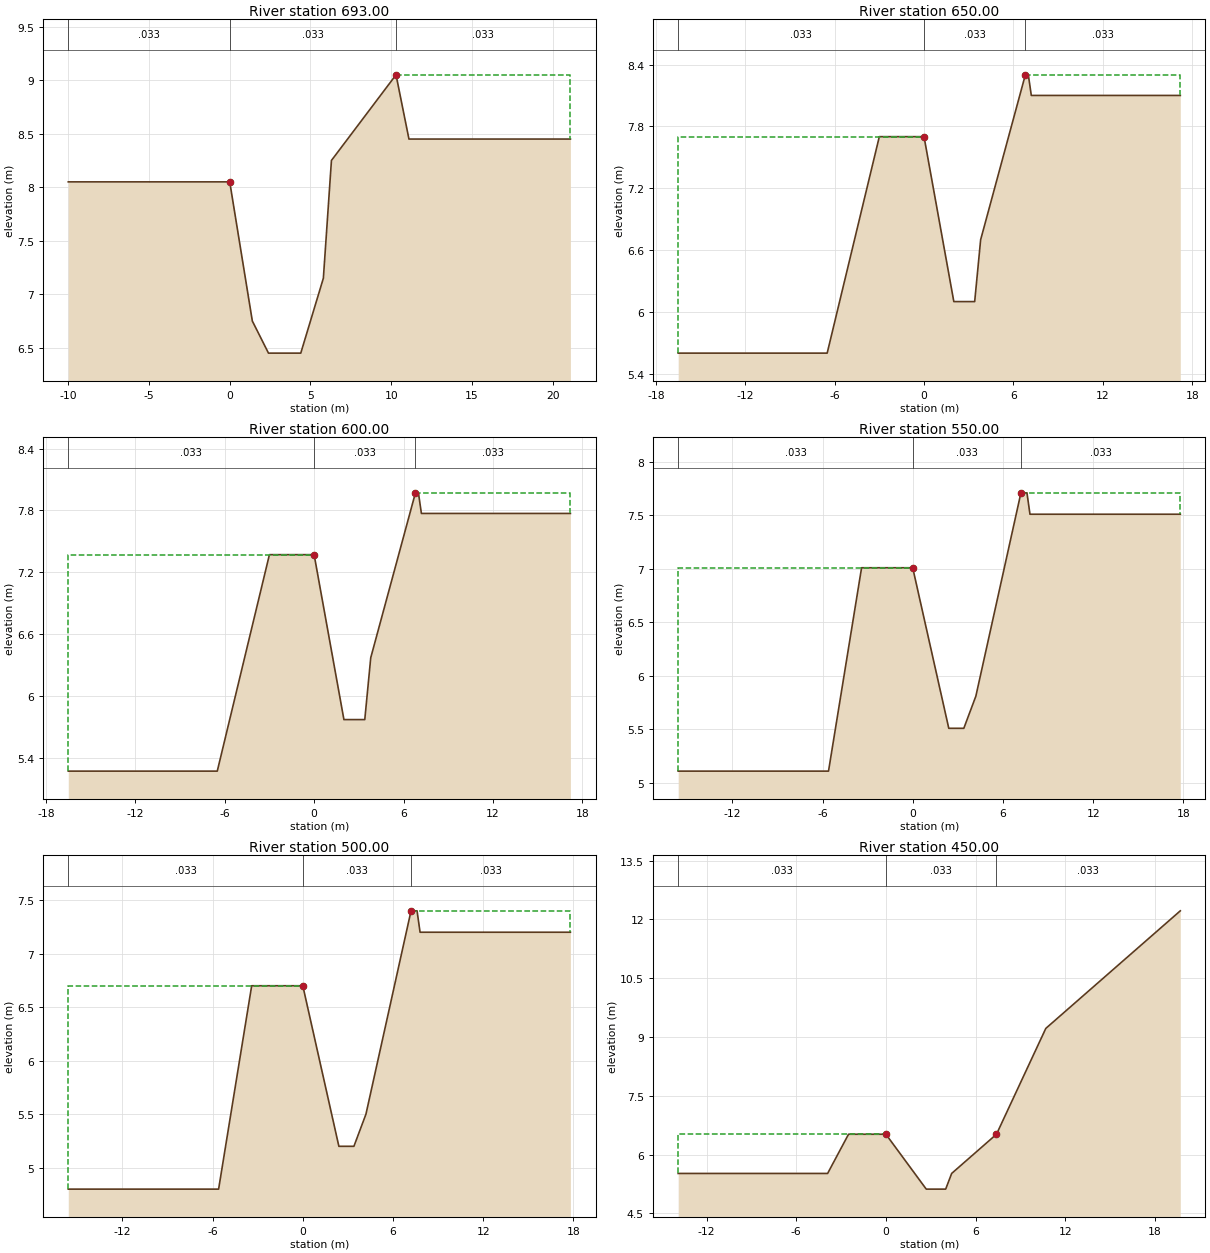
Type RM Length L Ch R = 1 ,693.00  ,43,43,43
BEGIN DESCRIPTION:
13.043
END DESCRIPTION:
#Sta/Elev= 10
     -10    8.05       0    8.05     1.4    6.75     2.4    6.45     4.4    6.45
     5.8    7.15     6.3    8.25    10.3    9.05    11.1    8.45    21.1    8.45
#Mann= 3 , 0 , 0
     -10    .033       0       0    .033       0    10.3    .033       0
#XS Ineff= 2 , 0
               0    8.05    10.3            9.05
Permanent Ineff=
       F       F
Bank Sta=0,10.3
XS Rating Curve= 0
Exp/Cntr=.3,.1

Type RM Length L Ch R = 1 ,650.00  ,50,50,50
BEGIN DESCRIPTION:
13
END DESCRIPTION:
#Sta/Elev= 11
   -16.5     5.6    -6.5     5.6      -3     7.7       0     7.7       2     6.1
     3.4     6.1     3.8     6.7     6.8     8.3       7     8.3     7.2     8.1
    17.2     8.1
#Mann= 3 , 0 , 0
   -16.5    .033       0       0    .033       0     6.8    .033       0
#XS Ineff= 2 , 0
               0     7.7     6.8             8.3
Permanent Ineff=
       F       F
Bank Sta=0,6.8
XS Rating Curve= 0
Exp/Cntr=.3,.1

Type RM Length L Ch R = 1 ,600.00  ,50,50,50
BEGIN DESCRIPTION:
12
END DESCRIPTION:
#Sta/Elev= 11
   -16.5    5.27    -6.5    5.27      -3    7.37       0    7.37       2    5.77
     3.4    5.77     3.8    6.37     6.8    7.97       7    7.97     7.2    7.77
    17.2    7.77
#Mann= 3 , 0 , 0
   -16.5    .033       0       0    .033       0     6.8    .033       0
#XS Ineff= 2 , 0
               0    7.37     6.8            7.97
Permanent Ineff=
       F       F
Bank Sta=0,6.8
XS Rating Curve= 0
Exp/Cntr=.3,.1

Type RM Length L Ch R = 1 ,550.00  ,50,50,50
BEGIN DESCRIPTION:
11
END DESCRIPTION:
#Sta/Elev= 11
   -15.6    5.11    -5.6    5.11    -3.4    7.01       0    7.01     2.4    5.51
     3.4    5.51     4.2    5.81     7.2    7.71     7.6    7.71     7.8    7.51
    17.8    7.51
#Mann= 3 , 0 , 0
   -15.6    .033       0       0    .033       0     7.2    .033       0
#XS Ineff= 2 , 0
               0    7.01     7.2            7.71
Permanent Ineff=
       F       F
Bank Sta=0,7.2
XS Rating Curve= 0
Exp/Cntr=.3,.1

Type RM Length L Ch R = 1 ,500.00  ,50,50,50
BEGIN DESCRIPTION:
10
END DESCRIPTION:
#Sta/Elev= 11
   -15.6     4.8    -5.6     4.8    -3.4     6.7       0     6.7     2.4     5.2
     3.4     5.2     4.2     5.5     7.2     7.4     7.6     7.4     7.8     7.2
    17.8     7.2
#Mann= 3 , 0 , 0
   -15.6    .033       0       0    .033       0     7.2    .033       0
#XS Ineff= 2 , 0
               0     6.7     7.2             7.4
Permanent Ineff=
       F       F
Bank Sta=0,7.2
XS Rating Curve= 0
Exp/Cntr=.3,.1

Type RM Length L Ch R = 1 ,450.00  ,50,50,50
BEGIN DESCRIPTION:
9
END DESCRIPTION:
#Sta/Elev= 12
   -13.9    5.52    -3.9    5.52    -2.5    6.52       0    6.52     2.7    5.12
       4    5.12     4.4    5.52     7.4    6.52    10.7    9.22    13.7   10.22
    16.7   11.22    19.7   12.22
#Mann= 3 , 0 , 0
   -13.9    .033       0       0    .033       0     7.4    .033       0
#XS Ineff= 2 , 0
               0    6.52     7.4            6.52
Permanent Ineff=
       F       F
Bank Sta=0,7.4
XS Rating Curve= 0
Exp/Cntr=.3,.1