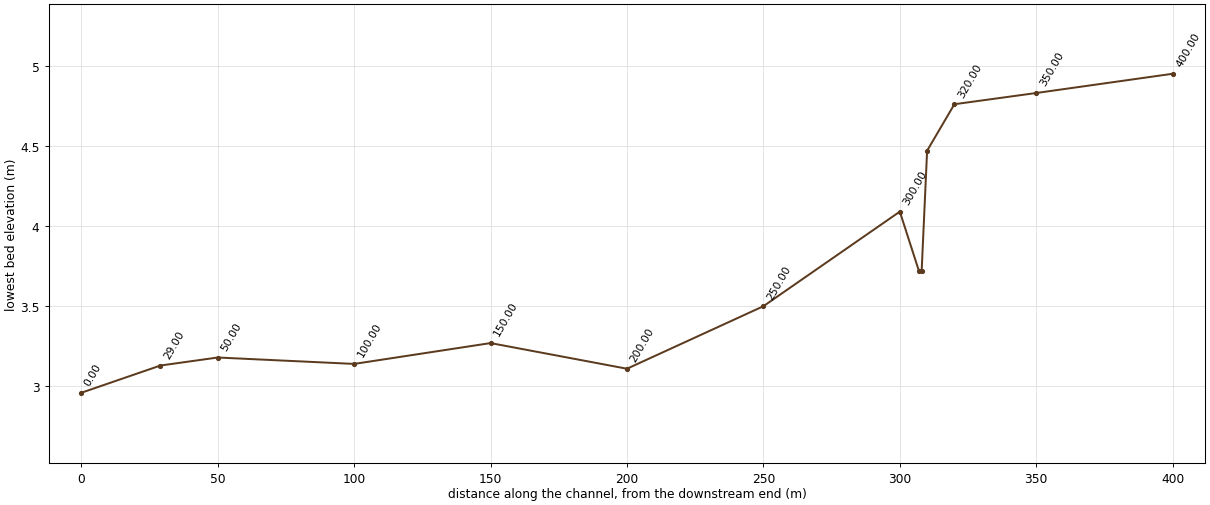
HEC-RAS study SKC.prj: SKC

--- SKC.g01 (geometry) --- (continued)

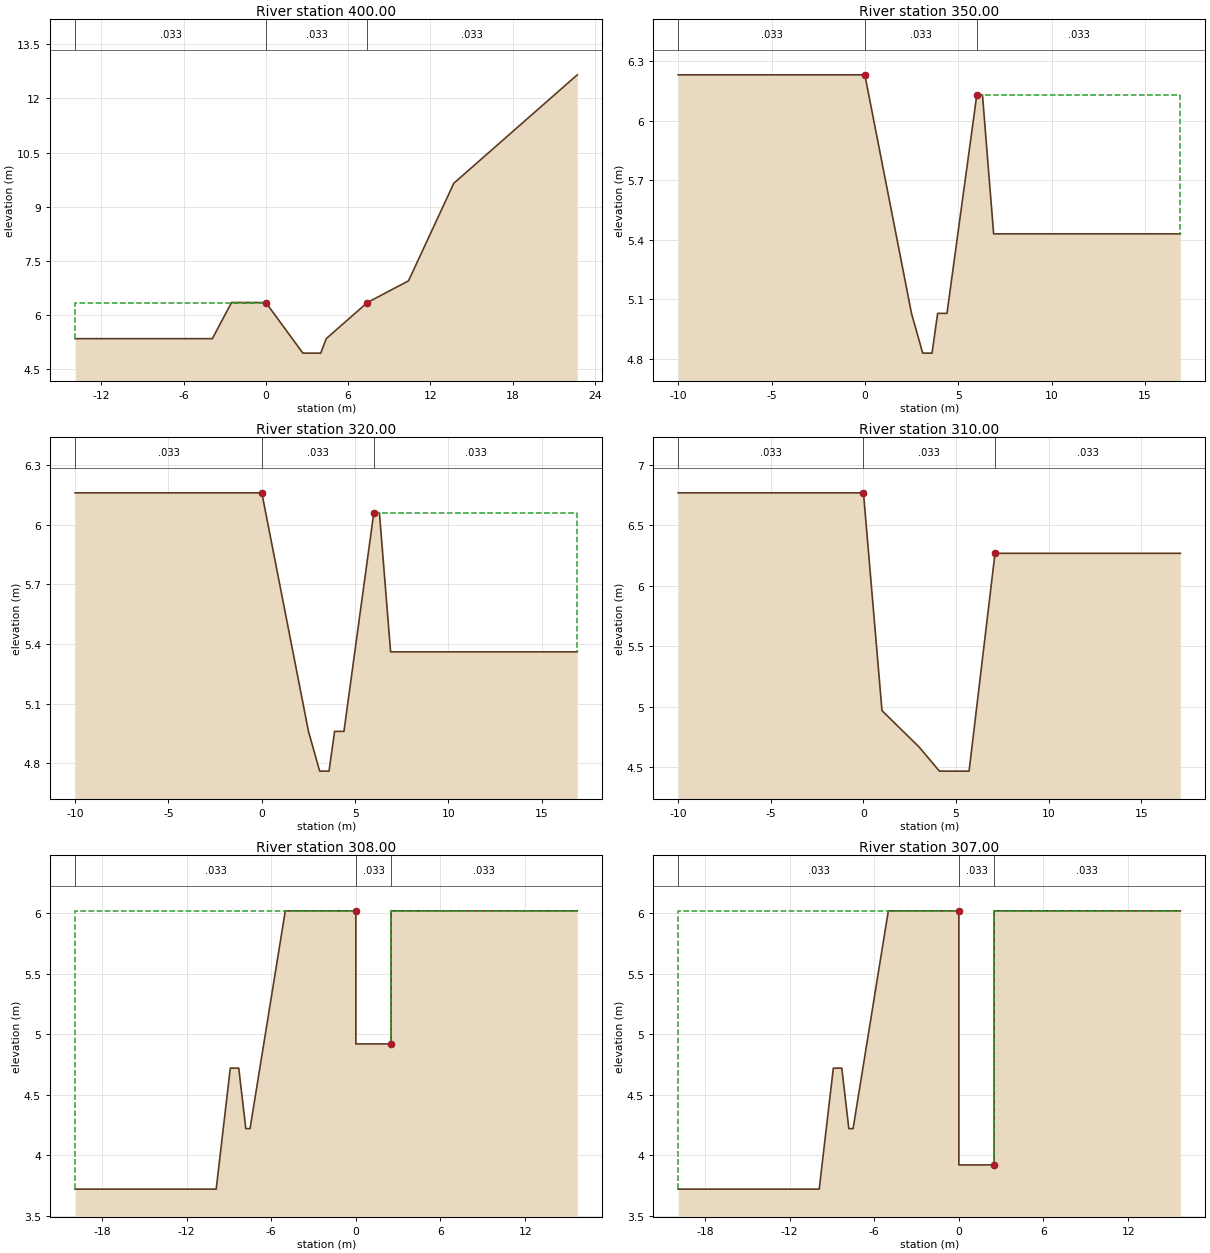
Type RM Length L Ch R = 1 ,400.00  ,50,50,50
BEGIN DESCRIPTION:
8
END DESCRIPTION:
#Sta/Elev= 13
   -13.9    5.35    -3.9    5.35    -2.5    6.35       0    6.35     2.7    4.95
       4    4.95     4.4    5.35     7.4    6.35    10.4    6.95    13.7    9.65
    16.7   10.65    19.7   11.65    22.7   12.65
#Mann= 3 , 0 , 0
   -13.9    .033       0       0    .033       0     7.4    .033       0
#XS Ineff= 2 , 0
               0    6.35     7.4            6.35
Permanent Ineff=
       F       F
Bank Sta=0,7.4
XS Rating Curve= 0
Exp/Cntr=.3,.1

Type RM Length L Ch R = 1 ,350.00  ,30,30,30
BEGIN DESCRIPTION:
7
END DESCRIPTION:
#Sta/Elev= 11
     -10    6.23       0    6.23     2.5    5.03     3.1    4.83     3.6    4.83
     3.9    5.03     4.4    5.03       6    6.13     6.3    6.13     6.9    5.43
    16.9    5.43
#Mann= 3 , 0 , 0
     -10    .033       0       0    .033       0       6    .033       0
#XS Ineff= 2 , 0
               0    6.23       6            6.13
Permanent Ineff=
       F       F
Bank Sta=0,6
XS Rating Curve= 0
Exp/Cntr=.3,.1

Type RM Length L Ch R = 1 ,320.00  ,10,10,10
BEGIN DESCRIPTION:
6.02
END DESCRIPTION:
#Sta/Elev= 11
     -10    6.16       0    6.16     2.5    4.96     3.1    4.76     3.6    4.76
     3.9    4.96     4.4    4.96       6    6.06     6.3    6.06     6.9    5.36
    16.9    5.36
#Mann= 3 , 0 , 0
     -10    .033       0       0    .033       0       6    .033       0
#XS Ineff= 2 , 0
               0    6.16       6            6.06
Permanent Ineff=
       F       F
Bank Sta=0,6
XS Rating Curve= 0
Exp/Cntr=.3,.1

Type RM Length L Ch R = 1 ,310.00  ,2,2,2
BEGIN DESCRIPTION:
6.01
END DESCRIPTION:
#Sta/Elev= 8
     -10    6.77       0    6.77       1    4.97       3    4.67     4.1    4.47
     5.7    4.47     7.1    6.27    17.1    6.27
#Mann= 3 , 0 , 0
     -10    .033       0       0    .033       0     7.1    .033       0
#XS Ineff= 2 , 0
               0    6.77     7.1            6.27
Permanent Ineff=
       F       F
Bank Sta=0,7.1
XS Rating Curve= 0
Exp/Cntr=.3,.1

Type RM Length L Ch R = 1 ,308.00  ,1,1,1
BEGIN DESCRIPTION:
6.008
END DESCRIPTION:
#Sta/Elev= 13
   -19.9    3.72    -9.9    3.72    -8.9    4.72    -8.3    4.72    -7.8    4.22
    -7.5    4.22      -5    6.02       0    6.02       0    4.92     2.5    4.92
     2.5    6.02     5.7    6.02    15.7    6.02
#Mann= 3 , 0 , 0
   -19.9    .033       0       0    .033       0     2.5    .033       0
#XS Ineff= 2 , 0
               0    6.02     2.5            6.02
Permanent Ineff=
       F       F
Bank Sta=0,2.5
XS Rating Curve= 0
Exp/Cntr=.3,.1

Type RM Length L Ch R = 1 ,307.00  ,7,7,7
BEGIN DESCRIPTION:
6.007
END DESCRIPTION:
#Sta/Elev= 15
   -19.9    3.72    -9.9    3.72    -8.9    4.72    -8.3    4.72    -7.8    4.22
    -7.5    4.22      -5    6.02       0    6.02       0    4.92       0    3.92
     2.5    3.92     2.5    4.92     2.5    6.02     5.7    6.02    15.7    6.02
#Mann= 3 , 0 , 0
   -19.9    .033       0       0    .033       0     2.5    .033       0
#XS Ineff= 2 , 0
               0    6.02     2.5            6.02
Permanent Ineff=
       F       F
Bank Sta=0,2.5
XS Rating Curve= 0
Exp/Cntr=.3,.1

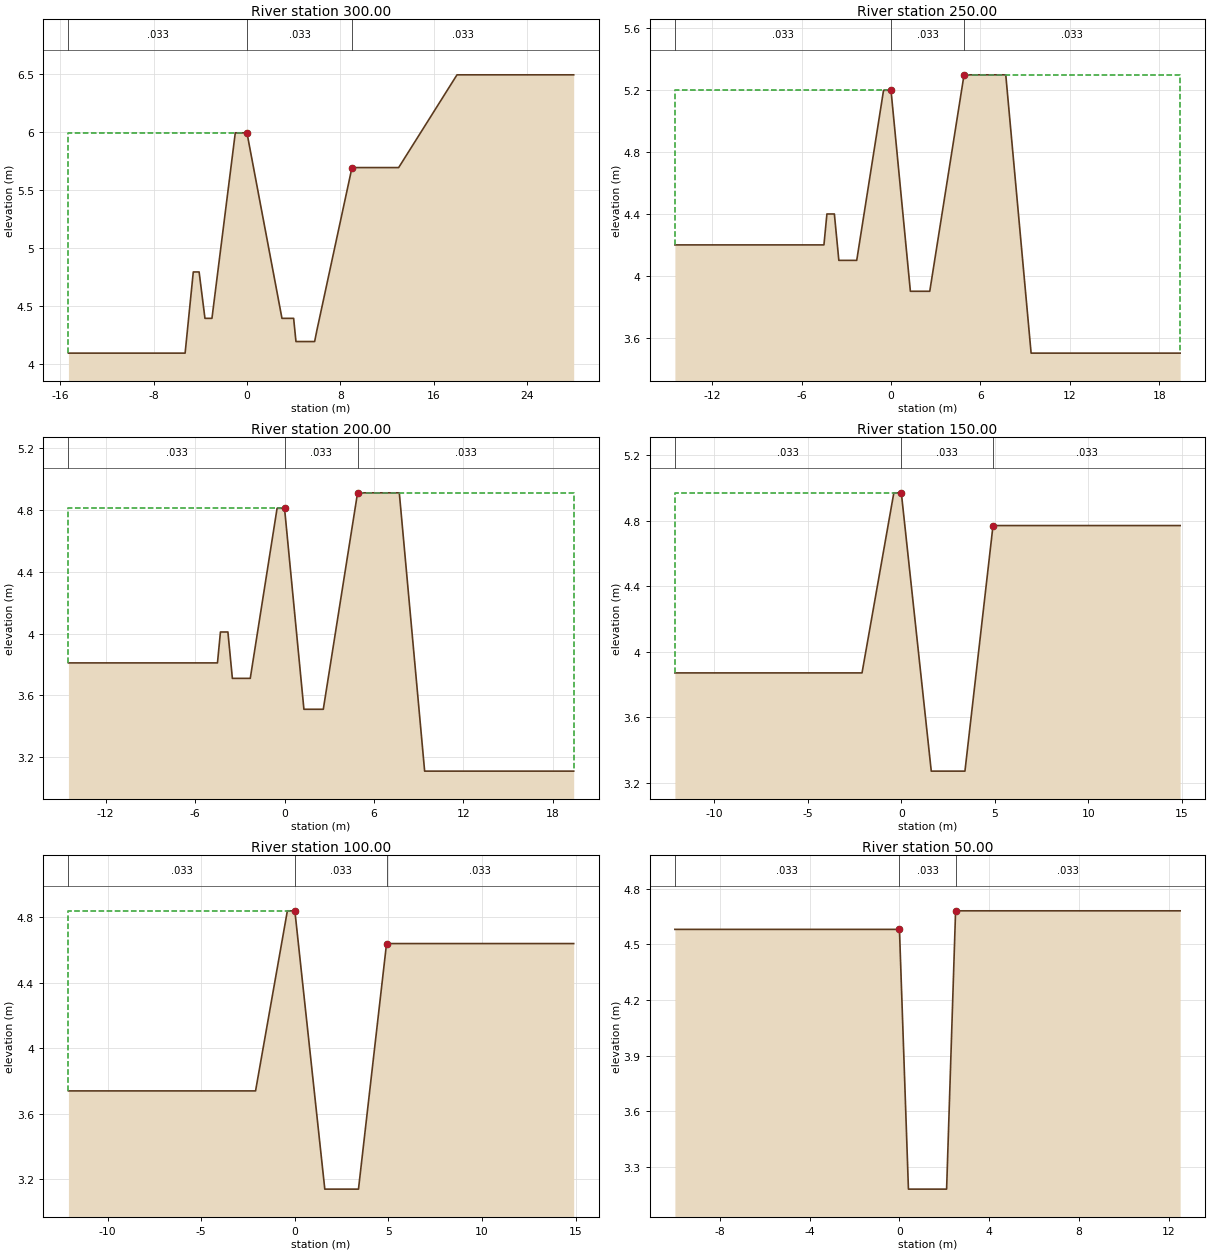
Type RM Length L Ch R = 1 ,300.00  ,50,50,50
BEGIN DESCRIPTION:
6
END DESCRIPTION:
#Sta/Elev= 17
   -15.3    4.09    -5.3    4.09    -4.6    4.79    -4.1    4.79    -3.6    4.39
      -3    4.39      -1    5.99       0    5.99       3    4.39       4    4.39
     4.2    4.19     5.8    4.19       6    4.29       9    5.69      13    5.69
      18    6.49      28    6.49
#Mann= 3 , 0 , 0
   -15.3    .033       0       0    .033       0       9    .033       0
#XS Ineff= 2 , 0
               0    5.99       9            5.69
Permanent Ineff=
       F       F
Bank Sta=0,9
XS Rating Curve= 0
Exp/Cntr=.3,.1

Type RM Length L Ch R = 1 ,250.00  ,50,50,50
BEGIN DESCRIPTION:
5
END DESCRIPTION:
#Sta/Elev= 14
   -14.5     4.2    -4.5     4.2    -4.3     4.4    -3.8     4.4    -3.5     4.1
    -2.3     4.1     -.5     5.2       0     5.2     1.3     3.9     2.6     3.9
     4.9     5.3     7.7     5.3     9.4     3.5    19.4     3.5
#Mann= 3 , 0 , 0
   -14.5    .033       0       0    .033       0     4.9    .033       0
#XS Ineff= 2 , 0
               0     5.2     4.9             5.3
Permanent Ineff=
       F       F
Bank Sta=0,4.9
XS Rating Curve= 0
Exp/Cntr=.3,.1

Type RM Length L Ch R = 1 ,200.00  ,50,50,50
BEGIN DESCRIPTION:
4
END DESCRIPTION:
#Sta/Elev= 14
   -14.5    3.81    -4.5    3.81    -4.3    4.01    -3.8    4.01    -3.5    3.71
    -2.3    3.71     -.5    4.81       0    4.81     1.3    3.51     2.6    3.51
     4.9    4.91     7.7    4.91     9.4    3.11    19.4    3.11
#Mann= 3 , 0 , 0
   -14.5    .033       0       0    .033       0     4.9    .033       0
#XS Ineff= 2 , 0
               0    4.81     4.9            4.91
Permanent Ineff=
       F       F
Bank Sta=0,4.9
XS Rating Curve= 0
Exp/Cntr=.3,.1

Type RM Length L Ch R = 1 ,150.00  ,50,50,50
BEGIN DESCRIPTION:
3
END DESCRIPTION:
#Sta/Elev= 8
   -12.1    3.87    -2.1    3.87     -.4    4.97       0    4.97     1.6    3.27
     3.4    3.27     4.9    4.77    14.9    4.77
#Mann= 3 , 0 , 0
   -12.1    .033       0       0    .033       0     4.9    .033       0
#XS Ineff= 2 , 0
               0    4.97     4.9            4.77
Permanent Ineff=
       F       F
Bank Sta=0,4.9
XS Rating Curve= 0
Exp/Cntr=.3,.1

Type RM Length L Ch R = 1 ,100.00  ,50,50,50
BEGIN DESCRIPTION:
2
END DESCRIPTION:
#Sta/Elev= 8
   -12.1    3.74    -2.1    3.74     -.4    4.84       0    4.84     1.6    3.14
     3.4    3.14     4.9    4.64    14.9    4.64
#Mann= 3 , 0 , 0
   -12.1    .033       0       0    .033       0     4.9    .033       0
#XS Ineff= 2 , 0
               0    4.84     4.9            4.64
Permanent Ineff=
       F       F
Bank Sta=0,4.9
XS Rating Curve= 0
Exp/Cntr=.3,.1

Type RM Length L Ch R = 1 ,50.00   ,21,21,21
BEGIN DESCRIPTION:
1
END DESCRIPTION:
#Sta/Elev= 6
     -10    4.58       0    4.58      .4    3.18     2.1    3.18     2.5    4.68
    12.5    4.68
#Mann= 3 , 0 , 0
     -10    .033       0       0    .033       0     2.5    .033       0
#XS Ineff= 2 , 0
               0    4.58     2.5            4.68
Permanent Ineff=
       F       F
Bank Sta=0,2.5
XS Rating Curve= 0
Exp/Cntr=.3,.1

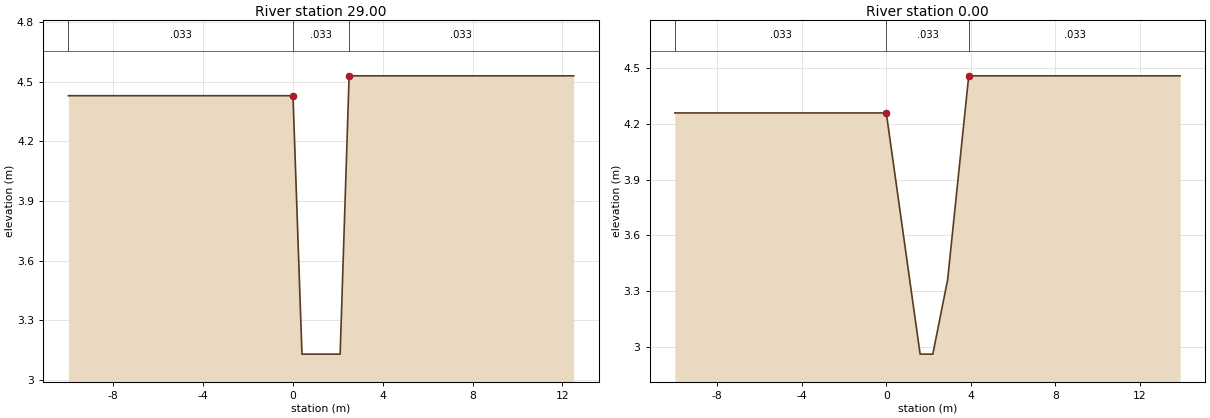
Type RM Length L Ch R = 1 ,29.00   ,29,29,29
BEGIN DESCRIPTION:
0.029
END DESCRIPTION:
#Sta/Elev= 6
     -10    4.43       0    4.43      .4    3.13     2.1    3.13     2.5    4.53
    12.5    4.53
#Mann= 3 , 0 , 0
     -10    .033       0       0    .033       0     2.5    .033       0
#XS Ineff= 2 , 0
               0    4.43     2.5            4.53
Permanent Ineff=
       F       F
Bank Sta=0,2.5
XS Rating Curve= 0
Exp/Cntr=.3,.1

Type RM Length L Ch R = 1 ,0.00    ,0,0,0
BEGIN DESCRIPTION:
0
END DESCRIPTION:
#Sta/Elev= 7
     -10    4.26       0    4.26     1.6    2.96     2.2    2.96     2.9    3.36
     3.9    4.46    13.9    4.46
#Mann= 3 , 0 , 0
     -10    .033       0       0    .033       0     3.9    .033       0
#XS Ineff= 2 , 0
               0    4.26     3.9            4.46
Permanent Ineff=
       F       F
Bank Sta=0,3.9
XS Rating Curve= 0
Exp/Cntr=.3,.1

Chan Stop Cuts=-1