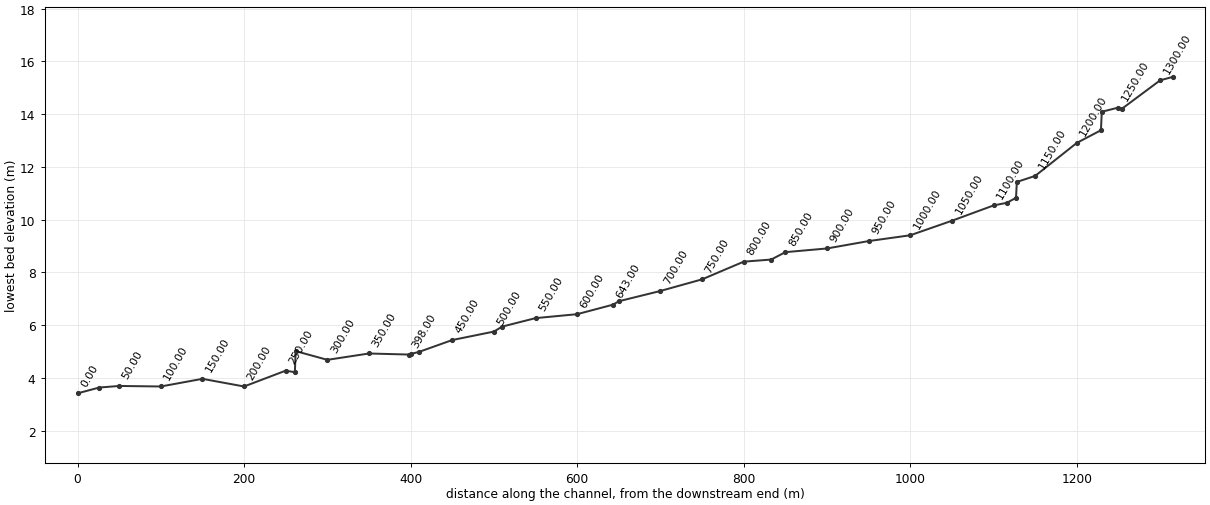
--- OKOK.prj (project) ---

Proj Title=OKOK
Current Plan=p01
Default Exp/Contr=.3,.1
SI Units
Geom File=g01
Flow File=f01
Plan File=p01
Y Axis Title=Elevation
X Axis Title(PF)=Main Channel Distance
X Axis Title(XS)=Station
BEGIN DESCRIPTION:
           BACK WATER COMPUTATION
      APPLICATION OF HEC-2 BY Samju Construction Engineering
      YOKOK-STREEM : 30 YR
END DESCRIPTION:
DSS Export Rating Curves= 0
DSS Export Rating Curve Sorted= 0
DSS Export Volume Flow Curves= 0
DXF OffsetX= 0
DXF OffsetY= 0
DXF ScaleX= 1
DXF ScaleY= 10

--- OKOK.p01 (plan) ---

Plan Title=Imported Plan 01
Version=Version 3.0.1  Mar 2001
Short Identifier=Imported Pla
Geom File=g01
Flow File=f01
Subcritical Flow
K Sum by GR= 0
Std Step Tol= 0.003
Critical Tol= 0.003
Num of Std Step Trials= 20
Max Error Tol= 0.1
Flow Tol Ratio= 0.001
Split Flow NTrial= 30
Split Flow Tol= 0.02
Split Flow Ratio= 0.02
Log Output Level= 0
Friction Slope Method= 1
Unsteady Friction Slope Method= 2
Parabolic Critical Depth
Global Vel Dist= 0 , 0 , 0
Global Log Level= 0
CheckData=True
Encroach Param=-1 ,0,0, 0
Computation Interval=1HOUR
Output Interval=1HOUR
Run HTab= 0
Run UNet= 0
Run PostProcess= 0
UNET Theta= 1
UNET ZTol= 0.02
UNET ZSATol= 0.1
UNET MxIter= 20
UNET MaxInSteps= 20
UNET DtIC= 0
UNET DtMin= 0
UNET MaxCRTS= 20
UNET WFStab= 2
UNET SFStab= 1
UNET WFX= 1
UNET SFX= 1
UNET Convert EG Bridges=-1
UNET Use Existing IB Tables=-1
Instantaneous Interval=1HOUR
Write IC File= 0
Write Velocity= 0
Write Detailed= 0

--- OKOK.f01 (steady flow) ---

Flow Title=Imported Flow 01
Version=Version 3.0.1  Mar 2001
Number of Profiles= 5
Profile Names=10YR,20YR,30YR,50YR,80YR
River Rch & RM=RIVER-1,Reach-1         ,26.015
    4.12    4.54    4.78    5.09    5.37
River Rch & RM=RIVER-1,Reach-1         ,10
    5.35    5.89    6.21    6.61    6.98
River Rch & RM=YOKOK,YOKOK           ,1315.00
    4.12    4.54    4.78    5.09    5.37
River Rch & RM=YOKOK,YOKOK           ,500.00
    5.35    5.89    6.21    6.61    6.98
Boundary for River Rch & Prof#=YOKOK,YOKOK           , 1
Up Type= 0
Dn Type= 3
Dn Slope=.06
Boundary for River Rch & Prof#=YOKOK,YOKOK           , 2
Up Type= 0
Dn Type= 3
Dn Slope=.06
Boundary for River Rch & Prof#=YOKOK,YOKOK           , 3
Up Type= 0
Dn Type= 3
Dn Slope=.06
Boundary for River Rch & Prof#=YOKOK,YOKOK           , 4
Up Type= 0
Dn Type= 3
Dn Slope=.06
Boundary for River Rch & Prof#=YOKOK,YOKOK           , 5
Up Type= 0
Dn Type= 3
Dn Slope=.06
DSS Import GetInterval= 0
DSS Import GetPeak= 0
DSS Import FillOption= 0

--- OKOK.g01 (geometry) ---

Geom Title=Imported Geom 01
Version=Version 3.0.1  Mar 2001

River Reach=YOKOK           ,YOKOK
Reach XY= 2
              .5             .95              .5             .05

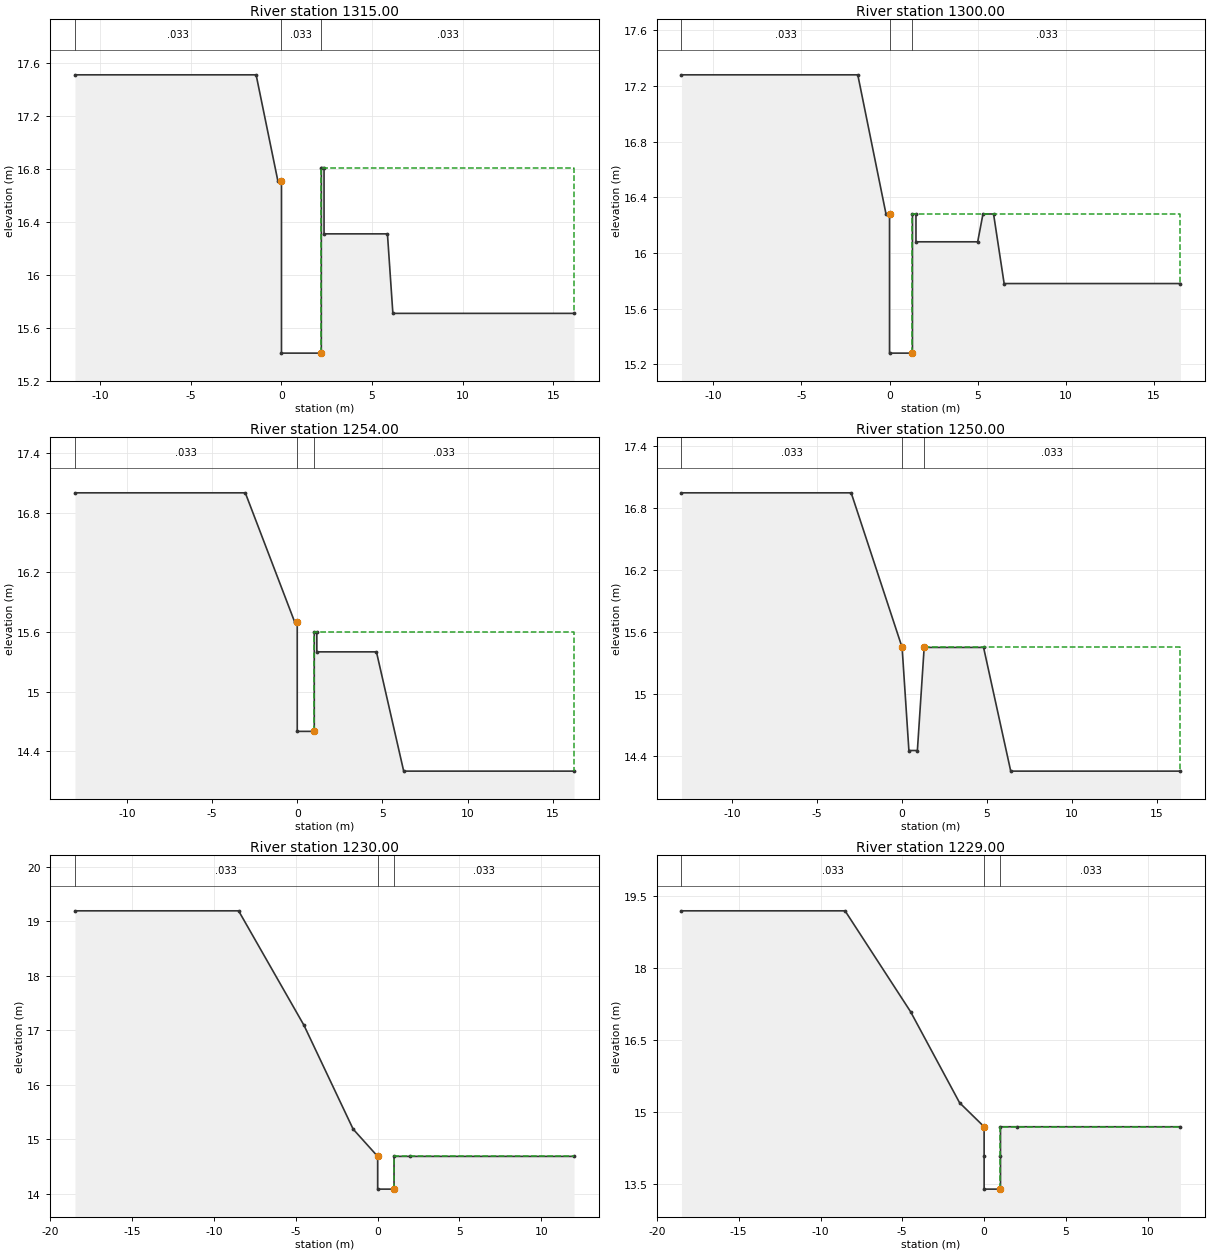
Type RM Length L Ch R = 1 ,1315.00 ,15,15,15
BEGIN DESCRIPTION:
26.015
END DESCRIPTION:
#Sta/Elev= 12
   -11.4   17.51    -1.4   17.51     -.2   16.71       0   16.71       0   15.41
     2.2   15.41     2.2   16.81    2.35   16.81    2.35   16.31    5.85   16.31
    6.15   15.71   16.15   15.71
#Mann= 3 , 0 , 0
   -11.4    .033       0       0    .033       0     2.2    .033       0
#XS Ineff= 2 , 0
               0   16.71     2.2           16.81
Permanent Ineff=
       F       F
Bank Sta=0,2.2
XS Rating Curve= 0
Exp/Cntr=.3,.1

Type RM Length L Ch R = 1 ,1300.00 ,46,46,46
BEGIN DESCRIPTION:
26
END DESCRIPTION:
#Sta/Elev= 14
   -11.8   17.28    -1.8   17.28     -.2   16.28       0   16.28       0   15.28
     1.3   15.28     1.3   16.28     1.5   16.28     1.5   16.08       5   16.08
     5.3   16.28     5.9   16.28     6.5   15.78    16.5   15.78
#Mann= 3 , 0 , 0
   -11.8    .033       0       0    .033       0     1.3    .033       0
#XS Ineff= 2 , 0
               0   16.28     1.3           16.28
Permanent Ineff=
       F       F
Bank Sta=0,1.3
XS Rating Curve= 0
Exp/Cntr=.3,.1

Type RM Length L Ch R = 1 ,1254.00 ,4,4,4
BEGIN DESCRIPTION:
25.004
END DESCRIPTION:
#Sta/Elev= 12
  -13.05      17   -3.05      17    -.15    15.7       0    15.7       0    14.6
       1    14.6       1    15.6    1.15    15.6    1.15    15.4    4.65    15.4
    6.25    14.2   16.25    14.2
#Mann= 3 , 0 , 0
  -13.05    .033       0       0    .033       0       1    .033       0
#XS Ineff= 2 , 0
               0    15.7       1            15.6
Permanent Ineff=
       F       F
Bank Sta=0,1
XS Rating Curve= 0
Exp/Cntr=.3,.1

Type RM Length L Ch R = 1 ,1250.00 ,20,20,20
BEGIN DESCRIPTION:
25
END DESCRIPTION:
#Sta/Elev= 9
     -13   16.95      -3   16.95       0   15.45      .4   14.45      .9   14.45
     1.3   15.45     4.8   15.45     6.4   14.25    16.4   14.25
#Mann= 3 , 0 , 0
     -13    .033       0       0    .033       0     1.3    .033       0
#XS Ineff= 2 , 0
               0   15.45     1.3           15.45
Permanent Ineff=
       F       F
Bank Sta=0,1.3
XS Rating Curve= 0
Exp/Cntr=.3,.1

Type RM Length L Ch R = 1 ,1230.00 ,1,1,1
BEGIN DESCRIPTION:
24.03
END DESCRIPTION:
#Sta/Elev= 10
   -18.5   19.19    -8.5   19.19    -4.5   17.09    -1.5   15.19       0   14.69
       0   14.09       1   14.09       1   14.69       2   14.69      12   14.69
#Mann= 3 , 0 , 0
   -18.5    .033       0       0    .033       0       1    .033       0
#XS Ineff= 2 , 0
               0   14.69       1           14.69
Permanent Ineff=
       F       F
Bank Sta=0,1
XS Rating Curve= 0
Exp/Cntr=.3,.1

Type RM Length L Ch R = 1 ,1229.00 ,29,29,29
BEGIN DESCRIPTION:
24.029
END DESCRIPTION:
#Sta/Elev= 12
   -18.5   19.19    -8.5   19.19    -4.5   17.09    -1.5   15.19       0   14.69
       0   14.09       0   13.39       1   13.39       1   14.09       1   14.69
       2   14.69      12   14.69
#Mann= 3 , 0 , 0
   -18.5    .033       0       0    .033       0       1    .033       0
#XS Ineff= 2 , 0
               0   14.69       1           14.69
Permanent Ineff=
       F       F
Bank Sta=0,1
XS Rating Curve= 0
Exp/Cntr=.3,.1

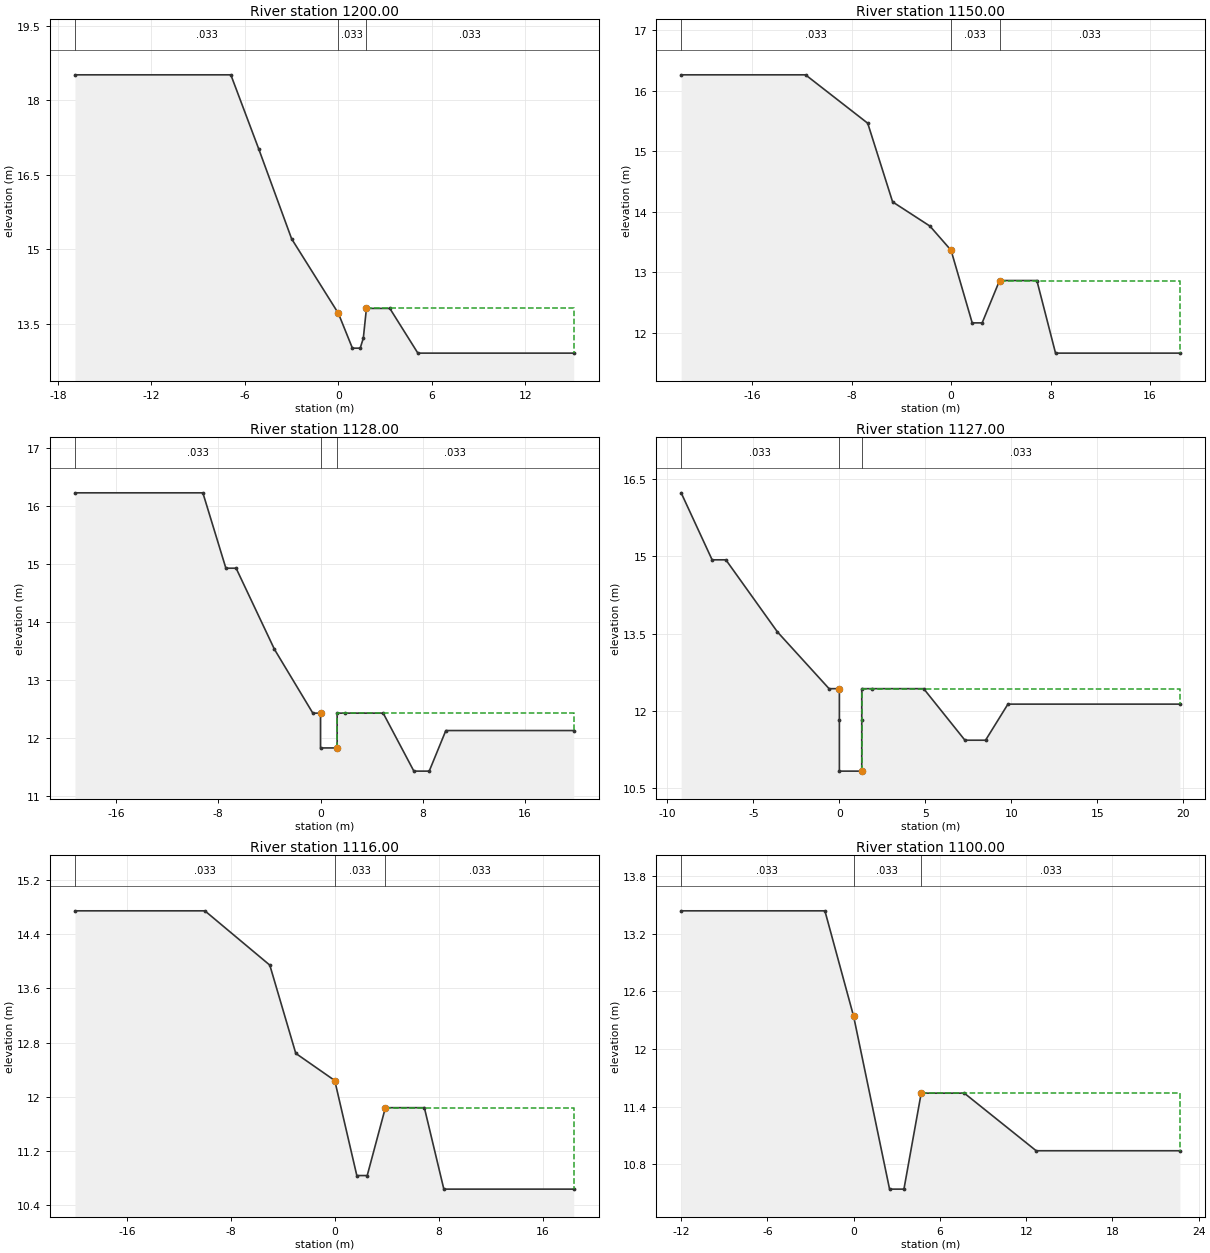
Type RM Length L Ch R = 1 ,1200.00 ,50,50,50
BEGIN DESCRIPTION:
24
END DESCRIPTION:
#Sta/Elev= 12
   -16.9   18.51    -6.9   18.51    -5.1   17.01      -3   15.21       0   13.71
      .9   13.01     1.4   13.01     1.6   13.21     1.8   13.81     3.3   13.81
     5.1   12.91    15.1   12.91
#Mann= 3 , 0 , 0
   -16.9    .033       0       0    .033       0     1.8    .033       0
#XS Ineff= 2 , 0
               0   13.71     1.8           13.81
Permanent Ineff=
       F       F
Bank Sta=0,1.8
XS Rating Curve= 0
Exp/Cntr=.3,.1

Type RM Length L Ch R = 1 ,1150.00 ,22,22,22
BEGIN DESCRIPTION:
23
END DESCRIPTION:
#Sta/Elev= 12
   -21.7   16.26   -11.7   16.26    -6.7   15.46    -4.7   14.16    -1.7   13.76
       0   13.36     1.7   12.16     2.5   12.16     3.9   12.86     6.9   12.86
     8.4   11.66    18.4   11.66
#Mann= 3 , 0 , 0
   -21.7    .033       0       0    .033       0     3.9    .033       0
#XS Ineff= 2 , 0
               0   13.36     3.9           12.86
Permanent Ineff=
       F       F
Bank Sta=0,3.9
XS Rating Curve= 0
Exp/Cntr=.3,.1

Type RM Length L Ch R = 1 ,1128.00 ,1,1,1
BEGIN DESCRIPTION:
22.028
END DESCRIPTION:
#Sta/Elev= 16
   -19.2   16.23    -9.2   16.23    -7.4   14.93    -6.6   14.93    -3.6   13.53
     -.6   12.43       0   12.43       0   11.83     1.3   11.83     1.3   12.43
     1.9   12.43     4.9   12.43     7.3   11.43     8.5   11.43     9.8   12.13
    19.8   12.13
#Mann= 3 , 0 , 0
   -19.2    .033       0       0    .033       0     1.3    .033       0
#XS Ineff= 2 , 0
               0   12.43     1.3           12.43
Permanent Ineff=
       F       F
Bank Sta=0,1.3
XS Rating Curve= 0
Exp/Cntr=.3,.1

Type RM Length L Ch R = 1 ,1127.00 ,11,11,11
BEGIN DESCRIPTION:
22.027
END DESCRIPTION:
#Sta/Elev= 17
    -9.2   16.23    -7.4   14.93    -6.6   14.93    -3.6   13.53     -.6   12.43
       0   12.43       0   11.83       0   10.83     1.3   10.83     1.3   11.83
     1.3   12.43     1.9   12.43     4.9   12.43     7.3   11.43     8.5   11.43
     9.8   12.13    19.8   12.13
#Mann= 3 , 0 , 0
    -9.2    .033       0       0    .033       0     1.3    .033       0
#XS Ineff= 2 , 0
               0   12.43     1.3           12.43
Permanent Ineff=
       F       F
Bank Sta=0,1.3
XS Rating Curve= 0
Exp/Cntr=.3,.1

Type RM Length L Ch R = 1 ,1116.00 ,16,16,16
BEGIN DESCRIPTION:
22.016
END DESCRIPTION:
#Sta/Elev= 11
     -20   14.74     -10   14.74      -5   13.94      -3   12.64       0   12.24
     1.7   10.84     2.5   10.84     3.9   11.84     6.9   11.84     8.4   10.64
    18.4   10.64
#Mann= 3 , 0 , 0
     -20    .033       0       0    .033       0     3.9    .033       0
#XS Ineff= 2 , 0
               0   12.24     3.9           11.84
Permanent Ineff=
       F       F
Bank Sta=0,3.9
XS Rating Curve= 0
Exp/Cntr=.3,.1

Type RM Length L Ch R = 1 ,1100.00 ,50,50,50
BEGIN DESCRIPTION:
22
END DESCRIPTION:
#Sta/Elev= 9
     -12   13.44      -2   13.44       0   12.34     2.5   10.54     3.5   10.54
     4.7   11.54     7.7   11.54    12.7   10.94    22.7   10.94
#Mann= 3 , 0 , 0
     -12    .033       0       0    .033       0     4.7    .033       0
#XS Ineff= 2 , 0
               0   12.34     4.7           11.54
Permanent Ineff=
       F       F
Bank Sta=0,4.7
XS Rating Curve= 0
Exp/Cntr=.3,.1

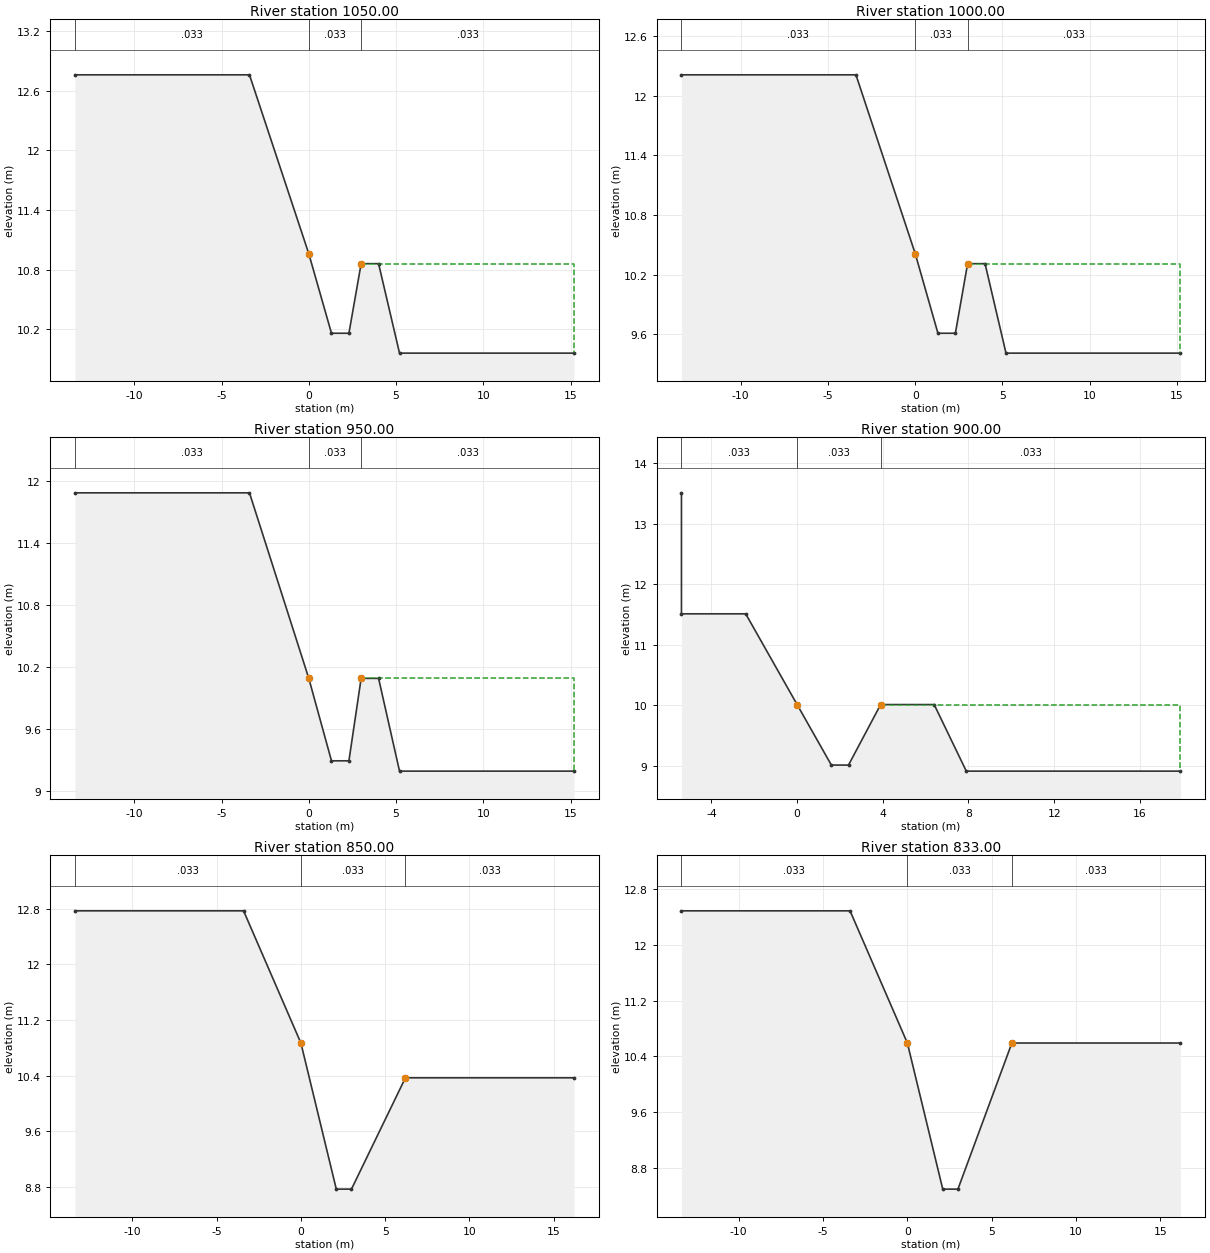
Type RM Length L Ch R = 1 ,1050.00 ,50,50,50
BEGIN DESCRIPTION:
21
END DESCRIPTION:
#Sta/Elev= 9
   -13.4   12.76    -3.4   12.76       0   10.96     1.3   10.16     2.3   10.16
       3   10.86       4   10.86     5.2    9.96    15.2    9.96
#Mann= 3 , 0 , 0
   -13.4    .033       0       0    .033       0       3    .033       0
#XS Ineff= 2 , 0
               0   10.96       3           10.86
Permanent Ineff=
       F       F
Bank Sta=0,3
XS Rating Curve= 0
Exp/Cntr=.3,.1

Type RM Length L Ch R = 1 ,1000.00 ,50,50,50
BEGIN DESCRIPTION:
20
END DESCRIPTION:
#Sta/Elev= 9
   -13.4   12.21    -3.4   12.21       0   10.41     1.3    9.61     2.3    9.61
       3   10.31       4   10.31     5.2    9.41    15.2    9.41
#Mann= 3 , 0 , 0
   -13.4    .033       0       0    .033       0       3    .033       0
#XS Ineff= 2 , 0
               0   10.41       3           10.31
Permanent Ineff=
       F       F
Bank Sta=0,3
XS Rating Curve= 0
Exp/Cntr=.3,.1

Type RM Length L Ch R = 1 ,950.00  ,50,50,50
BEGIN DESCRIPTION:
19
END DESCRIPTION:
#Sta/Elev= 9
   -13.4   11.89    -3.4   11.89       0   10.09     1.3    9.29     2.3    9.29
       3   10.09       4   10.09     5.2    9.19    15.2    9.19
#Mann= 3 , 0 , 0
   -13.4    .033       0       0    .033       0       3    .033       0
#XS Ineff= 2 , 0
               0   10.09       3           10.09
Permanent Ineff=
       F       F
Bank Sta=0,3
XS Rating Curve= 0
Exp/Cntr=.3,.1

Type RM Length L Ch R = 1 ,900.00  ,50,50,50
BEGIN DESCRIPTION:
18
END DESCRIPTION:
#Sta/Elev= 10
    -5.4   13.51    -5.4   11.51    -2.4   11.51       0   10.01     1.6    9.01
     2.4    9.01     3.9   10.01     6.4   10.01     7.9    8.91    17.9    8.91
#Mann= 3 , 0 , 0
    -5.4    .033       0       0    .033       0     3.9    .033       0
#XS Ineff= 2 , 0
               0   10.01     3.9           10.01
Permanent Ineff=
       F       F
Bank Sta=0,3.9
XS Rating Curve= 0
Exp/Cntr=.3,.1

Type RM Length L Ch R = 1 ,850.00  ,17,17,17
BEGIN DESCRIPTION:
17
END DESCRIPTION:
#Sta/Elev= 7
   -13.4   12.77    -3.4   12.77       0   10.87     2.1    8.77       3    8.77
     6.2   10.37    16.2   10.37
#Mann= 3 , 0 , 0
   -13.4    .033       0       0    .033       0     6.2    .033       0
#XS Ineff= 2 , 0
               0   10.87     6.2           10.37
Permanent Ineff=
       F       F
Bank Sta=0,6.2
XS Rating Curve= 0
Exp/Cntr=.3,.1

Type RM Length L Ch R = 1 ,833.00  ,33,33,33
BEGIN DESCRIPTION:
16.033
END DESCRIPTION:
#Sta/Elev= 7
   -13.4   12.49    -3.4   12.49       0   10.59     2.1    8.49       3    8.49
     6.2   10.59    16.2   10.59
#Mann= 3 , 0 , 0
   -13.4    .033       0       0    .033       0     6.2    .033       0
#XS Ineff= 2 , 0
               0   10.59     6.2           10.59
Permanent Ineff=
       F       F
Bank Sta=0,6.2
XS Rating Curve= 0
Exp/Cntr=.3,.1

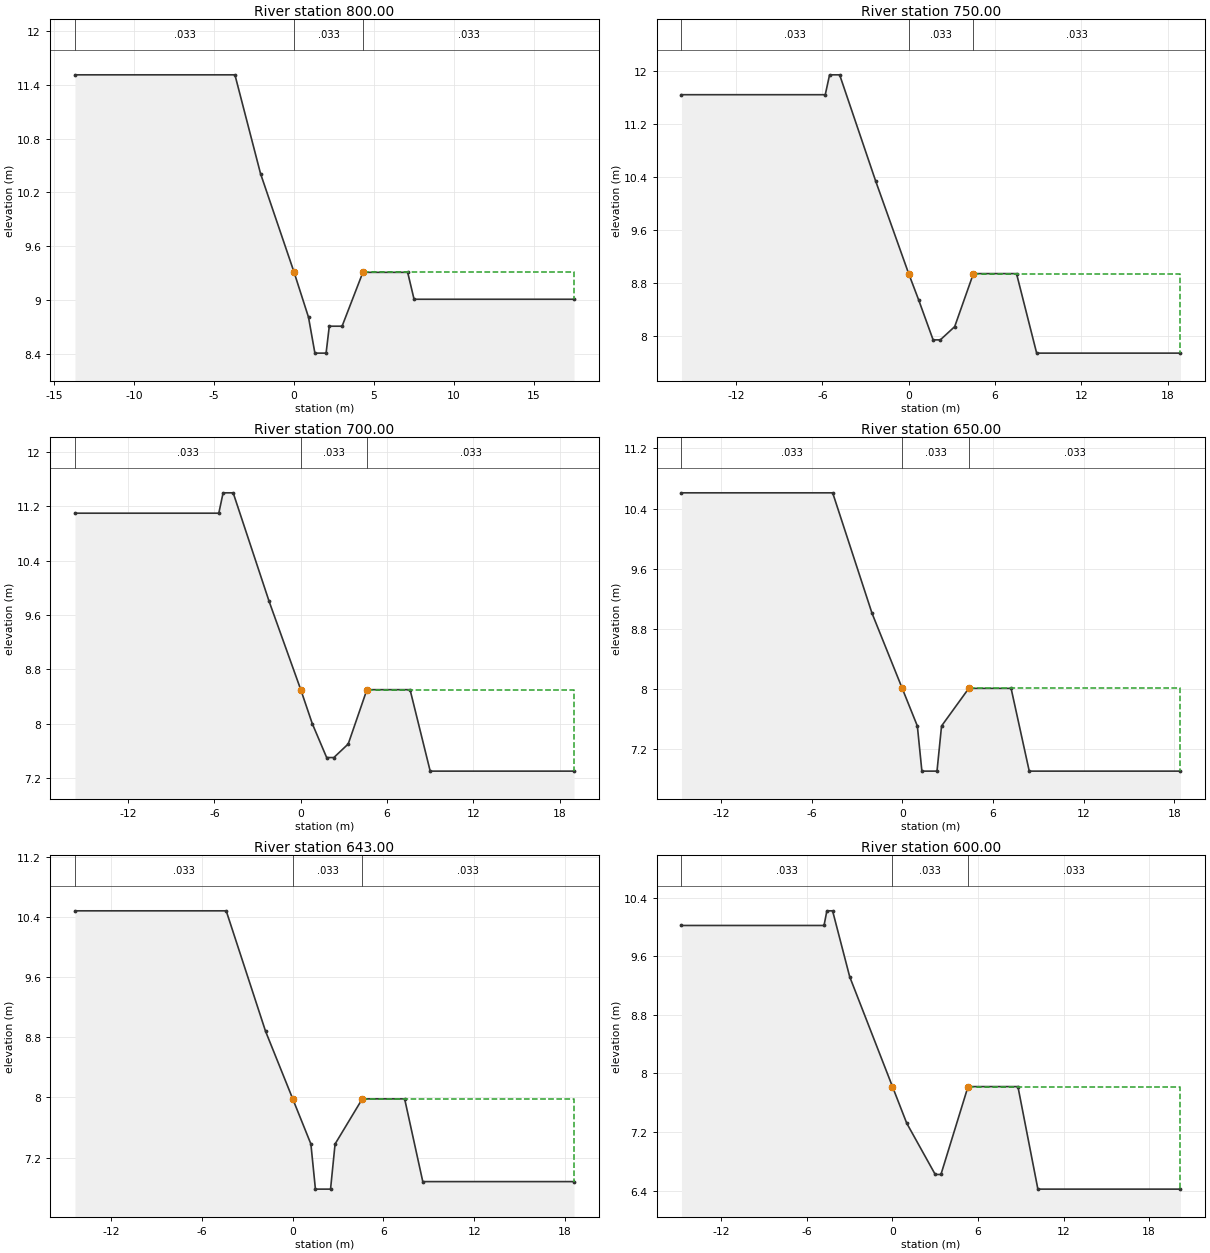
Type RM Length L Ch R = 1 ,800.00  ,50,50,50
BEGIN DESCRIPTION:
16
END DESCRIPTION:
#Sta/Elev= 13
   -13.7   11.51    -3.7   11.51    -2.1   10.41       0    9.31      .9    8.81
     1.3    8.41       2    8.41     2.2    8.71       3    8.71     4.3    9.31
     7.1    9.31     7.5    9.01    17.5    9.01
#Mann= 3 , 0 , 0
   -13.7    .033       0       0    .033       0     4.3    .033       0
#XS Ineff= 2 , 0
               0    9.31     4.3            9.31
Permanent Ineff=
       F       F
Bank Sta=0,4.3
XS Rating Curve= 0
Exp/Cntr=.3,.1

Type RM Length L Ch R = 1 ,750.00  ,50,50,50
BEGIN DESCRIPTION:
15
END DESCRIPTION:
#Sta/Elev= 14
   -15.8   11.64    -5.8   11.64    -5.5   11.94    -4.8   11.94    -2.3   10.34
       0    8.94      .7    8.54     1.7    7.94     2.2    7.94     3.2    8.14
     4.5    8.94     7.5    8.94     8.9    7.74    18.9    7.74
#Mann= 3 , 0 , 0
   -15.8    .033       0       0    .033       0     4.5    .033       0
#XS Ineff= 2 , 0
               0    8.94     4.5            8.94
Permanent Ineff=
       F       F
Bank Sta=0,4.5
XS Rating Curve= 0
Exp/Cntr=.3,.1

Type RM Length L Ch R = 1 ,700.00  ,50,50,50
BEGIN DESCRIPTION:
14
END DESCRIPTION:
#Sta/Elev= 14
   -15.7    11.1    -5.7    11.1    -5.4    11.4    -4.7    11.4    -2.2     9.8
       0     8.5      .8       8     1.8     7.5     2.3     7.5     3.3     7.7
     4.6     8.5     7.6     8.5       9     7.3      19     7.3
#Mann= 3 , 0 , 0
   -15.7    .033       0       0    .033       0     4.6    .033       0
#XS Ineff= 2 , 0
               0     8.5     4.6             8.5
Permanent Ineff=
       F       F
Bank Sta=0,4.6
XS Rating Curve= 0
Exp/Cntr=.3,.1

Type RM Length L Ch R = 1 ,650.00  ,7,7,7
BEGIN DESCRIPTION:
13
END DESCRIPTION:
#Sta/Elev= 12
   -14.6   10.61    -4.6   10.61      -2    9.01       0    8.01       1    7.51
     1.3    6.91     2.3    6.91     2.6    7.51     4.4    8.01     7.2    8.01
     8.4    6.91    18.4    6.91
#Mann= 3 , 0 , 0
   -14.6    .033       0       0    .033       0     4.4    .033       0
#XS Ineff= 2 , 0
               0    8.01     4.4            8.01
Permanent Ineff=
       F       F
Bank Sta=0,4.4
XS Rating Curve= 0
Exp/Cntr=.3,.1

Type RM Length L Ch R = 1 ,643.00  ,43,43,43
BEGIN DESCRIPTION:
12.043
END DESCRIPTION:
#Sta/Elev= 12
   -14.4   10.48    -4.4   10.48    -1.8    8.88       0    7.98     1.2    7.38
     1.5    6.78     2.5    6.78     2.8    7.38     4.6    7.98     7.4    7.98
     8.6    6.88    18.6    6.88
#Mann= 3 , 0 , 0
   -14.4    .033       0       0    .033       0     4.6    .033       0
#XS Ineff= 2 , 0
               0    7.98     4.6            7.98
Permanent Ineff=
       F       F
Bank Sta=0,4.6
XS Rating Curve= 0
Exp/Cntr=.3,.1

Type RM Length L Ch R = 1 ,600.00  ,50,50,50
BEGIN DESCRIPTION:
12
END DESCRIPTION:
#Sta/Elev= 13
   -14.8   10.02    -4.8   10.02    -4.6   10.22    -4.2   10.22      -3    9.32
       0    7.82       1    7.32       3    6.62     3.4    6.62     5.3    7.82
     8.8    7.82    10.2    6.42    20.2    6.42
#Mann= 3 , 0 , 0
   -14.8    .033       0       0    .033       0     5.3    .033       0
#XS Ineff= 2 , 0
               0    7.82     5.3            7.82
Permanent Ineff=
       F       F
Bank Sta=0,5.3
XS Rating Curve= 0
Exp/Cntr=.3,.1

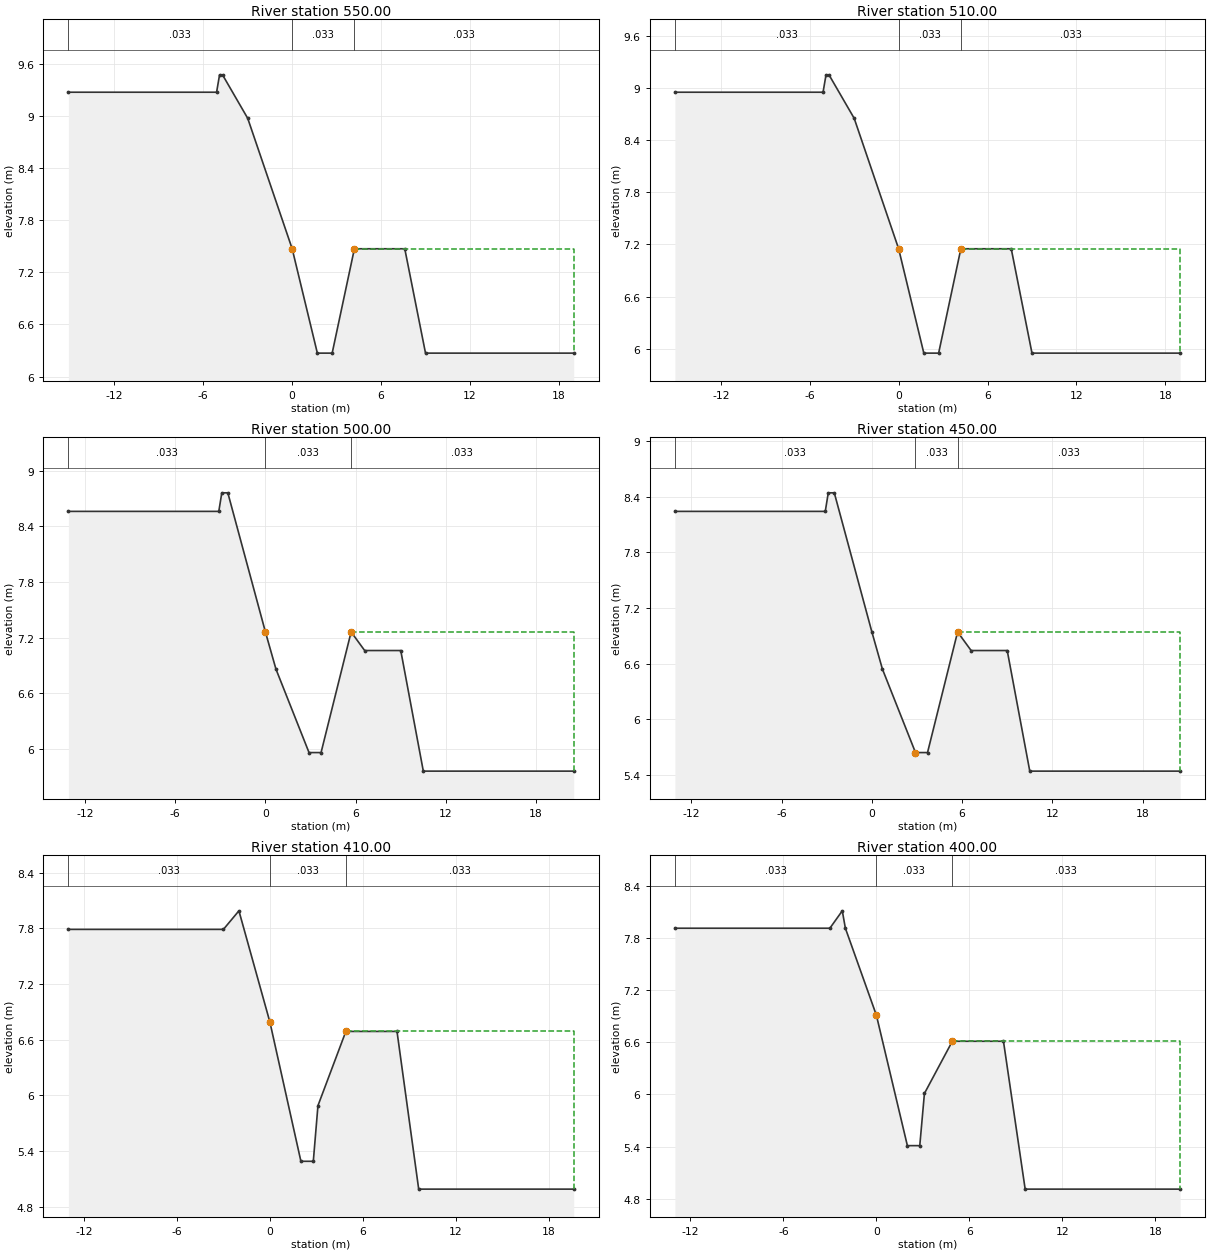
Type RM Length L Ch R = 1 ,550.00  ,40,40,40
BEGIN DESCRIPTION:
11
END DESCRIPTION:
#Sta/Elev= 12
   -15.1    9.27    -5.1    9.27    -4.9    9.47    -4.7    9.47      -3    8.97
       0    7.47     1.7    6.27     2.7    6.27     4.2    7.47     7.6    7.47
       9    6.27      19    6.27
#Mann= 3 , 0 , 0
   -15.1    .033       0       0    .033       0     4.2    .033       0
#XS Ineff= 2 , 0
               0    7.47     4.2            7.47
Permanent Ineff=
       F       F
Bank Sta=0,4.2
XS Rating Curve= 0
Exp/Cntr=.3,.1

Type RM Length L Ch R = 1 ,510.00  ,10,10,10
BEGIN DESCRIPTION:
10.01
END DESCRIPTION:
#Sta/Elev= 12
   -15.1    8.95    -5.1    8.95    -4.9    9.15    -4.7    9.15      -3    8.65
       0    7.15     1.7    5.95     2.7    5.95     4.2    7.15     7.6    7.15
       9    5.95      19    5.95
#Mann= 3 , 0 , 0
   -15.1    .033       0       0    .033       0     4.2    .033       0
#XS Ineff= 2 , 0
               0    7.15     4.2            7.15
Permanent Ineff=
       F       F
Bank Sta=0,4.2
XS Rating Curve= 0
Exp/Cntr=.3,.1

Type RM Length L Ch R = 1 ,500.00  ,50,50,50
BEGIN DESCRIPTION:
10
END DESCRIPTION:
#Sta/Elev= 13
   -13.1    8.56    -3.1    8.56    -2.9    8.76    -2.5    8.76       0    7.26
      .7    6.86     2.9    5.96     3.7    5.96     5.7    7.26     6.6    7.06
       9    7.06    10.5    5.76    20.5    5.76
#Mann= 3 , 0 , 0
   -13.1    .033       0       0    .033       0     5.7    .033       0
#XS Ineff= 2 , 0
               0    7.26     5.7            7.26
Permanent Ineff=
       F       F
Bank Sta=0,5.7
XS Rating Curve= 0
Exp/Cntr=.3,.1

Type RM Length L Ch R = 1 ,450.00  ,40,40,40
BEGIN DESCRIPTION:
9
END DESCRIPTION:
#Sta/Elev= 13
   -13.1    8.24    -3.1    8.24    -2.9    8.44    -2.5    8.44       0    6.94
      .7    6.54     2.9    5.64     3.7    5.64     5.7    6.94     6.6    6.74
       9    6.74    10.5    5.44    20.5    5.44
#Mann= 3 , 0 , 0
   -13.1    .033       0     2.9    .033       0     5.7    .033       0
#XS Ineff= 2 , 0
             2.9    5.64     5.7            6.94
Permanent Ineff=
       F       F
Bank Sta=2.9,5.7
XS Rating Curve= 0
Exp/Cntr=.3,.1

Type RM Length L Ch R = 1 ,410.00  ,10,10,10
BEGIN DESCRIPTION:
8.01
END DESCRIPTION:
#Sta/Elev= 11
     -13    7.79      -3    7.79      -2    7.99       0    6.79       2    5.29
     2.8    5.29     3.1    5.89     4.9    6.69     8.2    6.69     9.6    4.99
    19.6    4.99
#Mann= 3 , 0 , 0
     -13    .033       0       0    .033       0     4.9    .033       0
#XS Ineff= 2 , 0
               0    6.79     4.9            6.69
Permanent Ineff=
       F       F
Bank Sta=0,4.9
XS Rating Curve= 0
Exp/Cntr=.3,.1

Type RM Length L Ch R = 1 ,400.00  ,2,2,2
BEGIN DESCRIPTION:
8
END DESCRIPTION:
#Sta/Elev= 12
     -13    7.91      -3    7.91    -2.2    8.11      -2    7.91       0    6.91
       2    5.41     2.8    5.41     3.1    6.01     4.9    6.61     8.2    6.61
     9.6    4.91    19.6    4.91
#Mann= 3 , 0 , 0
     -13    .033       0       0    .033       0     4.9    .033       0
#XS Ineff= 2 , 0
               0    6.91     4.9            6.61
Permanent Ineff=
       F       F
Bank Sta=0,4.9
XS Rating Curve= 0
Exp/Cntr=.3,.1

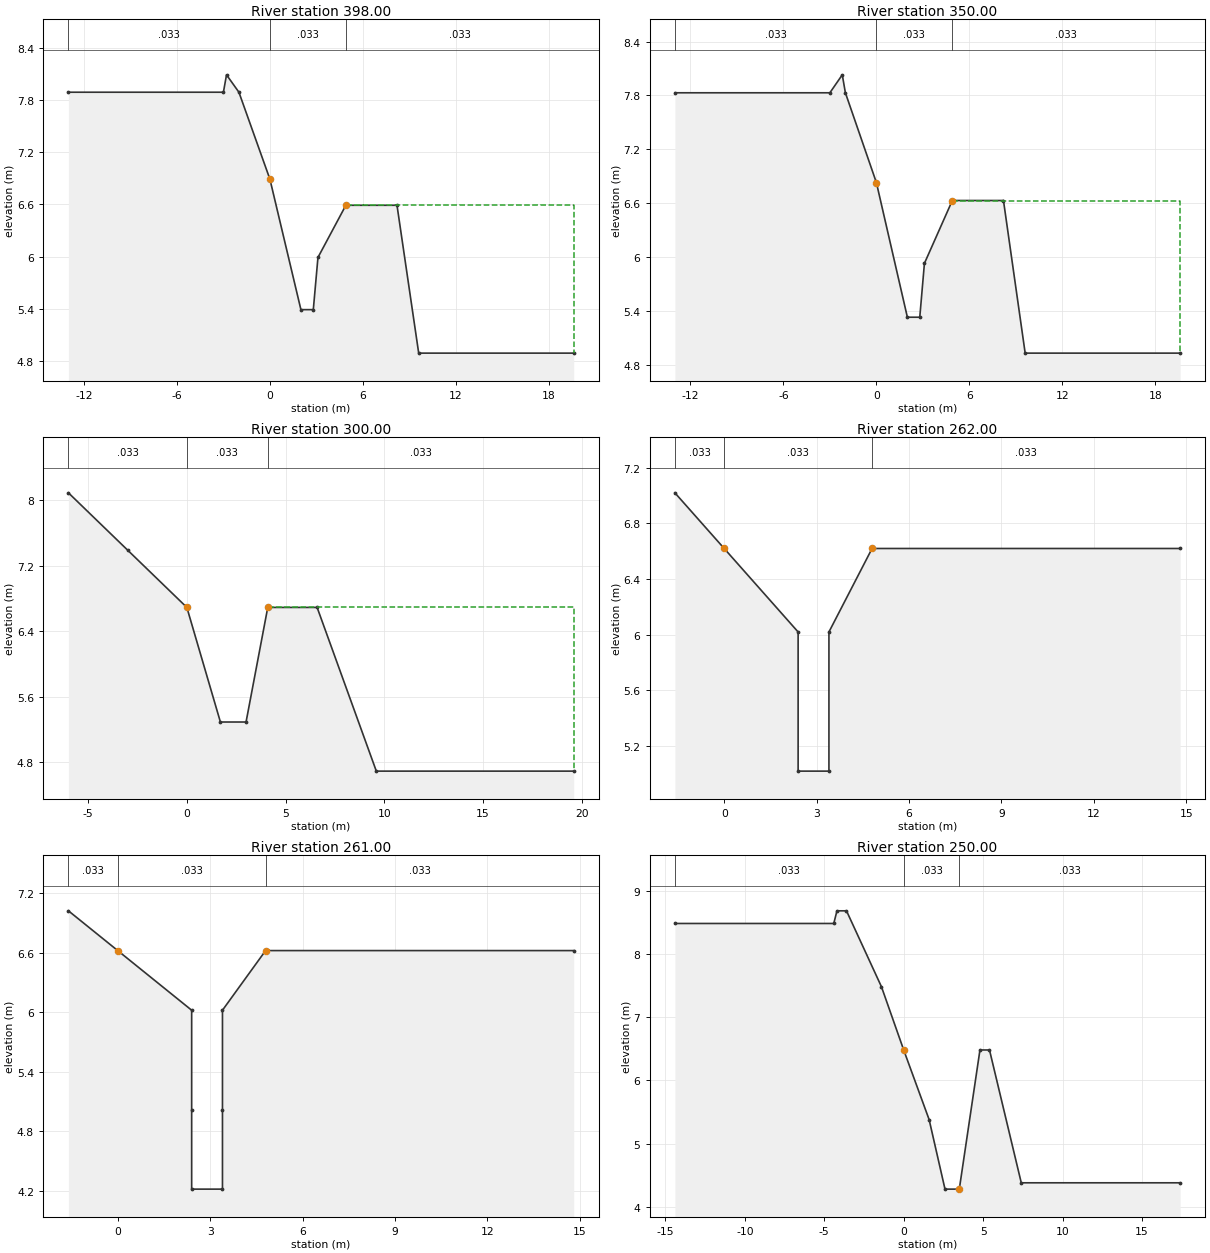
Type RM Length L Ch R = 1 ,398.00  ,48,48,48
BEGIN DESCRIPTION:
7.048
END DESCRIPTION:
#Sta/Elev= 12
     -13    7.89      -3    7.89    -2.8    8.09      -2    7.89       0    6.89
       2    5.39     2.8    5.39     3.1    5.99     4.9    6.59     8.2    6.59
     9.6    4.89    19.6    4.89
#Mann= 3 , 0 , 0
     -13    .033       0       0    .033       0     4.9    .033       0
#XS Ineff= 2 , 0
               0    6.89     4.9            6.59
Permanent Ineff=
       F       F
Bank Sta=0,4.9
XS Rating Curve= 0
Exp/Cntr=.3,.1

Type RM Length L Ch R = 1 ,350.00  ,50,50,50
BEGIN DESCRIPTION:
7
END DESCRIPTION:
#Sta/Elev= 12
     -13    7.83      -3    7.83    -2.2    8.03      -2    7.83       0    6.83
       2    5.33     2.8    5.33     3.1    5.93     4.9    6.63     8.2    6.63
     9.6    4.93    19.6    4.93
#Mann= 3 , 0 , 0
     -13    .033       0       0    .033       0     4.9    .033       0
#XS Ineff= 2 , 0
               0    6.83     4.9            6.63
Permanent Ineff=
       F       F
Bank Sta=0,4.9
XS Rating Curve= 0
Exp/Cntr=.3,.1

Type RM Length L Ch R = 1 ,300.00  ,38,38,38
BEGIN DESCRIPTION:
6
END DESCRIPTION:
#Sta/Elev= 9
      -6    8.09      -3    7.39       0    6.69     1.7    5.29       3    5.29
     4.1    6.69     6.6    6.69     9.6    4.69    19.6    4.69
#Mann= 3 , 0 , 0
      -6    .033       0       0    .033       0     4.1    .033       0
#XS Ineff= 2 , 0
               0    6.69     4.1            6.69
Permanent Ineff=
       F       F
Bank Sta=0,4.1
XS Rating Curve= 0
Exp/Cntr=.3,.1

Type RM Length L Ch R = 1 ,262.00  ,1,1,1
BEGIN DESCRIPTION:
5.012
END DESCRIPTION:
#Sta/Elev= 8
    -1.6    7.02       0    6.62     2.4    6.02     2.4    5.02     3.4    5.02
     3.4    6.02     4.8    6.62    14.8    6.62
#Mann= 3 , 0 , 0
    -1.6    .033       0       0    .033       0     4.8    .033       0
#XS Ineff= 2 , 0
               0    6.62     4.8            6.62
Permanent Ineff=
       F       F
Bank Sta=0,4.8
XS Rating Curve= 0
Exp/Cntr=.3,.1

Type RM Length L Ch R = 1 ,261.00  ,11,11,11
BEGIN DESCRIPTION:
5.011
END DESCRIPTION:
#Sta/Elev= 10
    -1.6    7.02       0    6.62     2.4    6.02     2.4    5.02     2.4    4.22
     3.4    4.22     3.4    5.02     3.4    6.02     4.8    6.62    14.8    6.62
#Mann= 3 , 0 , 0
    -1.6    .033       0       0    .033       0     4.8    .033       0
#XS Ineff= 2 , 0
               0    6.62     4.8            6.62
Permanent Ineff=
       F       F
Bank Sta=0,4.8
XS Rating Curve= 0
Exp/Cntr=.3,.1

Type RM Length L Ch R = 1 ,250.00  ,50,50,50
BEGIN DESCRIPTION:
5
END DESCRIPTION:
#Sta/Elev= 13
   -14.4    8.48    -4.4    8.48    -4.2    8.68    -3.6    8.68    -1.4    7.48
       0    6.48     1.6    5.38     2.6    4.28     3.5    4.28     4.8    6.48
     5.4    6.48     7.4    4.38    17.4    4.38
#Mann= 3 , 0 , 0
   -14.4    .033       0       0    .033       0     3.5    .033       0
#XS Ineff= 2 , 0
               0    6.48     3.5            4.28
Permanent Ineff=
       F       F
Bank Sta=0,3.5
XS Rating Curve= 0
Exp/Cntr=.3,.1

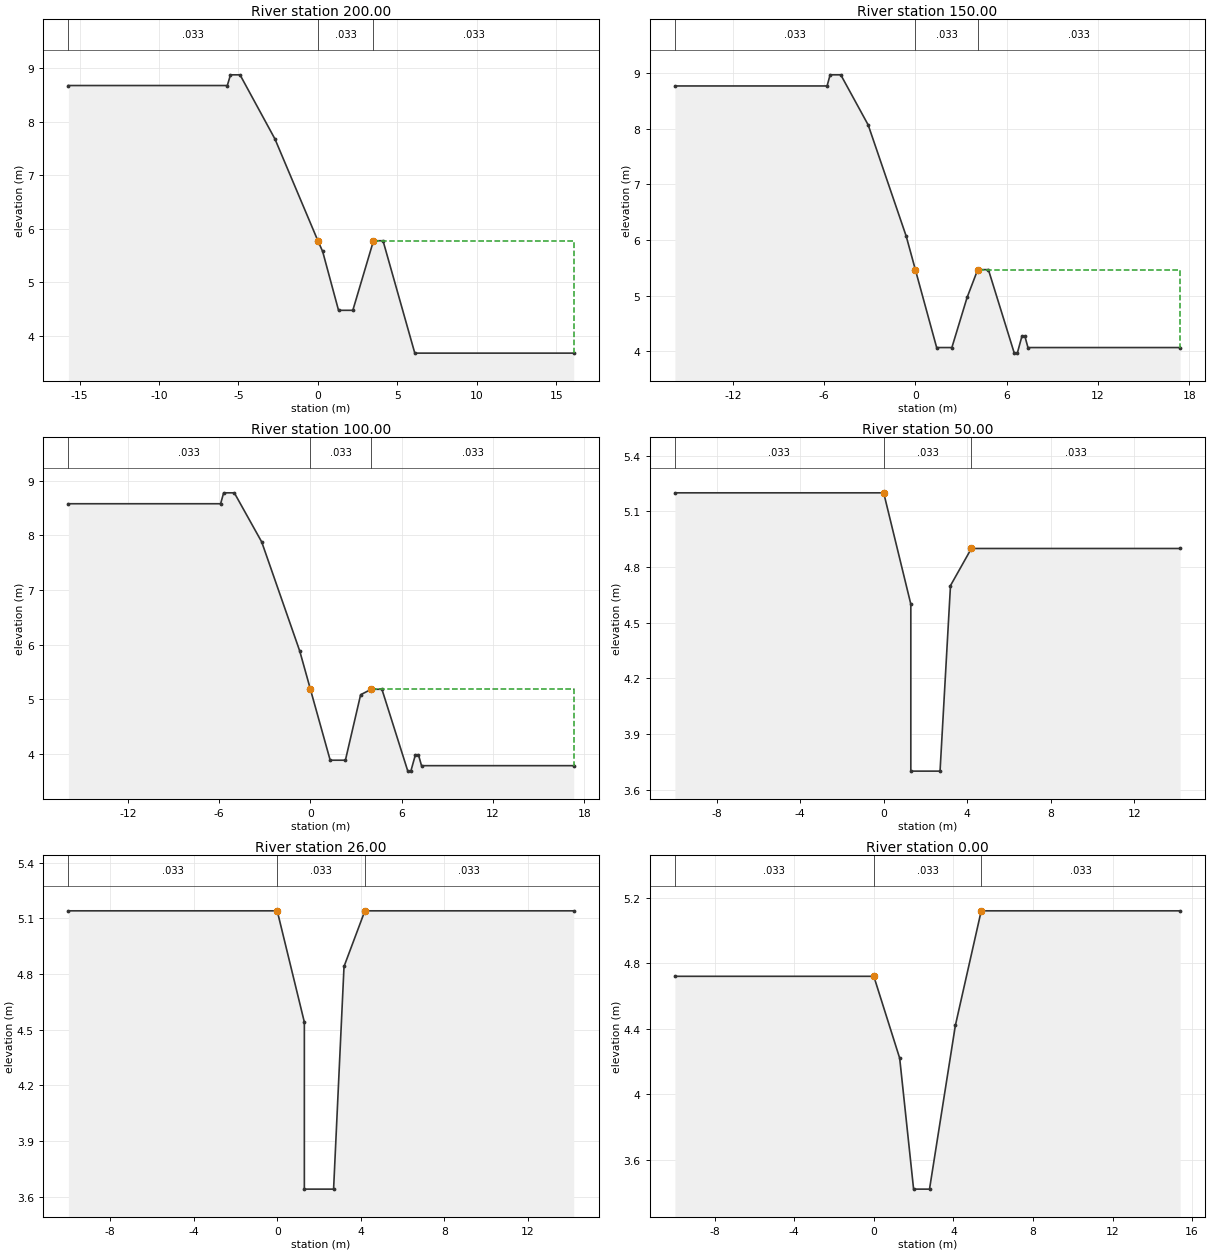
Type RM Length L Ch R = 1 ,200.00  ,50,50,50
BEGIN DESCRIPTION:
4
END DESCRIPTION:
#Sta/Elev= 13
   -15.7    8.68    -5.7    8.68    -5.5    8.88    -4.9    8.88    -2.7    7.68
       0    5.78      .3    5.58     1.3    4.48     2.2    4.48     3.5    5.78
     4.1    5.78     6.1    3.68    16.1    3.68
#Mann= 3 , 0 , 0
   -15.7    .033       0       0    .033       0     3.5    .033       0
#XS Ineff= 2 , 0
               0    5.78     3.5            5.78
Permanent Ineff=
       F       F
Bank Sta=0,3.5
XS Rating Curve= 0
Exp/Cntr=.3,.1

Type RM Length L Ch R = 1 ,150.00  ,50,50,50
BEGIN DESCRIPTION:
3
END DESCRIPTION:
#Sta/Elev= 18
   -15.8    8.77    -5.8    8.77    -5.6    8.97    -4.9    8.97    -3.1    8.07
     -.6    6.07       0    5.47     1.4    4.07     2.4    4.07     3.4    4.97
     4.1    5.47     4.8    5.47     6.5    3.97     6.7    3.97       7    4.27
     7.2    4.27     7.4    4.07    17.4    4.07
#Mann= 3 , 0 , 0
   -15.8    .033       0       0    .033       0     4.1    .033       0
#XS Ineff= 2 , 0
               0    5.47     4.1            5.47
Permanent Ineff=
       F       F
Bank Sta=0,4.1
XS Rating Curve= 0
Exp/Cntr=.3,.1

Type RM Length L Ch R = 1 ,100.00  ,50,50,50
BEGIN DESCRIPTION:
2
END DESCRIPTION:
#Sta/Elev= 18
   -15.9    8.58    -5.9    8.58    -5.7    8.78      -5    8.78    -3.2    7.88
     -.7    5.88       0    5.18     1.3    3.88     2.3    3.88     3.3    5.08
       4    5.18     4.7    5.18     6.4    3.68     6.6    3.68     6.9    3.98
     7.1    3.98     7.3    3.78    17.3    3.78
#Mann= 3 , 0 , 0
   -15.9    .033       0       0    .033       0       4    .033       0
#XS Ineff= 2 , 0
               0    5.18       4            5.18
Permanent Ineff=
       F       F
Bank Sta=0,4
XS Rating Curve= 0
Exp/Cntr=.3,.1

Type RM Length L Ch R = 1 ,50.00   ,24,24,24
BEGIN DESCRIPTION:
1
END DESCRIPTION:
#Sta/Elev= 8
     -10     5.2       0     5.2     1.3     4.6     1.3     3.7     2.7     3.7
     3.2     4.7     4.2     4.9    14.2     4.9
#Mann= 3 , 0 , 0
     -10    .033       0       0    .033       0     4.2    .033       0
#XS Ineff= 2 , 0
               0     5.2     4.2             4.9
Permanent Ineff=
       F       F
Bank Sta=0,4.2
XS Rating Curve= 0
Exp/Cntr=.3,.1

Type RM Length L Ch R = 1 ,26.00   ,26,26,26
BEGIN DESCRIPTION:
0.026
END DESCRIPTION:
#Sta/Elev= 8
     -10    5.14       0    5.14     1.3    4.54     1.3    3.64     2.7    3.64
     3.2    4.84     4.2    5.14    14.2    5.14
#Mann= 3 , 0 , 0
     -10    .033       0       0    .033       0     4.2    .033       0
#XS Ineff= 2 , 0
               0    5.14     4.2            5.14
Permanent Ineff=
       F       F
Bank Sta=0,4.2
XS Rating Curve= 0
Exp/Cntr=.3,.1

Type RM Length L Ch R = 1 ,0.00    ,0,0,0
BEGIN DESCRIPTION:
0
END DESCRIPTION:
#Sta/Elev= 8
     -10    4.72       0    4.72     1.3    4.22       2    3.42     2.8    3.42
     4.1    4.42     5.4    5.12    15.4    5.12
#Mann= 3 , 0 , 0
     -10    .033       0       0    .033       0     5.4    .033       0
#XS Ineff= 2 , 0
               0    4.72     5.4            5.12
Permanent Ineff=
       F       F
Bank Sta=0,5.4
XS Rating Curve= 0
Exp/Cntr=.3,.1

Chan Stop Cuts=-1