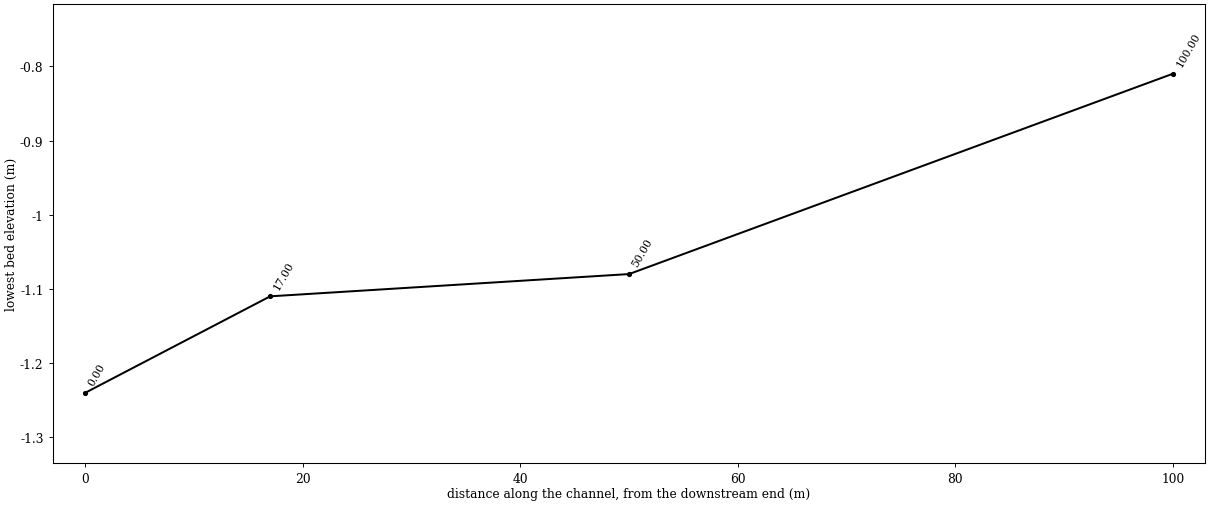
HEC-RAS study SSC.prj: SSC

--- SSC.g01 (geometry) --- (continued)

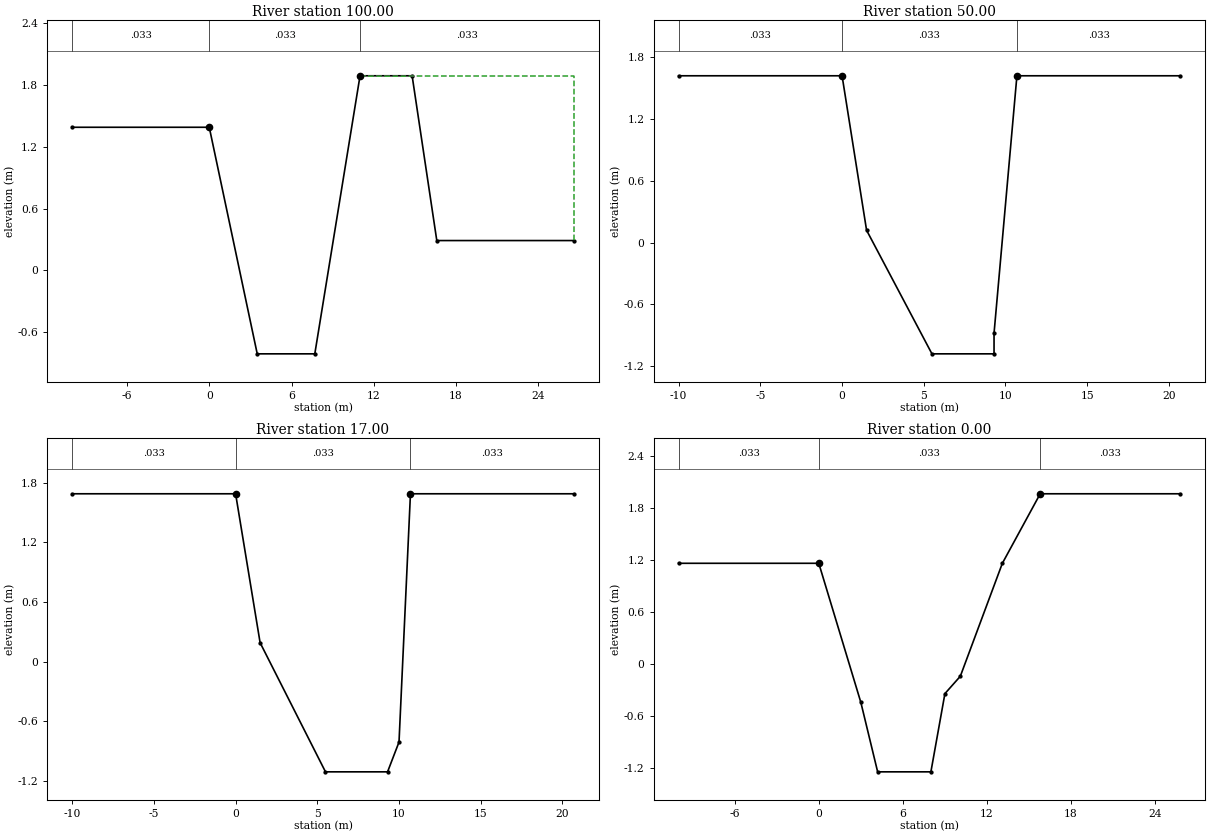
Type RM Length L Ch R = 1 ,100.00  ,50,50,50
BEGIN DESCRIPTION:
2
END DESCRIPTION:
#Sta/Elev= 8
     -10    1.39       0    1.39     3.5    -.81     7.7    -.81      11    1.89
    14.8    1.89    16.6     .29    26.6     .29
#Mann= 3 , 0 , 0
     -10    .033       0       0    .033       0      11    .033       0
#XS Ineff= 2 , 0
               0    1.39      11            1.89
Permanent Ineff=
       F       F
Bank Sta=0,11
XS Rating Curve= 0
Exp/Cntr=.3,.1

Type RM Length L Ch R = 1 ,50.00   ,33,33,33
BEGIN DESCRIPTION:
1
END DESCRIPTION:
#Sta/Elev= 8
     -10    1.62       0    1.62     1.5     .12     5.5   -1.08     9.3   -1.08
     9.3    -.88    10.7    1.62    20.7    1.62
#Mann= 3 , 0 , 0
     -10    .033       0       0    .033       0    10.7    .033       0
#XS Ineff= 2 , 0
               0    1.62    10.7            1.62
Permanent Ineff=
       F       F
Bank Sta=0,10.7
XS Rating Curve= 0
Exp/Cntr=.3,.1

Type RM Length L Ch R = 1 ,17.00   ,17,17,17
BEGIN DESCRIPTION:
0.017
END DESCRIPTION:
#Sta/Elev= 8
     -10    1.69       0    1.69     1.5     .19     5.5   -1.11     9.3   -1.11
      10    -.81    10.7    1.69    20.7    1.69
#Mann= 3 , 0 , 0
     -10    .033       0       0    .033       0    10.7    .033       0
#XS Ineff= 2 , 0
               0    1.69    10.7            1.69
Permanent Ineff=
       F       F
Bank Sta=0,10.7
XS Rating Curve= 0
Exp/Cntr=.3,.1

Type RM Length L Ch R = 1 ,0.00    ,0,0,0
BEGIN DESCRIPTION:
0
END DESCRIPTION:
#Sta/Elev= 10
     -10    1.16       0    1.16       3    -.44     4.2   -1.24       8   -1.24
       9    -.34    10.1    -.14    13.1    1.16    15.8    1.96    25.8    1.96
#Mann= 3 , 0 , 0
     -10    .033       0       0    .033       0    15.8    .033       0
#XS Ineff= 2 , 0
               0    1.16    15.8            1.96
Permanent Ineff=
       F       F
Bank Sta=0,15.8
XS Rating Curve= 0
Exp/Cntr=.3,.1

Chan Stop Cuts=-1