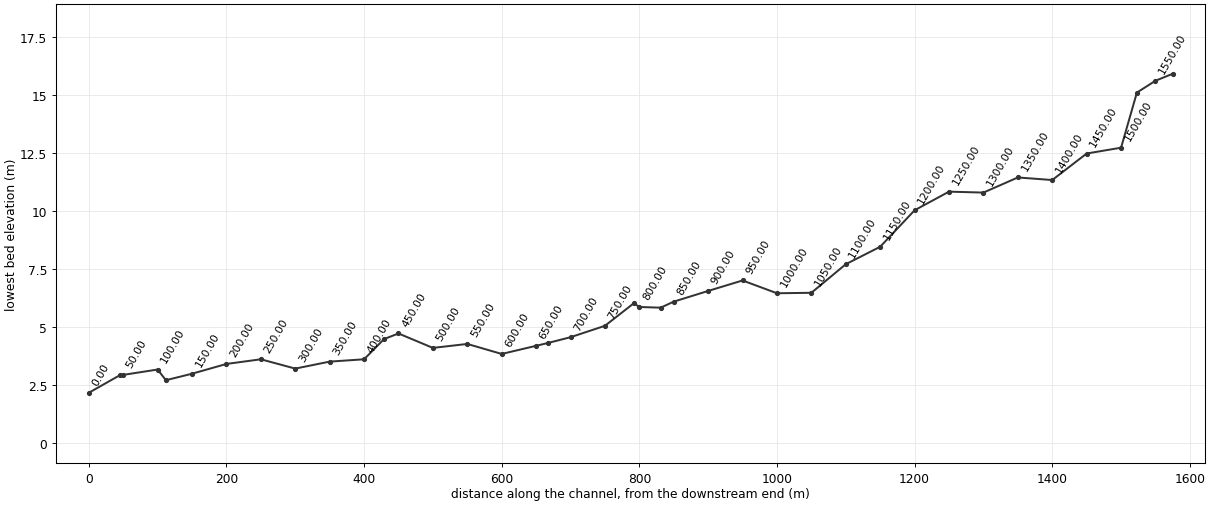
--- SIN.prj (project) ---

Proj Title=SIN
Current Plan=p01
Default Exp/Contr=.3,.1
SI Units
Geom File=g01
Flow File=f01
Plan File=p01
Y Axis Title=Elevation
X Axis Title(PF)=Main Channel Distance
X Axis Title(XS)=Station
BEGIN DESCRIPTION:
           BACK WATER COMPUTATION
      APPLICATION OF HEC-2 BY Samju Construction Engineering
      SINDAEMAL-STREEM : 30 YR
END DESCRIPTION:
DSS Export Rating Curves= 0
DSS Export Rating Curve Sorted= 0
DSS Export Volume Flow Curves= 0
DXF OffsetX= 0
DXF OffsetY= 0
DXF ScaleX= 1
DXF ScaleY= 10

--- SIN.p01 (plan) ---

Plan Title=Imported Plan 01
Version=Version 3.0.1  Mar 2001
Short Identifier=Imported Pla
Geom File=g01
Flow File=f01
Subcritical Flow
K Sum by GR= 0
Std Step Tol= 0.003
Critical Tol= 0.003
Num of Std Step Trials= 20
Max Error Tol= 0.1
Flow Tol Ratio= 0.001
Split Flow NTrial= 30
Split Flow Tol= 0.02
Split Flow Ratio= 0.02
Log Output Level= 0
Friction Slope Method= 1
Unsteady Friction Slope Method= 2
Parabolic Critical Depth
Global Vel Dist= 0 , 0 , 0
Global Log Level= 0
CheckData=True
Encroach Param=-1 ,0,0, 0
Computation Interval=1HOUR
Output Interval=1HOUR
Run HTab= 0
Run UNet= 0
Run PostProcess= 0
UNET Theta= 1
UNET ZTol= 0.02
UNET ZSATol= 0.1
UNET MxIter= 20
UNET MaxInSteps= 20
UNET DtIC= 0
UNET DtMin= 0
UNET MaxCRTS= 20
UNET WFStab= 2
UNET SFStab= 1
UNET WFX= 1
UNET SFX= 1
UNET Convert EG Bridges=-1
UNET Use Existing IB Tables=-1
Instantaneous Interval=1HOUR
Write IC File= 0
Write Velocity= 0
Write Detailed= 0

--- SIN.f01 (steady flow) ---

Flow Title=Imported Flow 01
Version=Version 3.0.1  Mar 2001
Number of Profiles= 5
Profile Names=10YR,20YR,30YR,50YR,80YR
River Rch & RM=RIVER-1,Reach-1         ,31.025
   12.85   14.15   14.91   15.87   16.75
River Rch & RM=RIVER-1,Reach-1         ,15
   18.68   20.58   21.69    23.1   24.39
River Rch & RM=SINDAEMAL,SINDAEMAL       ,1575.00
   12.85   14.15   14.91   15.87   16.75
River Rch & RM=SINDAEMAL,SINDAEMAL       ,750.00
   18.68   20.58   21.69    23.1   24.39
Boundary for River Rch & Prof#=SINDAEMAL,SINDAEMAL       , 1
Up Type= 0
Dn Type= 3
Dn Slope=.014
Boundary for River Rch & Prof#=SINDAEMAL,SINDAEMAL       , 2
Up Type= 0
Dn Type= 3
Dn Slope=.014
Boundary for River Rch & Prof#=SINDAEMAL,SINDAEMAL       , 3
Up Type= 0
Dn Type= 3
Dn Slope=.014
Boundary for River Rch & Prof#=SINDAEMAL,SINDAEMAL       , 4
Up Type= 0
Dn Type= 3
Dn Slope=.014
Boundary for River Rch & Prof#=SINDAEMAL,SINDAEMAL       , 5
Up Type= 0
Dn Type= 3
Dn Slope=.014
DSS Import GetInterval= 0
DSS Import GetPeak= 0
DSS Import FillOption= 0

--- SIN.g01 (geometry) ---

Geom Title=Imported Geom 01
Version=Version 3.0.1  Mar 2001

River Reach=SINDAEMAL       ,SINDAEMAL
Reach XY= 2
              .5             .95              .5             .05

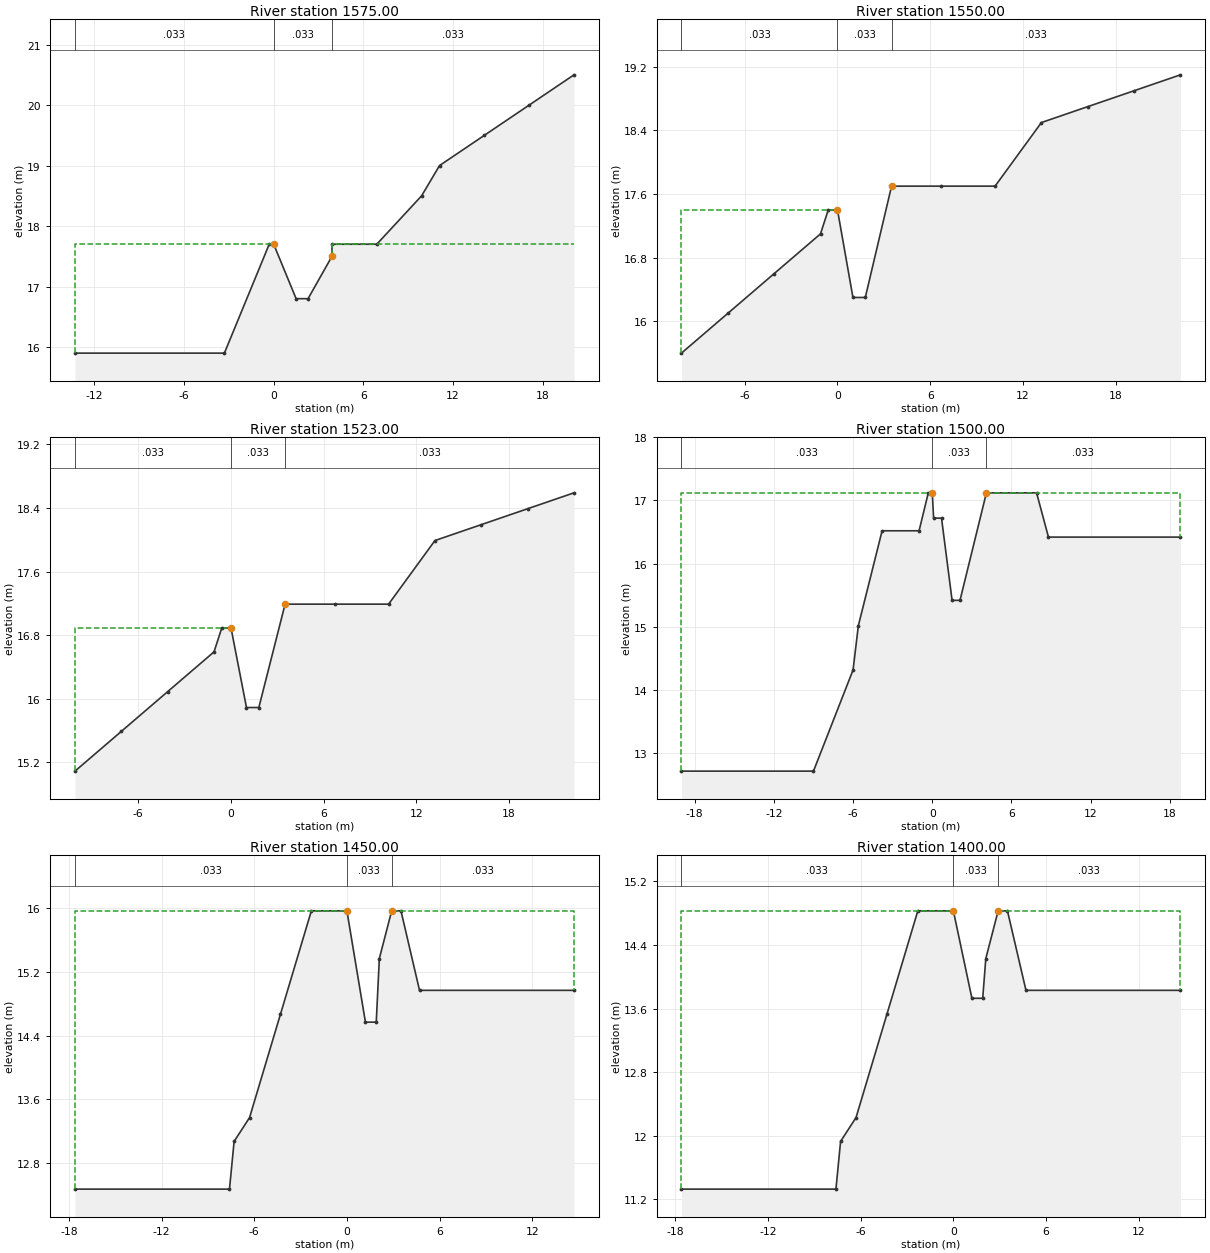
Type RM Length L Ch R = 1 ,1575.00 ,25,25,25
BEGIN DESCRIPTION:
31.025
END DESCRIPTION:
#Sta/Elev= 14
   -13.3    15.9    -3.3    15.9     -.3    17.7       0    17.7     1.5    16.8
     2.3    16.8     3.9    17.5     3.9    17.7     6.9    17.7     9.9    18.5
    11.1      19    14.1    19.5    17.1      20    20.1    20.5
#Mann= 3 , 0 , 0
   -13.3    .033       0       0    .033       0     3.9    .033       0
#XS Ineff= 2 , 0
               0    17.7     3.9            17.7
Permanent Ineff=
       F       F
Bank Sta=0,3.9
XS Rating Curve= 0
Exp/Cntr=.3,.1

Type RM Length L Ch R = 1 ,1550.00 ,27,27,27
BEGIN DESCRIPTION:
31
END DESCRIPTION:
#Sta/Elev= 15
   -10.1    15.6    -7.1    16.1    -4.1    16.6    -1.1    17.1     -.6    17.4
       0    17.4       1    16.3     1.8    16.3     3.5    17.7     6.7    17.7
    10.2    17.7    13.2    18.5    16.2    18.7    19.2    18.9    22.2    19.1
#Mann= 3 , 0 , 0
   -10.1    .033       0       0    .033       0     3.5    .033       0
#XS Ineff= 2 , 0
               0    17.4     3.5            17.7
Permanent Ineff=
       F       F
Bank Sta=0,3.5
XS Rating Curve= 0
Exp/Cntr=.3,.1

Type RM Length L Ch R = 1 ,1523.00 ,23,23,23
BEGIN DESCRIPTION:
30.023
END DESCRIPTION:
#Sta/Elev= 15
   -10.1   15.09    -7.1   15.59    -4.1   16.09    -1.1   16.59     -.6   16.89
       0   16.89       1   15.89     1.8   15.89     3.5   17.19     6.7   17.19
    10.2   17.19    13.2   17.99    16.2   18.19    19.2   18.39    22.2   18.59
#Mann= 3 , 0 , 0
   -10.1    .033       0       0    .033       0     3.5    .033       0
#XS Ineff= 2 , 0
               0   16.89     3.5           17.19
Permanent Ineff=
       F       F
Bank Sta=0,3.5
XS Rating Curve= 0
Exp/Cntr=.3,.1

Type RM Length L Ch R = 1 ,1500.00 ,50,50,50
BEGIN DESCRIPTION:
30
END DESCRIPTION:
#Sta/Elev= 16
     -19   12.72      -9   12.72      -6   14.32    -5.6   15.02    -3.8   16.52
      -1   16.52     -.3   17.12       0   17.12      .1   16.72      .7   16.72
     1.5   15.42     2.1   15.42     4.1   17.12     7.9   17.12     8.8   16.42
    18.8   16.42
#Mann= 3 , 0 , 0
     -19    .033       0       0    .033       0     4.1    .033       0
#XS Ineff= 2 , 0
               0   17.12     4.1           17.12
Permanent Ineff=
       F       F
Bank Sta=0,4.1
XS Rating Curve= 0
Exp/Cntr=.3,.1

Type RM Length L Ch R = 1 ,1450.00 ,50,50,50
BEGIN DESCRIPTION:
29
END DESCRIPTION:
#Sta/Elev= 14
   -17.6   12.47    -7.6   12.47    -7.3   13.07    -6.3   13.37    -4.3   14.67
    -2.3   15.97       0   15.97     1.2   14.57     1.9   14.57     2.1   15.37
     2.9   15.97     3.5   15.97     4.7   14.97    14.7   14.97
#Mann= 3 , 0 , 0
   -17.6    .033       0       0    .033       0     2.9    .033       0
#XS Ineff= 2 , 0
               0   15.97     2.9           15.97
Permanent Ineff=
       F       F
Bank Sta=0,2.9
XS Rating Curve= 0
Exp/Cntr=.3,.1

Type RM Length L Ch R = 1 ,1400.00 ,50,50,50
BEGIN DESCRIPTION:
28
END DESCRIPTION:
#Sta/Elev= 14
   -17.6   11.33    -7.6   11.33    -7.3   11.93    -6.3   12.23    -4.3   13.53
    -2.3   14.83       0   14.83     1.2   13.73     1.9   13.73     2.1   14.23
     2.9   14.83     3.5   14.83     4.7   13.83    14.7   13.83
#Mann= 3 , 0 , 0
   -17.6    .033       0       0    .033       0     2.9    .033       0
#XS Ineff= 2 , 0
               0   14.83     2.9           14.83
Permanent Ineff=
       F       F
Bank Sta=0,2.9
XS Rating Curve= 0
Exp/Cntr=.3,.1

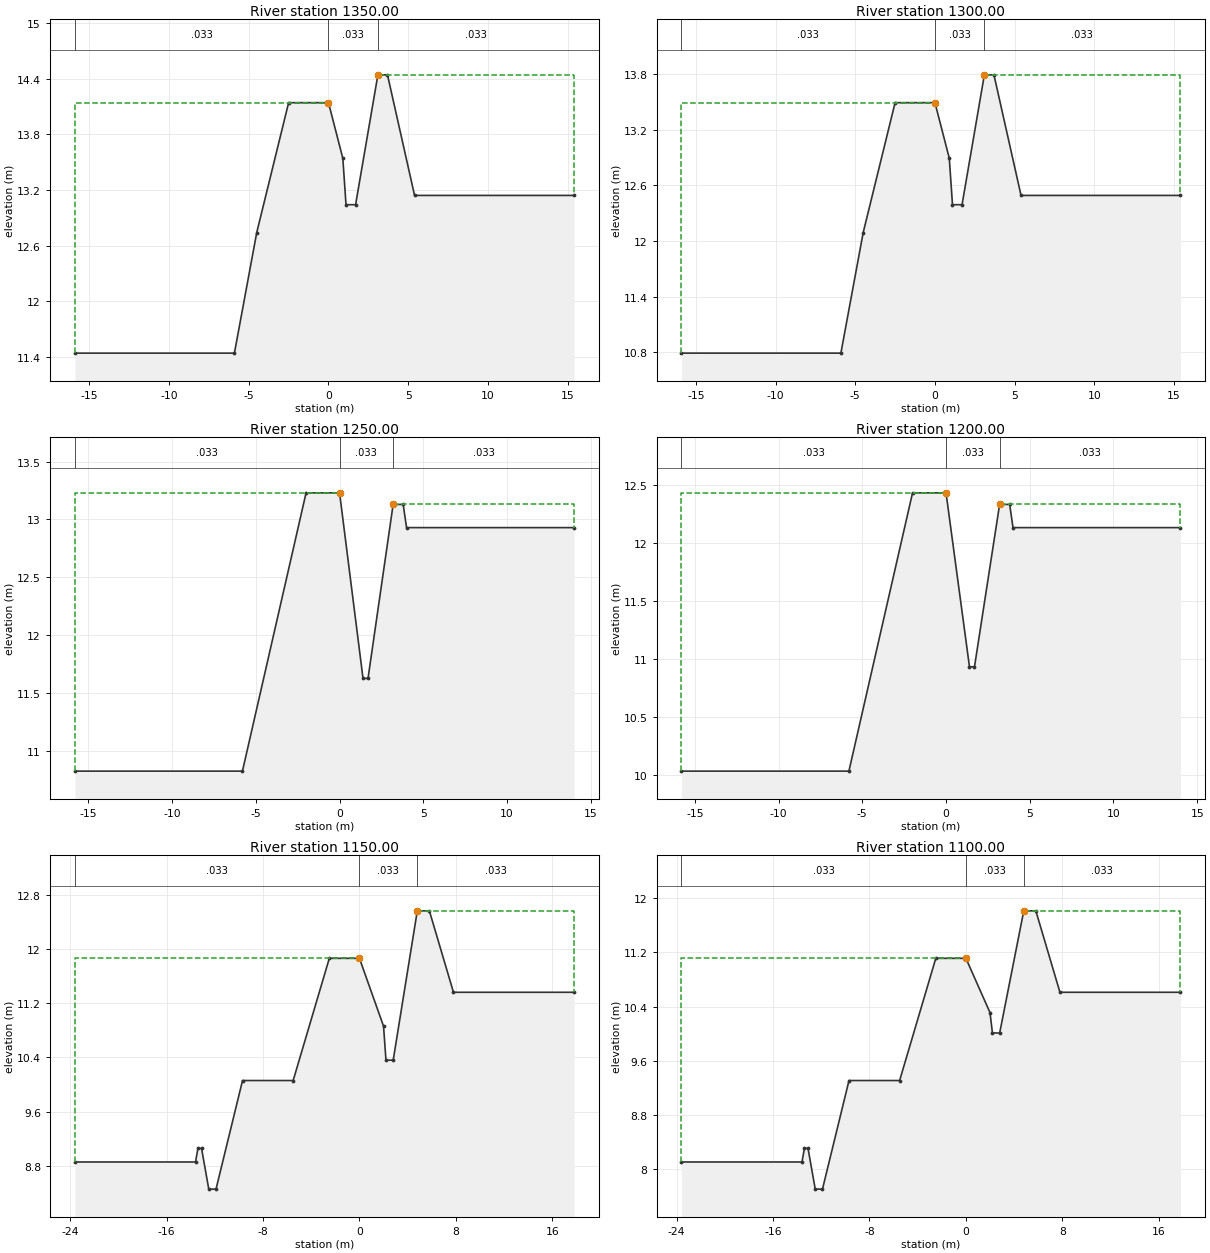
Type RM Length L Ch R = 1 ,1350.00 ,50,50,50
BEGIN DESCRIPTION:
27
END DESCRIPTION:
#Sta/Elev= 12
   -15.9   11.44    -5.9   11.44    -4.5   12.74    -2.5   14.14       0   14.14
      .9   13.54     1.1   13.04     1.7   13.04     3.1   14.44     3.7   14.44
     5.4   13.14    15.4   13.14
#Mann= 3 , 0 , 0
   -15.9    .033       0       0    .033       0     3.1    .033       0
#XS Ineff= 2 , 0
               0   14.14     3.1           14.44
Permanent Ineff=
       F       F
Bank Sta=0,3.1
XS Rating Curve= 0
Exp/Cntr=.3,.1

Type RM Length L Ch R = 1 ,1300.00 ,50,50,50
BEGIN DESCRIPTION:
26
END DESCRIPTION:
#Sta/Elev= 12
   -15.9   10.79    -5.9   10.79    -4.5   12.09    -2.5   13.49       0   13.49
      .9   12.89     1.1   12.39     1.7   12.39     3.1   13.79     3.7   13.79
     5.4   12.49    15.4   12.49
#Mann= 3 , 0 , 0
   -15.9    .033       0       0    .033       0     3.1    .033       0
#XS Ineff= 2 , 0
               0   13.49     3.1           13.79
Permanent Ineff=
       F       F
Bank Sta=0,3.1
XS Rating Curve= 0
Exp/Cntr=.3,.1

Type RM Length L Ch R = 1 ,1250.00 ,50,50,50
BEGIN DESCRIPTION:
25
END DESCRIPTION:
#Sta/Elev= 10
   -15.8   10.83    -5.8   10.83      -2   13.23       0   13.23     1.4   11.63
     1.7   11.63     3.2   13.13     3.8   13.13       4   12.93      14   12.93
#Mann= 3 , 0 , 0
   -15.8    .033       0       0    .033       0     3.2    .033       0
#XS Ineff= 2 , 0
               0   13.23     3.2           13.13
Permanent Ineff=
       F       F
Bank Sta=0,3.2
XS Rating Curve= 0
Exp/Cntr=.3,.1

Type RM Length L Ch R = 1 ,1200.00 ,50,50,50
BEGIN DESCRIPTION:
24
END DESCRIPTION:
#Sta/Elev= 10
   -15.8   10.03    -5.8   10.03      -2   12.43       0   12.43     1.4   10.93
     1.7   10.93     3.2   12.33     3.8   12.33       4   12.13      14   12.13
#Mann= 3 , 0 , 0
   -15.8    .033       0       0    .033       0     3.2    .033       0
#XS Ineff= 2 , 0
               0   12.43     3.2           12.33
Permanent Ineff=
       F       F
Bank Sta=0,3.2
XS Rating Curve= 0
Exp/Cntr=.3,.1

Type RM Length L Ch R = 1 ,1150.00 ,50,50,50
BEGIN DESCRIPTION:
23
END DESCRIPTION:
#Sta/Elev= 17
   -23.6    8.86   -13.6    8.86   -13.4    9.06   -13.1    9.06   -12.5    8.46
   -11.9    8.46    -9.7   10.06    -5.5   10.06    -2.5   11.86       0   11.86
       2   10.86     2.2   10.36     2.8   10.36     4.8   12.56     5.8   12.56
     7.8   11.36    17.8   11.36
#Mann= 3 , 0 , 0
   -23.6    .033       0       0    .033       0     4.8    .033       0
#XS Ineff= 2 , 0
               0   11.86     4.8           12.56
Permanent Ineff=
       F       F
Bank Sta=0,4.8
XS Rating Curve= 0
Exp/Cntr=.3,.1

Type RM Length L Ch R = 1 ,1100.00 ,50,50,50
BEGIN DESCRIPTION:
22
END DESCRIPTION:
#Sta/Elev= 17
   -23.6    8.11   -13.6    8.11   -13.4    8.31   -13.1    8.31   -12.5    7.71
   -11.9    7.71    -9.7    9.31    -5.5    9.31    -2.5   11.11       0   11.11
       2   10.31     2.2   10.01     2.8   10.01     4.8   11.81     5.8   11.81
     7.8   10.61    17.8   10.61
#Mann= 3 , 0 , 0
   -23.6    .033       0       0    .033       0     4.8    .033       0
#XS Ineff= 2 , 0
               0   11.11     4.8           11.81
Permanent Ineff=
       F       F
Bank Sta=0,4.8
XS Rating Curve= 0
Exp/Cntr=.3,.1

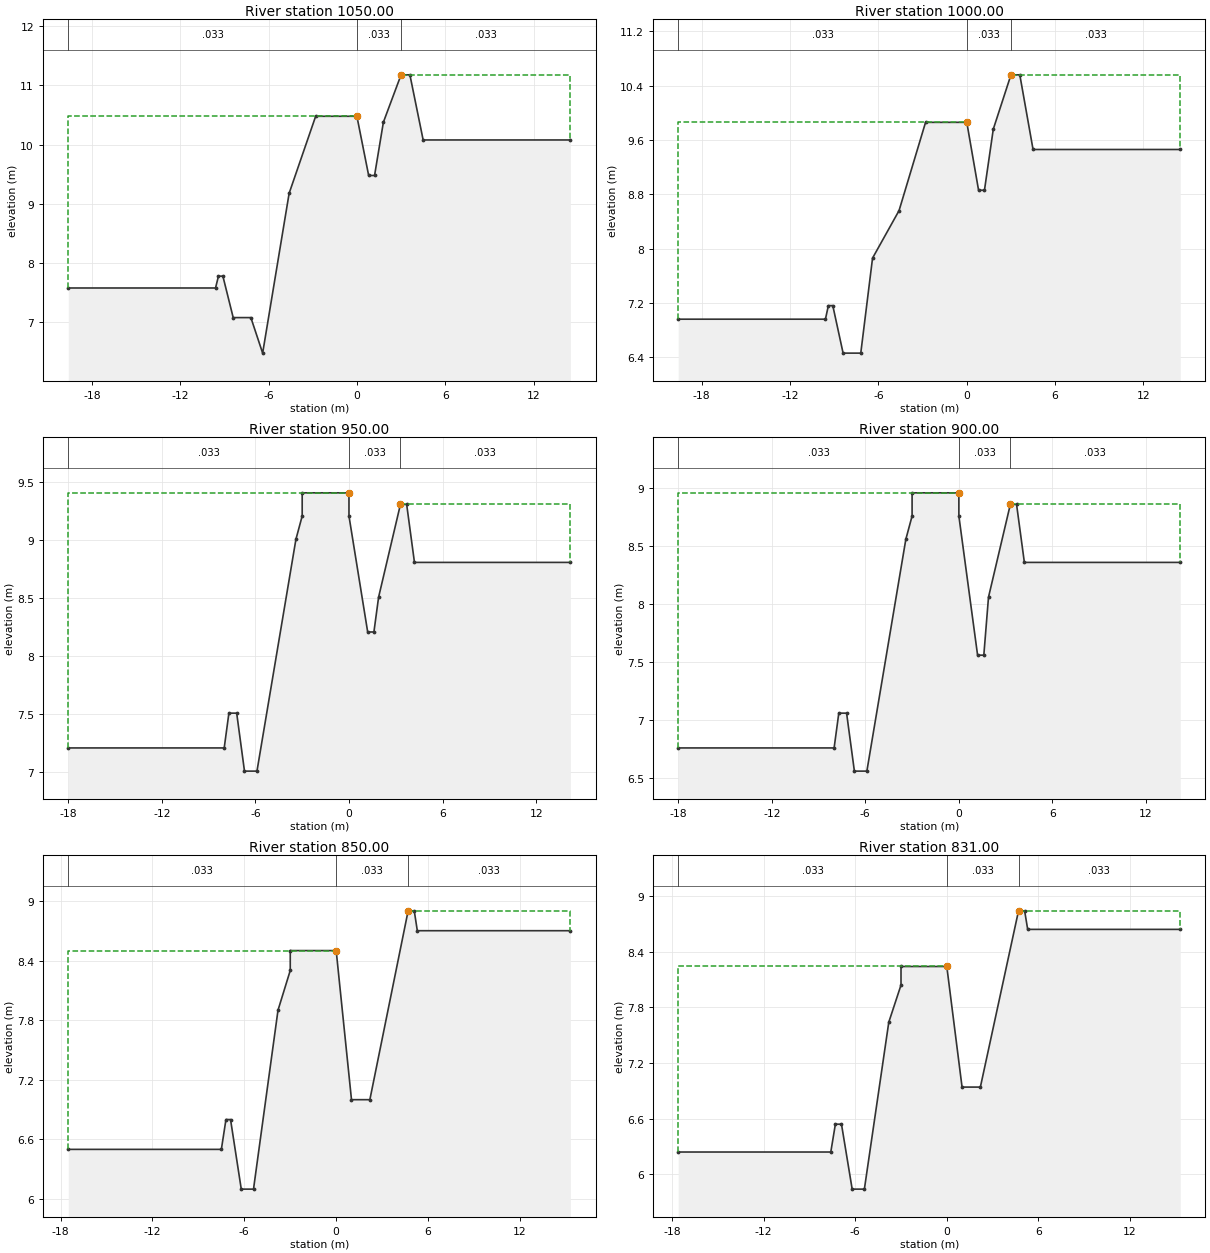
Type RM Length L Ch R = 1 ,1050.00 ,50,50,50
BEGIN DESCRIPTION:
21
END DESCRIPTION:
#Sta/Elev= 17
   -19.6    7.58    -9.6    7.58    -9.4    7.78    -9.1    7.78    -8.4    7.08
    -7.2    7.08    -6.4    6.48    -4.6    9.18    -2.8   10.48       0   10.48
      .8    9.48     1.2    9.48     1.8   10.38       3   11.18     3.6   11.18
     4.5   10.08    14.5   10.08
#Mann= 3 , 0 , 0
   -19.6    .033       0       0    .033       0       3    .033       0
#XS Ineff= 2 , 0
               0   10.48       3           11.18
Permanent Ineff=
       F       F
Bank Sta=0,3
XS Rating Curve= 0
Exp/Cntr=.3,.1

Type RM Length L Ch R = 1 ,1000.00 ,50,50,50
BEGIN DESCRIPTION:
20
END DESCRIPTION:
#Sta/Elev= 17
   -19.6    6.96    -9.6    6.96    -9.4    7.16    -9.1    7.16    -8.4    6.46
    -7.2    6.46    -6.4    7.86    -4.6    8.56    -2.8    9.86       0    9.86
      .8    8.86     1.2    8.86     1.8    9.76       3   10.56     3.6   10.56
     4.5    9.46    14.5    9.46
#Mann= 3 , 0 , 0
   -19.6    .033       0       0    .033       0       3    .033       0
#XS Ineff= 2 , 0
               0    9.86       3           10.56
Permanent Ineff=
       F       F
Bank Sta=0,3
XS Rating Curve= 0
Exp/Cntr=.3,.1

Type RM Length L Ch R = 1 ,950.00  ,50,50,50
BEGIN DESCRIPTION:
19
END DESCRIPTION:
#Sta/Elev= 18
     -18    7.21      -8    7.21    -7.7    7.51    -7.2    7.51    -6.7    7.01
    -5.9    7.01    -3.4    9.01      -3    9.21      -3    9.41       0    9.41
       0    9.21     1.2    8.21     1.6    8.21     1.9    8.51     3.3    9.31
     3.7    9.31     4.2    8.81    14.2    8.81
#Mann= 3 , 0 , 0
     -18    .033       0       0    .033       0     3.3    .033       0
#XS Ineff= 2 , 0
               0    9.41     3.3            9.31
Permanent Ineff=
       F       F
Bank Sta=0,3.3
XS Rating Curve= 0
Exp/Cntr=.3,.1

Type RM Length L Ch R = 1 ,900.00  ,50,50,50
BEGIN DESCRIPTION:
18
END DESCRIPTION:
#Sta/Elev= 18
     -18    6.76      -8    6.76    -7.7    7.06    -7.2    7.06    -6.7    6.56
    -5.9    6.56    -3.4    8.56      -3    8.76      -3    8.96       0    8.96
       0    8.76     1.2    7.56     1.6    7.56     1.9    8.06     3.3    8.86
     3.7    8.86     4.2    8.36    14.2    8.36
#Mann= 3 , 0 , 0
     -18    .033       0       0    .033       0     3.3    .033       0
#XS Ineff= 2 , 0
               0    8.96     3.3            8.86
Permanent Ineff=
       F       F
Bank Sta=0,3.3
XS Rating Curve= 0
Exp/Cntr=.3,.1

Type RM Length L Ch R = 1 ,850.00  ,19,19,19
BEGIN DESCRIPTION:
17
END DESCRIPTION:
#Sta/Elev= 16
   -17.5     6.5    -7.5     6.5    -7.2     6.8    -6.9     6.8    -6.2     6.1
    -5.4     6.1    -3.8     7.9      -3     8.3      -3     8.5       0     8.5
       1       7     2.2       7     4.7     8.9     5.1     8.9     5.3     8.7
    15.3     8.7
#Mann= 3 , 0 , 0
   -17.5    .033       0       0    .033       0     4.7    .033       0
#XS Ineff= 2 , 0
               0     8.5     4.7             8.9
Permanent Ineff=
       F       F
Bank Sta=0,4.7
XS Rating Curve= 0
Exp/Cntr=.3,.1

Type RM Length L Ch R = 1 ,831.00  ,31,31,31
BEGIN DESCRIPTION:
16.031
END DESCRIPTION:
#Sta/Elev= 16
   -17.6    6.24    -7.6    6.24    -7.3    6.54    -6.9    6.54    -6.2    5.84
    -5.4    5.84    -3.8    7.64      -3    8.04      -3    8.24       0    8.24
       1    6.94     2.2    6.94     4.7    8.84     5.1    8.84     5.3    8.64
    15.3    8.64
#Mann= 3 , 0 , 0
   -17.6    .033       0       0    .033       0     4.7    .033       0
#XS Ineff= 2 , 0
               0    8.24     4.7            8.84
Permanent Ineff=
       F       F
Bank Sta=0,4.7
XS Rating Curve= 0
Exp/Cntr=.3,.1

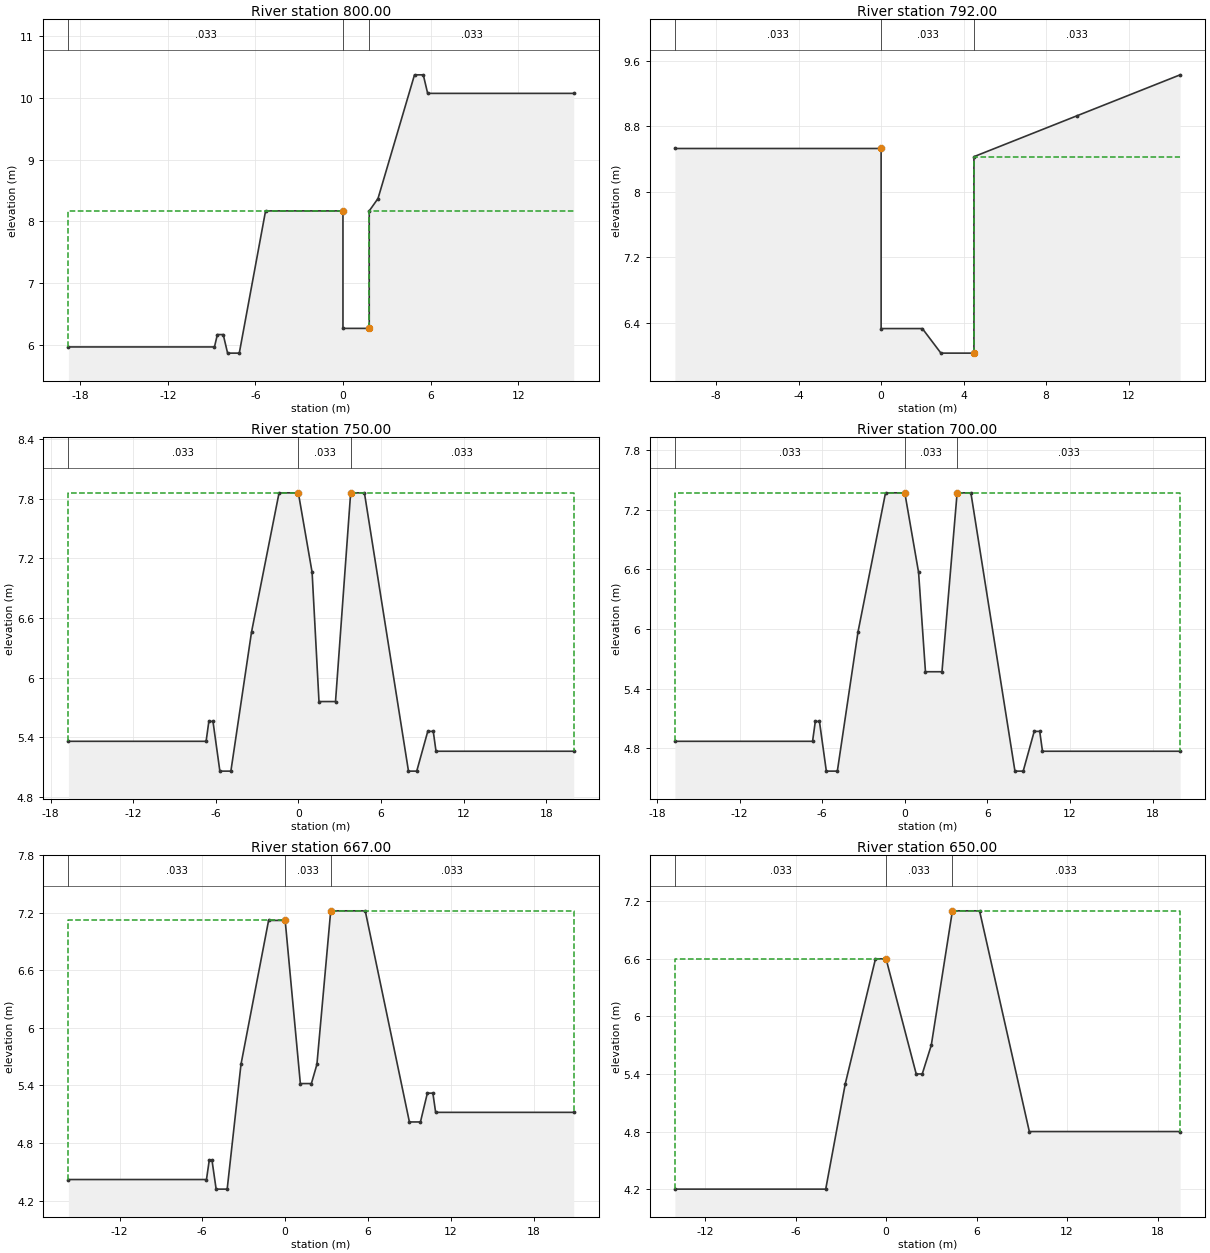
Type RM Length L Ch R = 1 ,800.00  ,8,8,8
BEGIN DESCRIPTION:
16
END DESCRIPTION:
#Sta/Elev= 16
   -18.8    5.97    -8.8    5.97    -8.6    6.17    -8.2    6.17    -7.9    5.87
    -7.1    5.87    -5.3    8.17       0    8.17       0    6.27     1.8    6.27
     1.8    8.17     2.4    8.37     4.9   10.37     5.5   10.37     5.8   10.07
    15.8   10.07
#Mann= 3 , 0 , 0
   -18.8    .033       0       0    .033       0     1.8    .033       0
#XS Ineff= 2 , 0
               0    8.17     1.8            8.17
Permanent Ineff=
       F       F
Bank Sta=0,1.8
XS Rating Curve= 0
Exp/Cntr=.3,.1

Type RM Length L Ch R = 1 ,792.00  ,42,42,42
BEGIN DESCRIPTION:
15.042
END DESCRIPTION:
#Sta/Elev= 9
     -10    8.53       0    8.53       0    6.33       2    6.33     2.9    6.03
     4.5    6.03     4.5    8.43     9.5    8.93    14.5    9.43
#Mann= 3 , 0 , 0
     -10    .033       0       0    .033       0     4.5    .033       0
#XS Ineff= 2 , 0
               0    8.53     4.5            8.43
Permanent Ineff=
       F       F
Bank Sta=0,4.5
XS Rating Curve= 0
Exp/Cntr=.3,.1

Type RM Length L Ch R = 1 ,750.00  ,50,50,50
BEGIN DESCRIPTION:
15
END DESCRIPTION:
#Sta/Elev= 20
   -16.7    5.36    -6.7    5.36    -6.5    5.56    -6.2    5.56    -5.7    5.06
    -4.9    5.06    -3.4    6.46    -1.4    7.86       0    7.86       1    7.06
     1.5    5.76     2.7    5.76     3.8    7.86     4.8    7.86       8    5.06
     8.6    5.06     9.4    5.46     9.8    5.46      10    5.26      20    5.26
#Mann= 3 , 0 , 0
   -16.7    .033       0       0    .033       0     3.8    .033       0
#XS Ineff= 2 , 0
               0    7.86     3.8            7.86
Permanent Ineff=
       F       F
Bank Sta=0,3.8
XS Rating Curve= 0
Exp/Cntr=.3,.1

Type RM Length L Ch R = 1 ,700.00  ,33,33,33
BEGIN DESCRIPTION:
14
END DESCRIPTION:
#Sta/Elev= 20
   -16.7    4.87    -6.7    4.87    -6.5    5.07    -6.2    5.07    -5.7    4.57
    -4.9    4.57    -3.4    5.97    -1.4    7.37       0    7.37       1    6.57
     1.5    5.57     2.7    5.57     3.8    7.37     4.8    7.37       8    4.57
     8.6    4.57     9.4    4.97     9.8    4.97      10    4.77      20    4.77
#Mann= 3 , 0 , 0
   -16.7    .033       0       0    .033       0     3.8    .033       0
#XS Ineff= 2 , 0
               0    7.37     3.8            7.37
Permanent Ineff=
       F       F
Bank Sta=0,3.8
XS Rating Curve= 0
Exp/Cntr=.3,.1

Type RM Length L Ch R = 1 ,667.00  ,17,17,17
BEGIN DESCRIPTION:
13.017
END DESCRIPTION:
#Sta/Elev= 20
   -15.7    4.42    -5.7    4.42    -5.5    4.62    -5.3    4.62      -5    4.32
    -4.2    4.32    -3.2    5.62    -1.2    7.12       0    7.12     1.1    5.42
     1.9    5.42     2.3    5.62     3.3    7.22     5.8    7.22       9    5.02
     9.8    5.02    10.3    5.32    10.7    5.32    10.9    5.12    20.9    5.12
#Mann= 3 , 0 , 0
   -15.7    .033       0       0    .033       0     3.3    .033       0
#XS Ineff= 2 , 0
               0    7.12     3.3            7.22
Permanent Ineff=
       F       F
Bank Sta=0,3.3
XS Rating Curve= 0
Exp/Cntr=.3,.1

Type RM Length L Ch R = 1 ,650.00  ,50,50,50
BEGIN DESCRIPTION:
13
END DESCRIPTION:
#Sta/Elev= 12
     -14     4.2      -4     4.2    -2.7     5.3     -.7     6.6       0     6.6
       2     5.4     2.4     5.4       3     5.7     4.4     7.1     6.2     7.1
     9.5     4.8    19.5     4.8
#Mann= 3 , 0 , 0
     -14    .033       0       0    .033       0     4.4    .033       0
#XS Ineff= 2 , 0
               0     6.6     4.4             7.1
Permanent Ineff=
       F       F
Bank Sta=0,4.4
XS Rating Curve= 0
Exp/Cntr=.3,.1

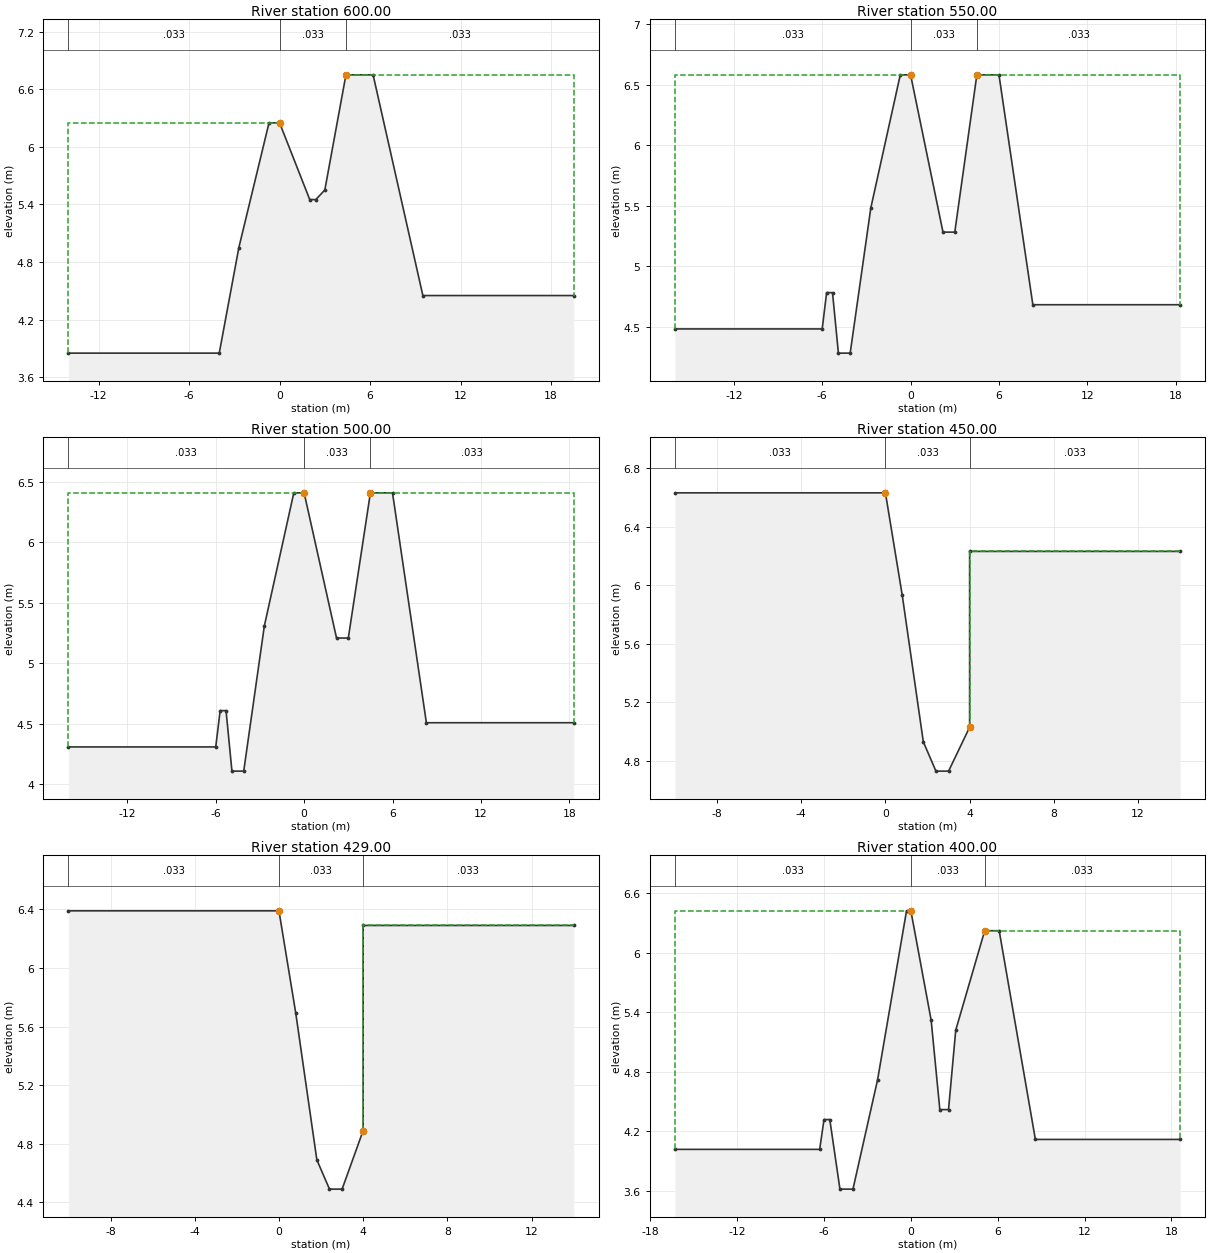
Type RM Length L Ch R = 1 ,600.00  ,50,50,50
BEGIN DESCRIPTION:
12
END DESCRIPTION:
#Sta/Elev= 12
     -14    3.85      -4    3.85    -2.7    4.95     -.7    6.25       0    6.25
       2    5.45     2.4    5.45       3    5.55     4.4    6.75     6.2    6.75
     9.5    4.45    19.5    4.45
#Mann= 3 , 0 , 0
     -14    .033       0       0    .033       0     4.4    .033       0
#XS Ineff= 2 , 0
               0    6.25     4.4            6.75
Permanent Ineff=
       F       F
Bank Sta=0,4.4
XS Rating Curve= 0
Exp/Cntr=.3,.1

Type RM Length L Ch R = 1 ,550.00  ,50,50,50
BEGIN DESCRIPTION:
11
END DESCRIPTION:
#Sta/Elev= 15
     -16    4.48      -6    4.48    -5.7    4.78    -5.3    4.78    -4.9    4.28
    -4.1    4.28    -2.7    5.48     -.7    6.58       0    6.58     2.2    5.28
       3    5.28     4.5    6.58       6    6.58     8.3    4.68    18.3    4.68
#Mann= 3 , 0 , 0
     -16    .033       0       0    .033       0     4.5    .033       0
#XS Ineff= 2 , 0
               0    6.58     4.5            6.58
Permanent Ineff=
       F       F
Bank Sta=0,4.5
XS Rating Curve= 0
Exp/Cntr=.3,.1

Type RM Length L Ch R = 1 ,500.00  ,50,50,50
BEGIN DESCRIPTION:
10
END DESCRIPTION:
#Sta/Elev= 15
     -16    4.31      -6    4.31    -5.7    4.61    -5.3    4.61    -4.9    4.11
    -4.1    4.11    -2.7    5.31     -.7    6.41       0    6.41     2.2    5.21
       3    5.21     4.5    6.41       6    6.41     8.3    4.51    18.3    4.51
#Mann= 3 , 0 , 0
     -16    .033       0       0    .033       0     4.5    .033       0
#XS Ineff= 2 , 0
               0    6.41     4.5            6.41
Permanent Ineff=
       F       F
Bank Sta=0,4.5
XS Rating Curve= 0
Exp/Cntr=.3,.1

Type RM Length L Ch R = 1 ,450.00  ,21,21,21
BEGIN DESCRIPTION:
9
END DESCRIPTION:
#Sta/Elev= 9
     -10    6.63       0    6.63      .8    5.93     1.8    4.93     2.4    4.73
       3    4.73       4    5.03       4    6.23      14    6.23
#Mann= 3 , 0 , 0
     -10    .033       0       0    .033       0       4    .033       0
#XS Ineff= 2 , 0
               0    6.63       4            6.23
Permanent Ineff=
       F       F
Bank Sta=0,4
XS Rating Curve= 0
Exp/Cntr=.3,.1

Type RM Length L Ch R = 1 ,429.00  ,29,29,29
BEGIN DESCRIPTION:
8.029
END DESCRIPTION:
#Sta/Elev= 9
     -10    6.39       0    6.39      .8    5.69     1.8    4.69     2.4    4.49
       3    4.49       4    4.89       4    6.29      14    6.29
#Mann= 3 , 0 , 0
     -10    .033       0       0    .033       0       4    .033       0
#XS Ineff= 2 , 0
               0    6.39       4            6.29
Permanent Ineff=
       F       F
Bank Sta=0,4
XS Rating Curve= 0
Exp/Cntr=.3,.1

Type RM Length L Ch R = 1 ,400.00  ,50,50,50
BEGIN DESCRIPTION:
8
END DESCRIPTION:
#Sta/Elev= 17
   -16.3    4.02    -6.3    4.02      -6    4.32    -5.6    4.32    -4.9    3.62
      -4    3.62    -2.3    4.72     -.3    6.42       0    6.42     1.4    5.32
       2    4.42     2.6    4.42     3.1    5.22     5.1    6.22     6.1    6.22
     8.6    4.12    18.6    4.12
#Mann= 3 , 0 , 0
   -16.3    .033       0       0    .033       0     5.1    .033       0
#XS Ineff= 2 , 0
               0    6.42     5.1            6.22
Permanent Ineff=
       F       F
Bank Sta=0,5.1
XS Rating Curve= 0
Exp/Cntr=.3,.1

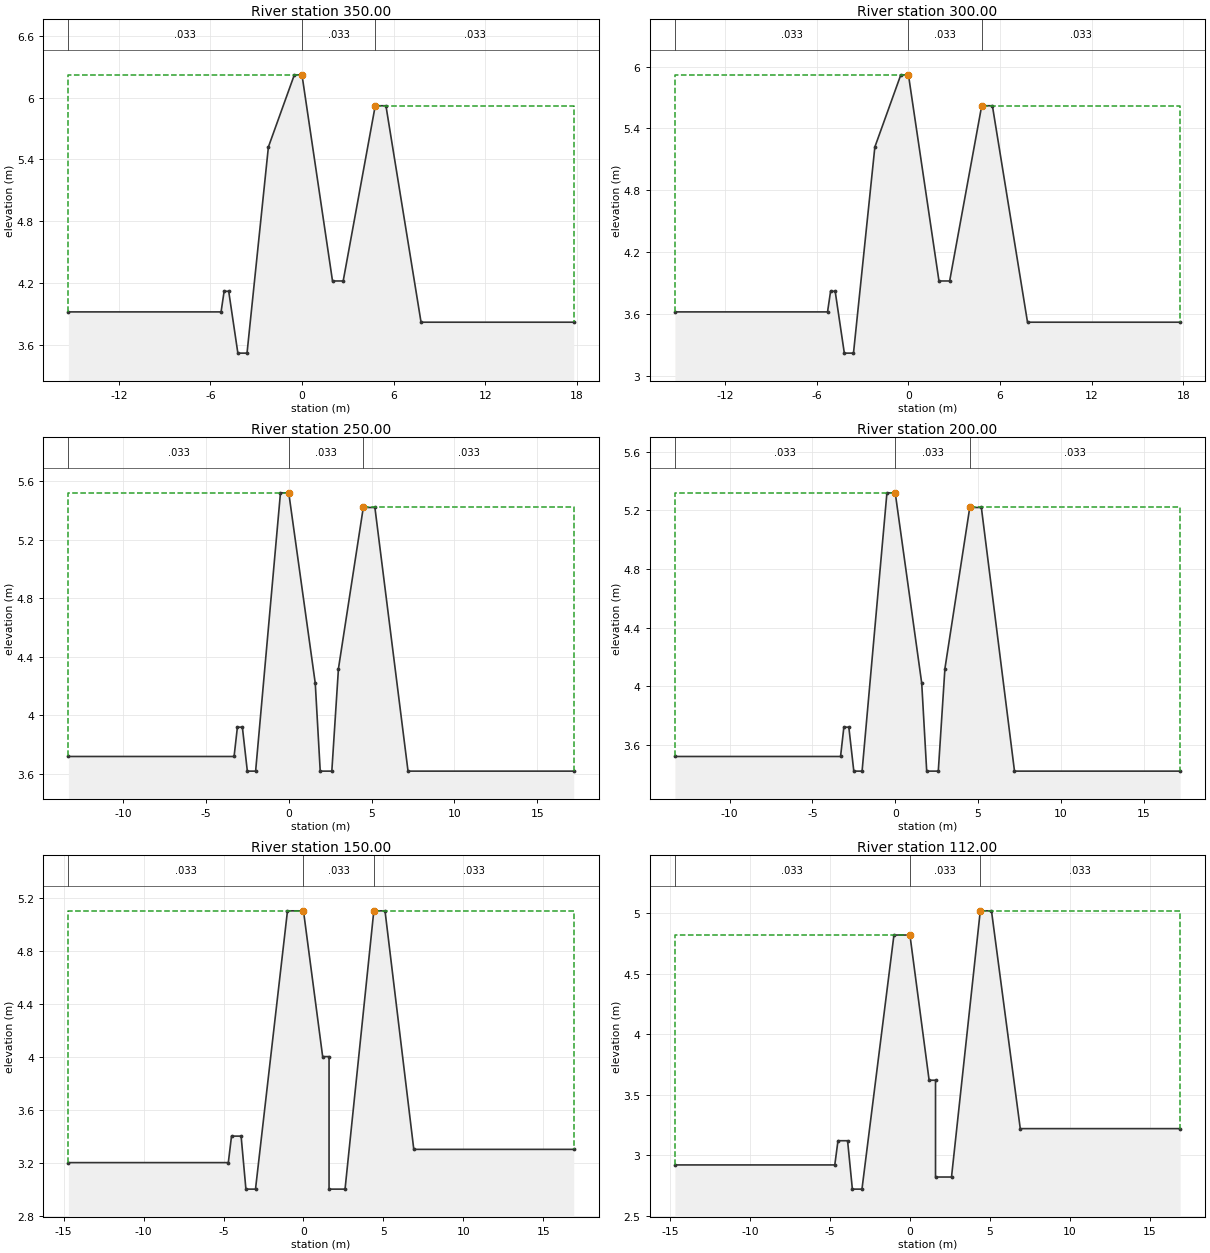
Type RM Length L Ch R = 1 ,350.00  ,50,50,50
BEGIN DESCRIPTION:
7
END DESCRIPTION:
#Sta/Elev= 15
   -15.3    3.92    -5.3    3.92    -5.1    4.12    -4.8    4.12    -4.2    3.52
    -3.6    3.52    -2.2    5.52     -.5    6.22       0    6.22       2    4.22
     2.7    4.22     4.8    5.92     5.5    5.92     7.8    3.82    17.8    3.82
#Mann= 3 , 0 , 0
   -15.3    .033       0       0    .033       0     4.8    .033       0
#XS Ineff= 2 , 0
               0    6.22     4.8            5.92
Permanent Ineff=
       F       F
Bank Sta=0,4.8
XS Rating Curve= 0
Exp/Cntr=.3,.1

Type RM Length L Ch R = 1 ,300.00  ,50,50,50
BEGIN DESCRIPTION:
6
END DESCRIPTION:
#Sta/Elev= 15
   -15.3    3.62    -5.3    3.62    -5.1    3.82    -4.8    3.82    -4.2    3.22
    -3.6    3.22    -2.2    5.22     -.5    5.92       0    5.92       2    3.92
     2.7    3.92     4.8    5.62     5.5    5.62     7.8    3.52    17.8    3.52
#Mann= 3 , 0 , 0
   -15.3    .033       0       0    .033       0     4.8    .033       0
#XS Ineff= 2 , 0
               0    5.92     4.8            5.62
Permanent Ineff=
       F       F
Bank Sta=0,4.8
XS Rating Curve= 0
Exp/Cntr=.3,.1

Type RM Length L Ch R = 1 ,250.00  ,50,50,50
BEGIN DESCRIPTION:
5
END DESCRIPTION:
#Sta/Elev= 16
   -13.3    3.72    -3.3    3.72    -3.1    3.92    -2.8    3.92    -2.5    3.62
      -2    3.62     -.5    5.52       0    5.52     1.6    4.22     1.9    3.62
     2.6    3.62       3    4.32     4.5    5.42     5.2    5.42     7.2    3.62
    17.2    3.62
#Mann= 3 , 0 , 0
   -13.3    .033       0       0    .033       0     4.5    .033       0
#XS Ineff= 2 , 0
               0    5.52     4.5            5.42
Permanent Ineff=
       F       F
Bank Sta=0,4.5
XS Rating Curve= 0
Exp/Cntr=.3,.1

Type RM Length L Ch R = 1 ,200.00  ,50,50,50
BEGIN DESCRIPTION:
4
END DESCRIPTION:
#Sta/Elev= 16
   -13.3    3.52    -3.3    3.52    -3.1    3.72    -2.8    3.72    -2.5    3.42
      -2    3.42     -.5    5.32       0    5.32     1.6    4.02     1.9    3.42
     2.6    3.42       3    4.12     4.5    5.22     5.2    5.22     7.2    3.42
    17.2    3.42
#Mann= 3 , 0 , 0
   -13.3    .033       0       0    .033       0     4.5    .033       0
#XS Ineff= 2 , 0
               0    5.32     4.5            5.22
Permanent Ineff=
       F       F
Bank Sta=0,4.5
XS Rating Curve= 0
Exp/Cntr=.3,.1

Type RM Length L Ch R = 1 ,150.00  ,38,38,38
BEGIN DESCRIPTION:
3
END DESCRIPTION:
#Sta/Elev= 16
   -14.7     3.2    -4.7     3.2    -4.5     3.4    -3.9     3.4    -3.6       3
      -3       3      -1     5.1       0     5.1     1.2       4     1.6       4
     1.6       3     2.6       3     4.4     5.1     5.1     5.1     6.9     3.3
    16.9     3.3
#Mann= 3 , 0 , 0
   -14.7    .033       0       0    .033       0     4.4    .033       0
#XS Ineff= 2 , 0
               0     5.1     4.4             5.1
Permanent Ineff=
       F       F
Bank Sta=0,4.4
XS Rating Curve= 0
Exp/Cntr=.3,.1

Type RM Length L Ch R = 1 ,112.00  ,12,12,12
BEGIN DESCRIPTION:
2.012
END DESCRIPTION:
#Sta/Elev= 16
   -14.7    2.92    -4.7    2.92    -4.5    3.12    -3.9    3.12    -3.6    2.72
      -3    2.72      -1    4.82       0    4.82     1.2    3.62     1.6    3.62
     1.6    2.82     2.6    2.82     4.4    5.02     5.1    5.02     6.9    3.22
    16.9    3.22
#Mann= 3 , 0 , 0
   -14.7    .033       0       0    .033       0     4.4    .033       0
#XS Ineff= 2 , 0
               0    4.82     4.4            5.02
Permanent Ineff=
       F       F
Bank Sta=0,4.4
XS Rating Curve= 0
Exp/Cntr=.3,.1

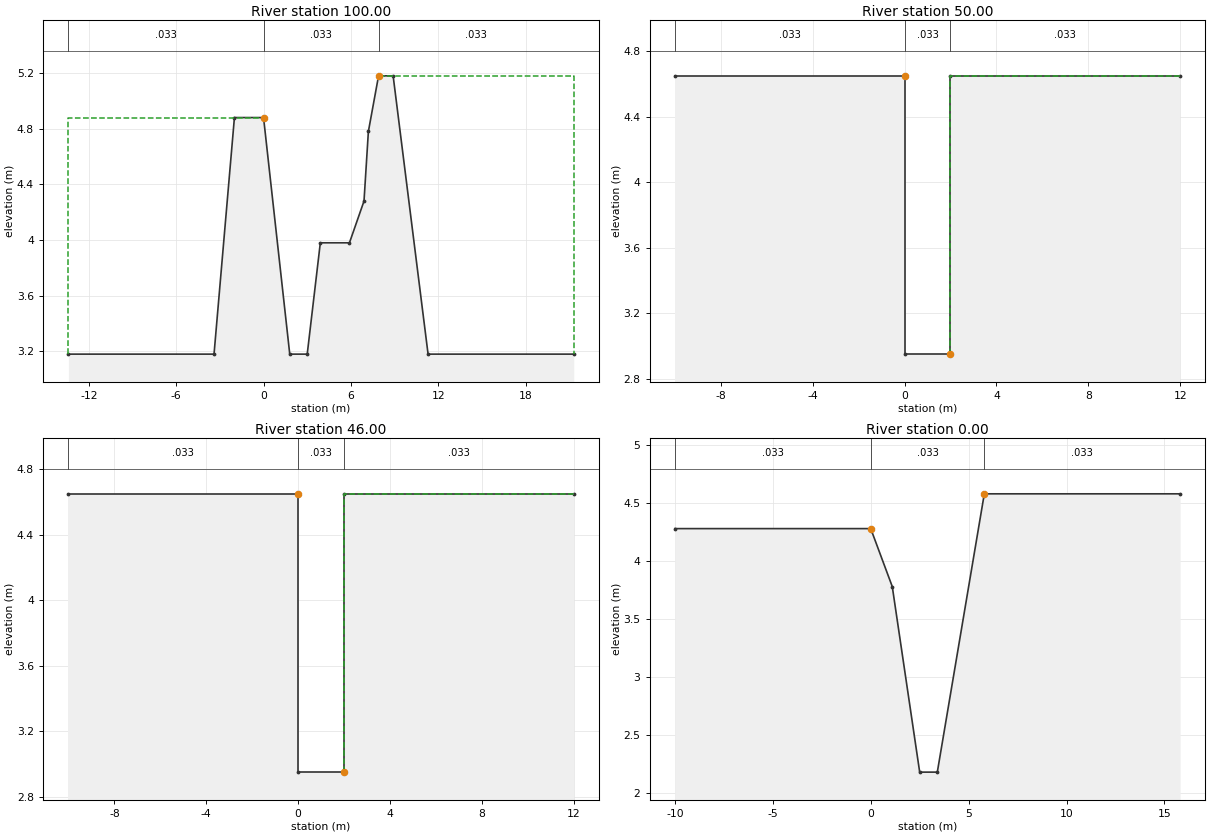
Type RM Length L Ch R = 1 ,100.00  ,50,50,50
BEGIN DESCRIPTION:
2
END DESCRIPTION:
#Sta/Elev= 14
   -13.4    3.18    -3.4    3.18      -2    4.88       0    4.88     1.8    3.18
       3    3.18     3.9    3.98     5.9    3.98     6.9    4.28     7.2    4.78
     7.9    5.18     8.9    5.18    11.3    3.18    21.3    3.18
#Mann= 3 , 0 , 0
   -13.4    .033       0       0    .033       0     7.9    .033       0
#XS Ineff= 2 , 0
               0    4.88     7.9            5.18
Permanent Ineff=
       F       F
Bank Sta=0,7.9
XS Rating Curve= 0
Exp/Cntr=.3,.1

Type RM Length L Ch R = 1 ,50.00   ,4,4,4
BEGIN DESCRIPTION:
1
END DESCRIPTION:
#Sta/Elev= 6
     -10    4.65       0    4.65       0    2.95       2    2.95       2    4.65
      12    4.65
#Mann= 3 , 0 , 0
     -10    .033       0       0    .033       0       2    .033       0
#XS Ineff= 2 , 0
               0    4.65       2            4.65
Permanent Ineff=
       F       F
Bank Sta=0,2
XS Rating Curve= 0
Exp/Cntr=.3,.1

Type RM Length L Ch R = 1 ,46.00   ,46,46,46
BEGIN DESCRIPTION:
0.046
END DESCRIPTION:
#Sta/Elev= 6
     -10    4.65       0    4.65       0    2.95       2    2.95       2    4.65
      12    4.65
#Mann= 3 , 0 , 0
     -10    .033       0       0    .033       0       2    .033       0
#XS Ineff= 2 , 0
               0    4.65       2            4.65
Permanent Ineff=
       F       F
Bank Sta=0,2
XS Rating Curve= 0
Exp/Cntr=.3,.1

Type RM Length L Ch R = 1 ,0.00    ,0,0,0
BEGIN DESCRIPTION:
0
END DESCRIPTION:
#Sta/Elev= 7
     -10    4.28       0    4.28     1.1    3.78     2.5    2.18     3.4    2.18
     5.8    4.58    15.8    4.58
#Mann= 3 , 0 , 0
     -10    .033       0       0    .033       0     5.8    .033       0
#XS Ineff= 2 , 0
               0    4.28     5.8            4.58
Permanent Ineff=
       F       F
Bank Sta=0,5.8
XS Rating Curve= 0
Exp/Cntr=.3,.1

Chan Stop Cuts=-1