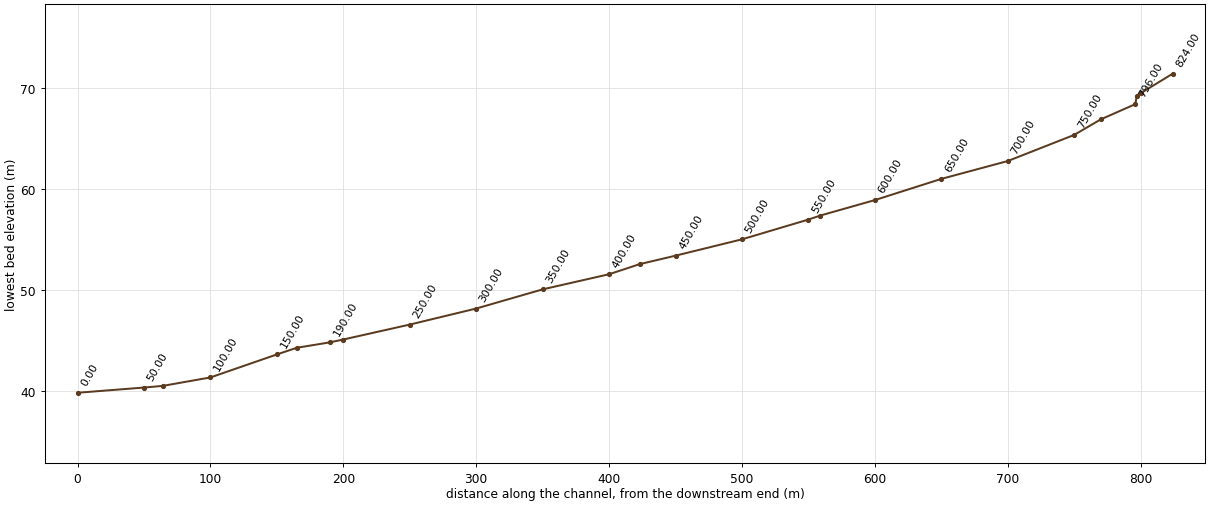
--- WGC.prj (project) ---

Proj Title=WGC
Current Plan=p01
Default Exp/Contr=.3,.1
SI Units
Geom File=g01
Flow File=f01
Plan File=p01
Y Axis Title=Elevation
X Axis Title(PF)=Main Channel Distance
X Axis Title(XS)=Station
BEGIN DESCRIPTION:
           BACK WATER COMPUTATION
      APPLICATION OF HEC-2 BY Samju Construction Engineering
      WOONGKOL-STREEM : 30 YR
END DESCRIPTION:
DSS Export Rating Curves= 0
DSS Export Rating Curve Sorted= 0
DSS Export Volume Flow Curves= 0
DXF OffsetX= 0
DXF OffsetY= 0
DXF ScaleX= 1
DXF ScaleY= 10

--- WGC.p01 (plan) ---

Plan Title=Imported Plan 01
Version=Version 3.0.1  Mar 2001
Short Identifier=Imported Pla
Geom File=g01
Flow File=f01
Subcritical Flow
K Sum by GR= 0
Std Step Tol= 0.003
Critical Tol= 0.003
Num of Std Step Trials= 20
Max Error Tol= 0.1
Flow Tol Ratio= 0.001
Split Flow NTrial= 30
Split Flow Tol= 0.02
Split Flow Ratio= 0.02
Log Output Level= 0
Friction Slope Method= 1
Unsteady Friction Slope Method= 2
Parabolic Critical Depth
Global Vel Dist= 0 , 0 , 0
Global Log Level= 0
CheckData=True
Encroach Param=-1 ,0,0, 0
Computation Interval=1HOUR
Output Interval=1HOUR
Run HTab= 0
Run UNet= 0
Run PostProcess= 0
UNET Theta= 1
UNET ZTol= 0.02
UNET ZSATol= 0.1
UNET MxIter= 20
UNET MaxInSteps= 20
UNET DtIC= 0
UNET DtMin= 0
UNET MaxCRTS= 20
UNET WFStab= 2
UNET SFStab= 1
UNET WFX= 1
UNET SFX= 1
UNET Convert EG Bridges=-1
UNET Use Existing IB Tables=-1
Instantaneous Interval=1HOUR
Write IC File= 0
Write Velocity= 0
Write Detailed= 0

--- WGC.f01 (steady flow) ---

Flow Title=Imported Flow 01
Version=Version 3.0.1  Mar 2001
Number of Profiles= 5
Profile Names=10YR,20YR,30YR,50YR,80YR
River Rch & RM=RIVER-1,Reach-1         ,824.00
    8.24    9.08    9.57   10.19   10.76
Boundary for River Rch & Prof#=RIVER-1,Reach-1         , 1
Up Type= 0
Dn Type= 3
Dn Slope=.03
Boundary for River Rch & Prof#=RIVER-1,Reach-1         , 2
Up Type= 0
Dn Type= 3
Dn Slope=.03
Boundary for River Rch & Prof#=RIVER-1,Reach-1         , 3
Up Type= 0
Dn Type= 3
Dn Slope=.03
Boundary for River Rch & Prof#=RIVER-1,Reach-1         , 4
Up Type= 0
Dn Type= 3
Dn Slope=.03
Boundary for River Rch & Prof#=RIVER-1,Reach-1         , 5
Up Type= 0
Dn Type= 3
Dn Slope=.03
DSS Import GetInterval= 0
DSS Import GetPeak= 0
DSS Import FillOption= 0

--- WGC.g01 (geometry) ---

Geom Title=Imported Geom 01
Version=Version 3.0.1  Mar 2001

River Reach=RIVER-1         ,Reach-1
Reach XY= 2
              .5             .95              .5             .05

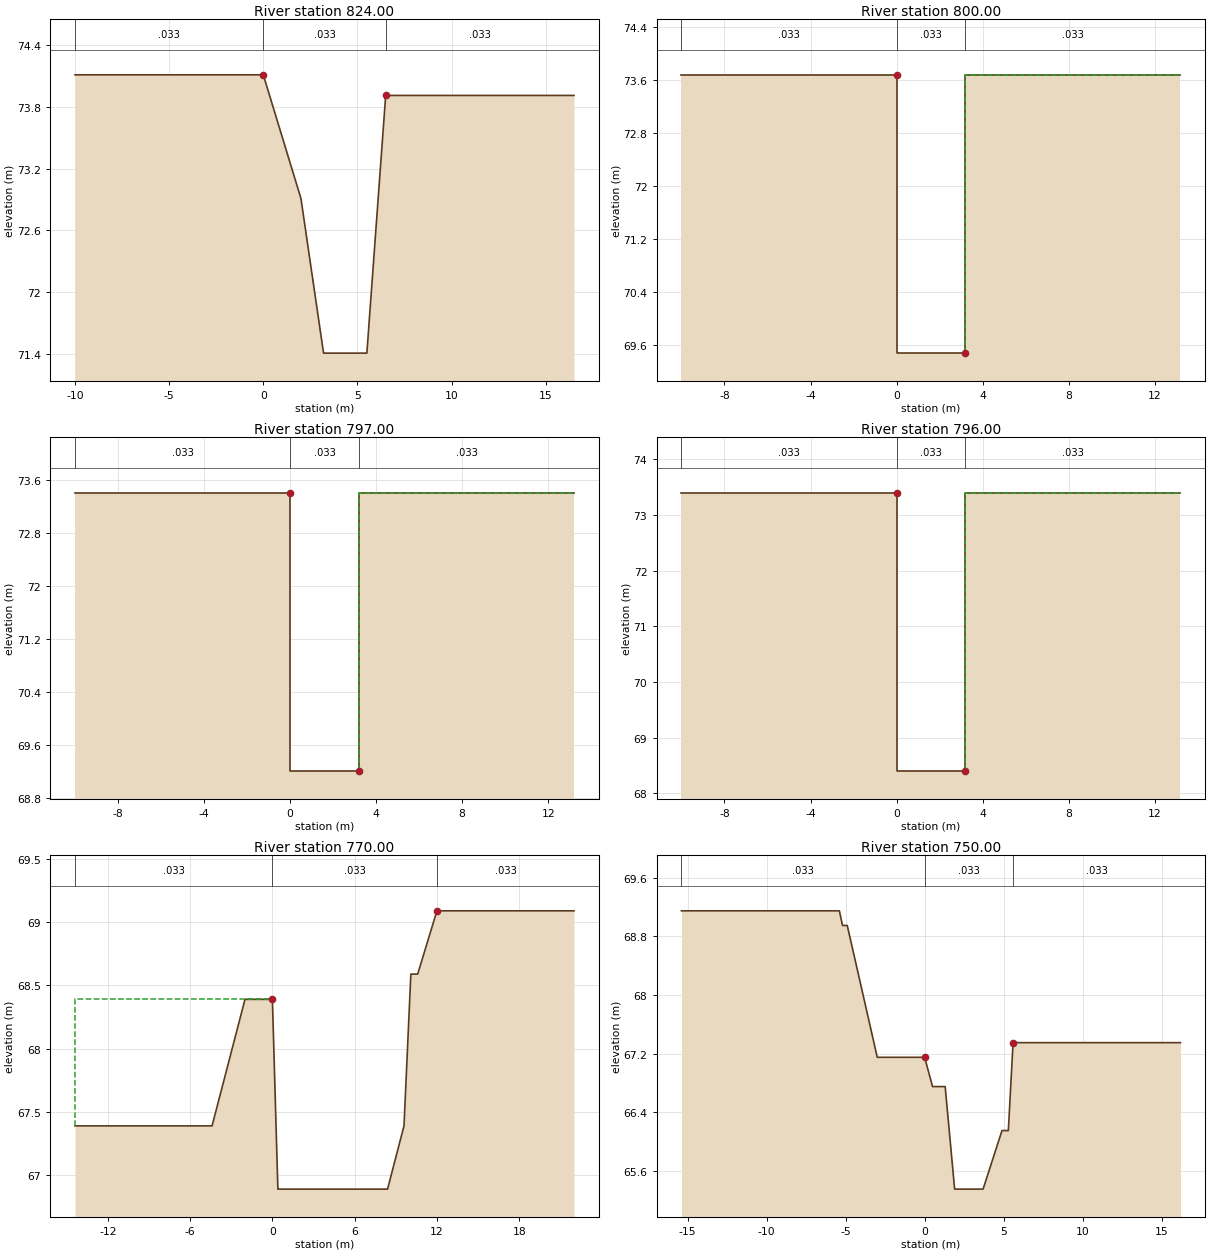
Type RM Length L Ch R = 1 ,824.00  ,24,24,24
BEGIN DESCRIPTION:
16.024
END DESCRIPTION:
#Sta/Elev= 7
     -10   74.11       0   74.11       2   72.91     3.2   71.41     5.5   71.41
     6.5   73.91    16.5   73.91
#Mann= 3 , 0 , 0
     -10    .033       0       0    .033       0     6.5    .033       0
#XS Ineff= 2 , 0
               0   74.11     6.5           73.91
Permanent Ineff=
       F       F
Bank Sta=0,6.5
XS Rating Curve= 0
Exp/Cntr=.3,.1

Type RM Length L Ch R = 1 ,800.00  ,3,3,3
BEGIN DESCRIPTION:
16
END DESCRIPTION:
#Sta/Elev= 6
     -10   73.68       0   73.68       0   69.48     3.2   69.48     3.2   73.68
    13.2   73.68
#Mann= 3 , 0 , 0
     -10    .033       0       0    .033       0     3.2    .033       0
#XS Ineff= 2 , 0
               0   73.68     3.2           73.68
Permanent Ineff=
       F       F
Bank Sta=0,3.2
XS Rating Curve= 0
Exp/Cntr=.3,.1

Type RM Length L Ch R = 1 ,797.00  ,1,1,1
BEGIN DESCRIPTION:
15.047
END DESCRIPTION:
#Sta/Elev= 6
     -10    73.4       0    73.4       0    69.2     3.2    69.2     3.2    73.4
    13.2    73.4
#Mann= 3 , 0 , 0
     -10    .033       0       0    .033       0     3.2    .033       0
#XS Ineff= 2 , 0
               0    73.4     3.2            73.4
Permanent Ineff=
       F       F
Bank Sta=0,3.2
XS Rating Curve= 0
Exp/Cntr=.3,.1

Type RM Length L Ch R = 1 ,796.00  ,26,26,26
BEGIN DESCRIPTION:
15.046
END DESCRIPTION:
#Sta/Elev= 8
     -10    73.4       0    73.4       0    69.2       0    68.4     3.2    68.4
     3.2    69.2     3.2    73.4    13.2    73.4
#Mann= 3 , 0 , 0
     -10    .033       0       0    .033       0     3.2    .033       0
#XS Ineff= 2 , 0
               0    73.4     3.2            73.4
Permanent Ineff=
       F       F
Bank Sta=0,3.2
XS Rating Curve= 0
Exp/Cntr=.3,.1

Type RM Length L Ch R = 1 ,770.00  ,20,20,20
BEGIN DESCRIPTION:
15.02
END DESCRIPTION:
#Sta/Elev= 11
   -14.4   67.39    -4.4   67.39      -2   68.39       0   68.39      .4   66.89
     8.4   66.89     9.6   67.39    10.1   68.59    10.6   68.59      12   69.09
      22   69.09
#Mann= 3 , 0 , 0
   -14.4    .033       0       0    .033       0      12    .033       0
#XS Ineff= 2 , 0
               0   68.39      12           69.09
Permanent Ineff=
       F       F
Bank Sta=0,12
XS Rating Curve= 0
Exp/Cntr=.3,.1

Type RM Length L Ch R = 1 ,750.00  ,50,50,50
BEGIN DESCRIPTION:
15
END DESCRIPTION:
#Sta/Elev= 15
   -15.4   69.15    -5.4   69.15    -5.2   68.95    -4.9   68.95      -3   67.15
       0   67.15      .5   66.75     1.3   66.75     1.9   65.35     3.7   65.35
     4.9   66.15     5.3   66.15     5.6   67.35     6.2   67.35    16.2   67.35
#Mann= 3 , 0 , 0
   -15.4    .033       0       0    .033       0     5.6    .033       0
#XS Ineff= 2 , 0
               0   67.15     5.6           67.35
Permanent Ineff=
       F       F
Bank Sta=0,5.6
XS Rating Curve= 0
Exp/Cntr=.3,.1

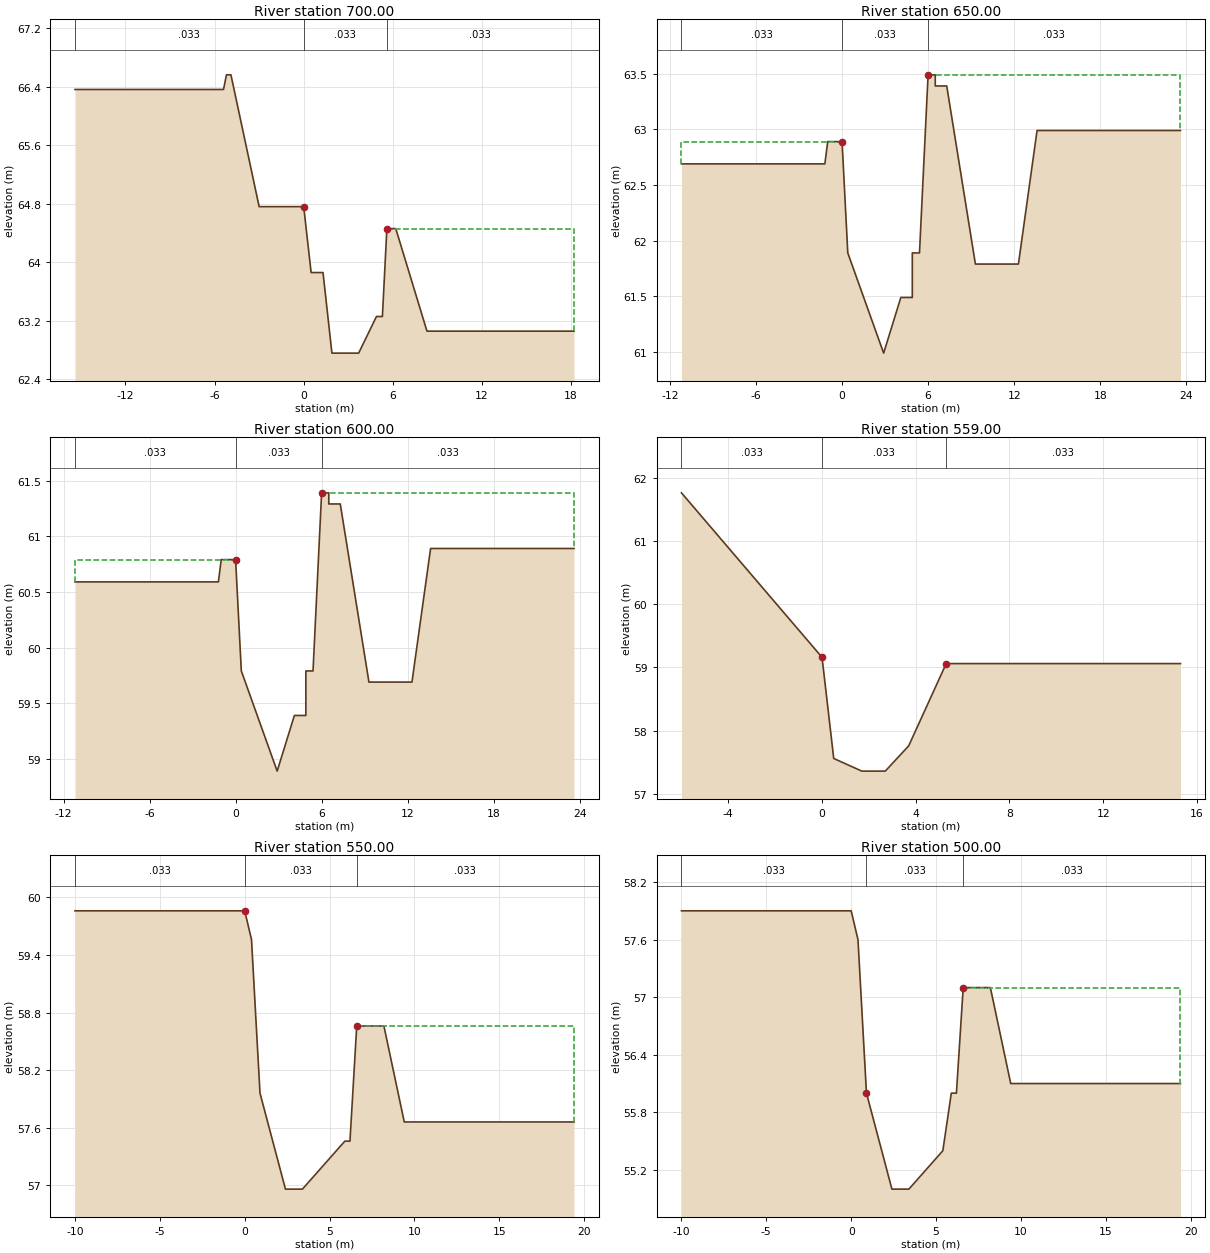
Type RM Length L Ch R = 1 ,700.00  ,50,50,50
BEGIN DESCRIPTION:
14
END DESCRIPTION:
#Sta/Elev= 16
   -15.4   66.36    -5.4   66.36    -5.2   66.56    -4.9   66.56      -3   64.76
       0   64.76      .5   63.86     1.3   63.86     1.9   62.76     3.7   62.76
     4.9   63.26     5.3   63.26     5.6   64.46     6.2   64.46     8.3   63.06
    18.2   63.06
#Mann= 3 , 0 , 0
   -15.4    .033       0       0    .033       0     5.6    .033       0
#XS Ineff= 2 , 0
               0   64.76     5.6           64.46
Permanent Ineff=
       F       F
Bank Sta=0,5.6
XS Rating Curve= 0
Exp/Cntr=.3,.1

Type RM Length L Ch R = 1 ,650.00  ,50,50,50
BEGIN DESCRIPTION:
13
END DESCRIPTION:
#Sta/Elev= 18
   -11.2   62.69    -1.2   62.69      -1   62.89       0   62.89      .4   61.89
     2.9   60.99     4.1   61.49     4.9   61.49     4.9   61.89     5.4   61.89
       6   63.49     6.5   63.49     6.5   63.39     7.3   63.39     9.3   61.79
    12.3   61.79    13.6   62.99    23.6   62.99
#Mann= 3 , 0 , 0
   -11.2    .033       0       0    .033       0       6    .033       0
#XS Ineff= 2 , 0
               0   62.89       6           63.49
Permanent Ineff=
       F       F
Bank Sta=0,6
XS Rating Curve= 0
Exp/Cntr=.3,.1

Type RM Length L Ch R = 1 ,600.00  ,41,41,41
BEGIN DESCRIPTION:
12
END DESCRIPTION:
#Sta/Elev= 18
   -11.2   60.59    -1.2   60.59      -1   60.79       0   60.79      .4   59.79
     2.9   58.89     4.1   59.39     4.9   59.39     4.9   59.79     5.4   59.79
       6   61.39     6.5   61.39     6.5   61.29     7.3   61.29     9.3   59.69
    12.3   59.69    13.6   60.89    23.6   60.89
#Mann= 3 , 0 , 0
   -11.2    .033       0       0    .033       0       6    .033       0
#XS Ineff= 2 , 0
               0   60.79       6           61.39
Permanent Ineff=
       F       F
Bank Sta=0,6
XS Rating Curve= 0
Exp/Cntr=.3,.1

Type RM Length L Ch R = 1 ,559.00  ,9,9,9
BEGIN DESCRIPTION:
11.009
END DESCRIPTION:
#Sta/Elev= 9
      -6   61.76      -3   60.46       0   59.16      .5   57.56     1.7   57.36
     2.7   57.36     3.7   57.76     5.3   59.06    15.3   59.06
#Mann= 3 , 0 , 0
      -6    .033       0       0    .033       0     5.3    .033       0
#XS Ineff= 2 , 0
               0   59.16     5.3           59.06
Permanent Ineff=
       F       F
Bank Sta=0,5.3
XS Rating Curve= 0
Exp/Cntr=.3,.1

Type RM Length L Ch R = 1 ,550.00  ,50,50,50
BEGIN DESCRIPTION:
11
END DESCRIPTION:
#Sta/Elev= 13
     -10   59.86       0   59.86      .4   59.56      .9   57.96     2.4   56.96
     3.4   56.96     5.4   57.36     5.9   57.46     6.2   57.46     6.6   58.66
     8.2   58.66     9.4   57.66    19.4   57.66
#Mann= 3 , 0 , 0
     -10    .033       0       0    .033       0     6.6    .033       0
#XS Ineff= 2 , 0
               0   59.86     6.6           58.66
Permanent Ineff=
       F       F
Bank Sta=0,6.6
XS Rating Curve= 0
Exp/Cntr=.3,.1

Type RM Length L Ch R = 1 ,500.00  ,50,50,50
BEGIN DESCRIPTION:
10
END DESCRIPTION:
#Sta/Elev= 13
     -10    57.9       0    57.9      .4    57.6      .9      56     2.4      55
     3.4      55     5.4    55.4     5.9      56     6.2      56     6.6    57.1
     8.2    57.1     9.4    56.1    19.4    56.1
#Mann= 3 , 0 , 0
     -10    .033       0      .9    .033       0     6.6    .033       0
#XS Ineff= 2 , 0
              .9      56     6.6            57.1
Permanent Ineff=
       F       F
Bank Sta=.9,6.6
XS Rating Curve= 0
Exp/Cntr=.3,.1

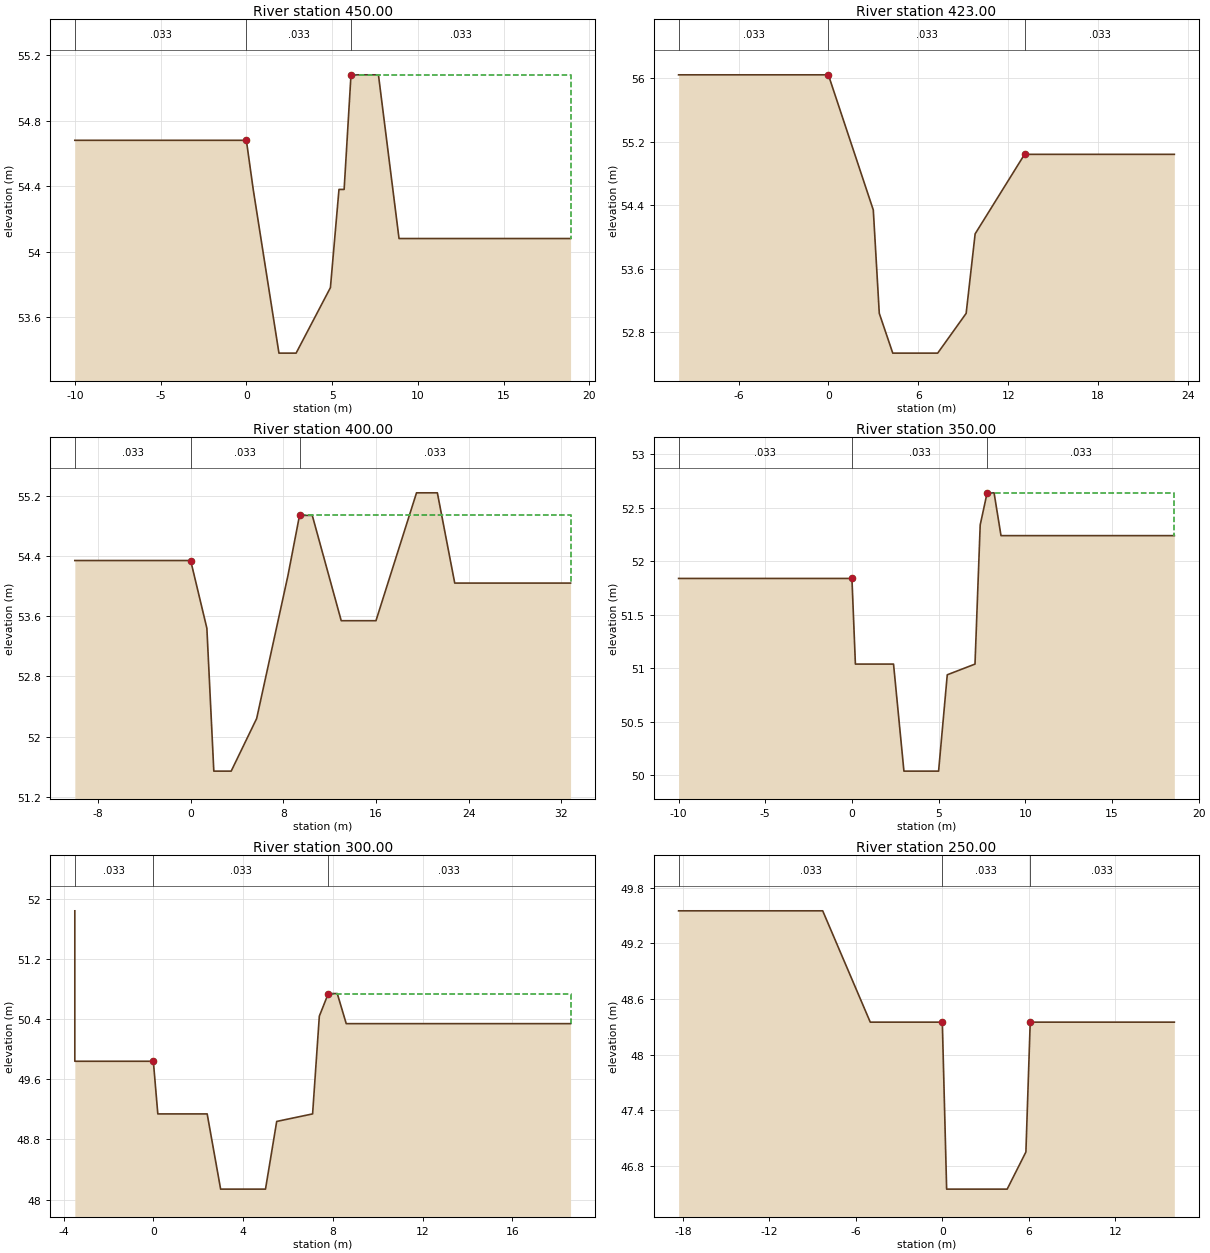
Type RM Length L Ch R = 1 ,450.00  ,27,27,27
BEGIN DESCRIPTION:
9
END DESCRIPTION:
#Sta/Elev= 12
     -10   54.68       0   54.68      .4   54.38     1.9   53.38     2.9   53.38
     4.9   53.78     5.4   54.38     5.7   54.38     6.1   55.08     7.7   55.08
     8.9   54.08    18.9   54.08
#Mann= 3 , 0 , 0
     -10    .033       0       0    .033       0     6.1    .033       0
#XS Ineff= 2 , 0
               0   54.68     6.1           55.08
Permanent Ineff=
       F       F
Bank Sta=0,6.1
XS Rating Curve= 0
Exp/Cntr=.3,.1

Type RM Length L Ch R = 1 ,423.00  ,23,23,23
BEGIN DESCRIPTION:
8.023
END DESCRIPTION:
#Sta/Elev= 10
     -10   56.04       0   56.04       3   54.34     3.4   53.04     4.3   52.54
     7.3   52.54     9.2   53.04     9.8   54.04    13.1   55.04    23.1   55.04
#Mann= 3 , 0 , 0
     -10    .033       0       0    .033       0    13.1    .033       0
#XS Ineff= 2 , 0
               0   56.04    13.1           55.04
Permanent Ineff=
       F       F
Bank Sta=0,13.1
XS Rating Curve= 0
Exp/Cntr=.3,.1

Type RM Length L Ch R = 1 ,400.00  ,50,50,50
BEGIN DESCRIPTION:
8
END DESCRIPTION:
#Sta/Elev= 15
     -10   54.34       0   54.34     1.4   53.44       2   51.54     3.5   51.54
     5.7   52.24     8.4   54.14     9.4   54.94    10.5   54.94      13   53.54
      16   53.54    19.5   55.24    21.3   55.24    22.8   54.04    32.8   54.04
#Mann= 3 , 0 , 0
     -10    .033       0       0    .033       0     9.4    .033       0
#XS Ineff= 2 , 0
               0   54.34     9.4           54.94
Permanent Ineff=
       F       F
Bank Sta=0,9.4
XS Rating Curve= 0
Exp/Cntr=.3,.1

Type RM Length L Ch R = 1 ,350.00  ,50,50,50
BEGIN DESCRIPTION:
7
END DESCRIPTION:
#Sta/Elev= 13
     -10   51.84       0   51.84      .2   51.04     2.4   51.04       3   50.04
       5   50.04     5.5   50.94     7.1   51.04     7.4   52.34     7.8   52.64
     8.2   52.64     8.6   52.24    18.6   52.24
#Mann= 3 , 0 , 0
     -10    .033       0       0    .033       0     7.8    .033       0
#XS Ineff= 2 , 0
               0   51.84     7.8           52.64
Permanent Ineff=
       F       F
Bank Sta=0,7.8
XS Rating Curve= 0
Exp/Cntr=.3,.1

Type RM Length L Ch R = 1 ,300.00  ,50,50,50
BEGIN DESCRIPTION:
6
END DESCRIPTION:
#Sta/Elev= 14
    -3.5   51.84    -3.5   49.84       0   49.84      .2   49.14     2.4   49.14
       3   48.14       5   48.14     5.5   49.04     7.1   49.14     7.4   50.44
     7.8   50.74     8.2   50.74     8.6   50.34    18.6   50.34
#Mann= 3 , 0 , 0
    -3.5    .033       0       0    .033       0     7.8    .033       0
#XS Ineff= 2 , 0
               0   49.84     7.8           50.74
Permanent Ineff=
       F       F
Bank Sta=0,7.8
XS Rating Curve= 0
Exp/Cntr=.3,.1

Type RM Length L Ch R = 1 ,250.00  ,50,50,50
BEGIN DESCRIPTION:
5
END DESCRIPTION:
#Sta/Elev= 10
   -18.3   49.55    -8.3   49.55      -5   48.35      -3   48.35       0   48.35
      .3   46.55     4.5   46.55     5.8   46.95     6.1   48.35    16.1   48.35
#Mann= 3 , 0 , 0
   -18.3    .033       0       0    .033       0     6.1    .033       0
#XS Ineff= 2 , 0
               0   48.35     6.1           48.35
Permanent Ineff=
       F       F
Bank Sta=0,6.1
XS Rating Curve= 0
Exp/Cntr=.3,.1

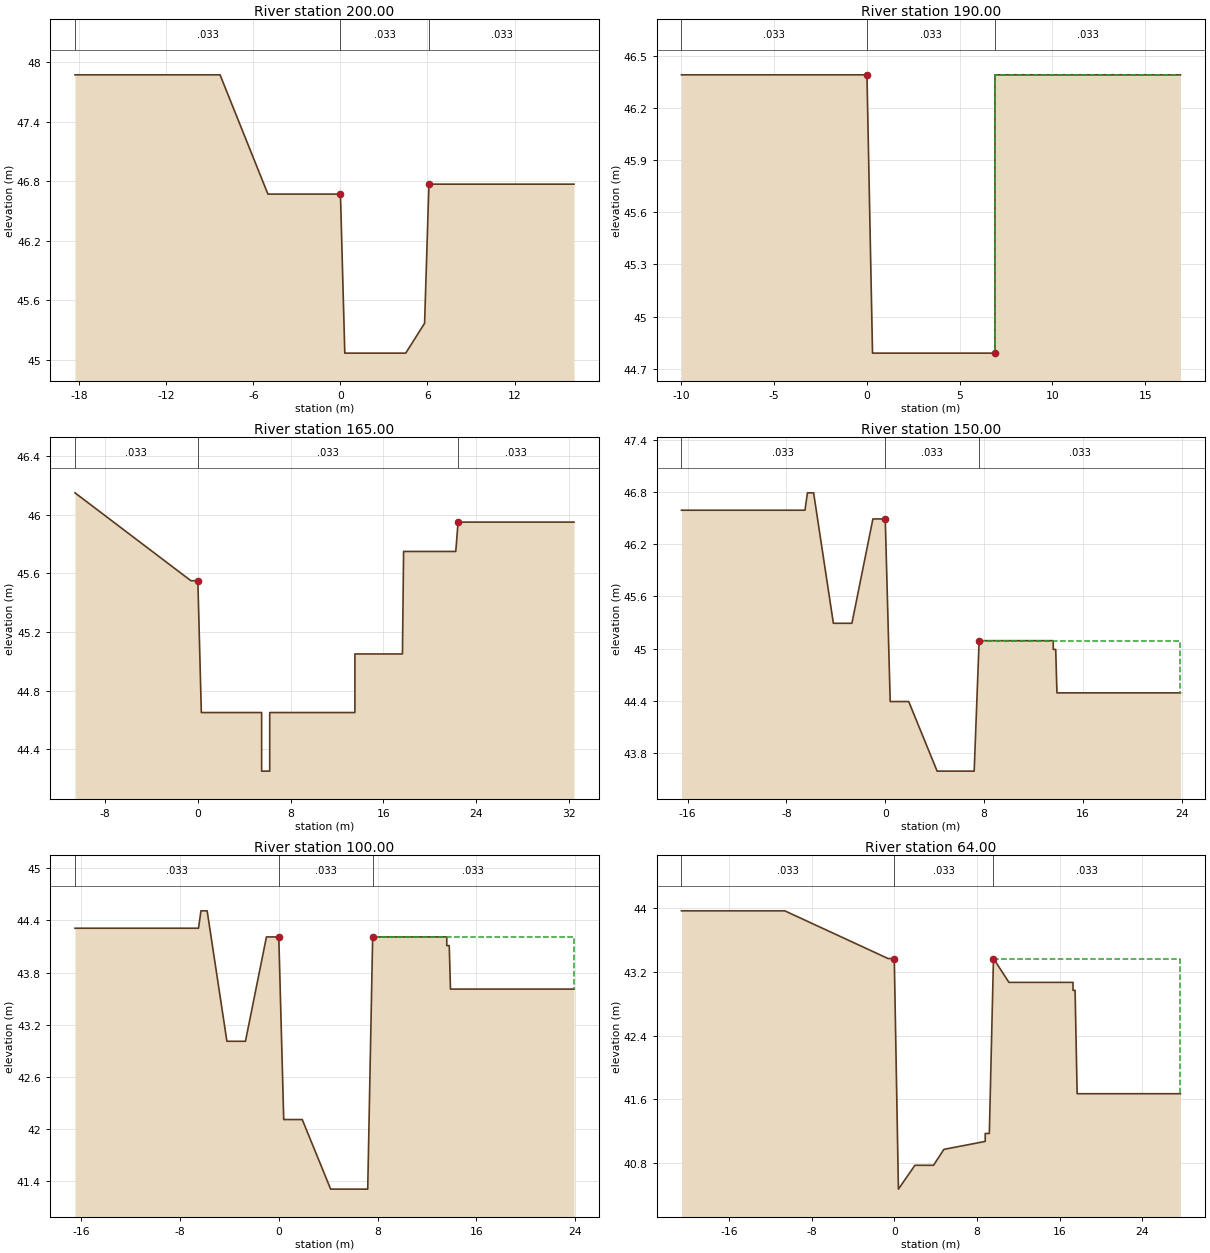
Type RM Length L Ch R = 1 ,200.00  ,10,10,10
BEGIN DESCRIPTION:
4
END DESCRIPTION:
#Sta/Elev= 10
   -18.3   47.87    -8.3   47.87      -5   46.67      -3   46.67       0   46.67
      .3   45.07     4.5   45.07     5.8   45.37     6.1   46.77    16.1   46.77
#Mann= 3 , 0 , 0
   -18.3    .033       0       0    .033       0     6.1    .033       0
#XS Ineff= 2 , 0
               0   46.67     6.1           46.77
Permanent Ineff=
       F       F
Bank Sta=0,6.1
XS Rating Curve= 0
Exp/Cntr=.3,.1

Type RM Length L Ch R = 1 ,190.00  ,25,25,25
BEGIN DESCRIPTION:
3.04
END DESCRIPTION:
#Sta/Elev= 6
     -10   46.39       0   46.39      .3   44.79     6.9   44.79     6.9   46.39
    16.9   46.39
#Mann= 3 , 0 , 0
     -10    .033       0       0    .033       0     6.9    .033       0
#XS Ineff= 2 , 0
               0   46.39     6.9           46.39
Permanent Ineff=
       F       F
Bank Sta=0,6.9
XS Rating Curve= 0
Exp/Cntr=.3,.1

Type RM Length L Ch R = 1 ,165.00  ,15,15,15
BEGIN DESCRIPTION:
3.015
END DESCRIPTION:
#Sta/Elev= 17
   -10.6   46.15    -5.6   45.85     -.6   45.55       0   45.55      .3   44.65
     5.5   44.65     5.5   44.25     6.2   44.25     6.2   44.65    12.7   44.65
   13.55   44.65   13.55   45.05   17.65   45.05   17.75   45.75   22.25   45.75
   22.45   45.95   32.45   45.95
#Mann= 3 , 0 , 0
   -10.6    .033       0       0    .033       0   22.45    .033       0
#XS Ineff= 2 , 0
               0   45.55   22.45           45.95
Permanent Ineff=
       F       F
Bank Sta=0,22.45
XS Rating Curve= 0
Exp/Cntr=.3,.1

Type RM Length L Ch R = 1 ,150.00  ,50,50,50
BEGIN DESCRIPTION:
3
END DESCRIPTION:
#Sta/Elev= 18
   -16.5   46.59    -6.5   46.59    -6.3   46.79    -5.8   46.79    -4.2   45.29
    -2.7   45.29      -1   46.49       0   46.49      .4   44.39     1.9   44.39
     4.2   43.59     7.2   43.59     7.6   45.09    13.6   45.09    13.6   44.99
    13.8   44.99    13.9   44.49    23.9   44.49
#Mann= 3 , 0 , 0
   -16.5    .033       0       0    .033       0     7.6    .033       0
#XS Ineff= 2 , 0
               0   46.49     7.6           45.09
Permanent Ineff=
       F       F
Bank Sta=0,7.6
XS Rating Curve= 0
Exp/Cntr=.3,.1

Type RM Length L Ch R = 1 ,100.00  ,36,36,36
BEGIN DESCRIPTION:
2
END DESCRIPTION:
#Sta/Elev= 18
   -16.5   44.31    -6.5   44.31    -6.3   44.51    -5.8   44.51    -4.2   43.01
    -2.7   43.01      -1   44.21       0   44.21      .4   42.11     1.9   42.11
     4.2   41.31     7.2   41.31     7.6   44.21    13.6   44.21    13.6   44.11
    13.8   44.11    13.9   43.61    23.9   43.61
#Mann= 3 , 0 , 0
   -16.5    .033       0       0    .033       0     7.6    .033       0
#XS Ineff= 2 , 0
               0   44.21     7.6           44.21
Permanent Ineff=
       F       F
Bank Sta=0,7.6
XS Rating Curve= 0
Exp/Cntr=.3,.1

Type RM Length L Ch R = 1 ,64.00   ,14,14,14
BEGIN DESCRIPTION:
1.014
END DESCRIPTION:
#Sta/Elev= 19
   -20.6   43.97   -10.6   43.97    -5.6   43.67     -.6   43.37       0   43.37
      .4   40.47       2   40.77     3.8   40.77     4.8   40.97     8.8   41.07
     8.8   41.17     9.2   41.17     9.6   43.37    11.1   43.07    17.3   43.07
    17.3   42.97    17.5   42.97    17.7   41.67    27.7   41.67
#Mann= 3 , 0 , 0
   -20.6    .033       0       0    .033       0     9.6    .033       0
#XS Ineff= 2 , 0
               0   43.37     9.6           43.37
Permanent Ineff=
       F       F
Bank Sta=0,9.6
XS Rating Curve= 0
Exp/Cntr=.3,.1

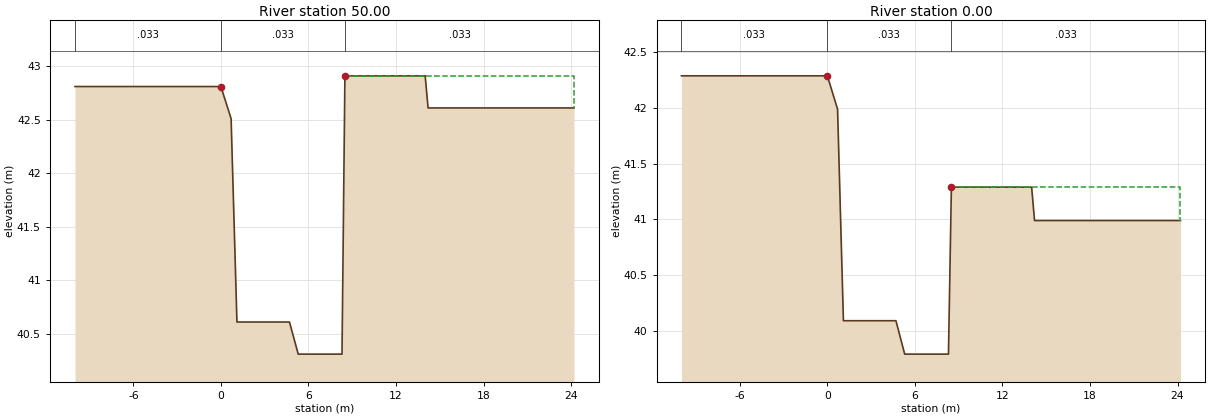
Type RM Length L Ch R = 1 ,50.00   ,50,50,50
BEGIN DESCRIPTION:
1
END DESCRIPTION:
#Sta/Elev= 11
     -10   42.81       0   42.81      .7   42.51     1.1   40.61     4.7   40.61
     5.3   40.31     8.3   40.31     8.5   42.91      14   42.91    14.2   42.61
    24.2   42.61
#Mann= 3 , 0 , 0
     -10    .033       0       0    .033       0     8.5    .033       0
#XS Ineff= 2 , 0
               0   42.81     8.5           42.91
Permanent Ineff=
       F       F
Bank Sta=0,8.5
XS Rating Curve= 0
Exp/Cntr=.3,.1

Type RM Length L Ch R = 1 ,0.00    ,0,0,0
BEGIN DESCRIPTION:
0
END DESCRIPTION:
#Sta/Elev= 11
     -10   42.29       0   42.29      .7   41.99     1.1   40.09     4.7   40.09
     5.3   39.79     8.3   39.79     8.5   41.29      14   41.29    14.2   40.99
    24.2   40.99
#Mann= 3 , 0 , 0
     -10    .033       0       0    .033       0     8.5    .033       0
#XS Ineff= 2 , 0
               0   42.29     8.5           41.29
Permanent Ineff=
       F       F
Bank Sta=0,8.5
XS Rating Curve= 0
Exp/Cntr=.3,.1

Chan Stop Cuts=-1