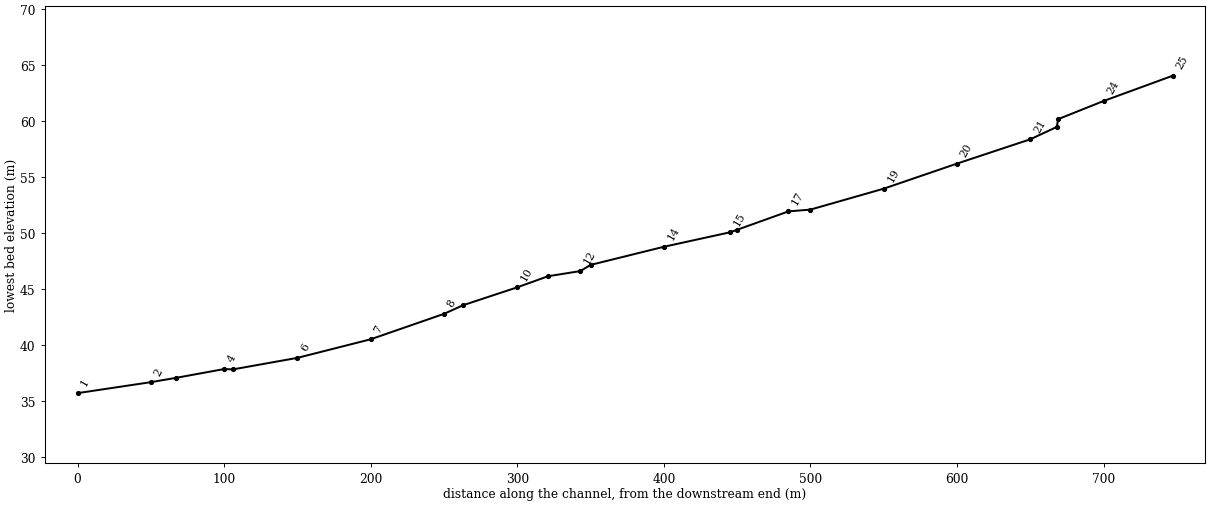
--- yanggi-ch.prj (project) ---

Proj Title=yanggi-ch
Current Plan=p01
Default Exp/Contr=.3,.1
SI Units
Geom File=g01
Flow File=f01
Plan File=p01
Y Axis Title=Elevation
X Axis Title(PF)=Main Channel Distance
X Axis Title(XS)=Station
BEGIN DESCRIPTION:
           BACK WATER COMPUTATION
      APPLICATION OF HEC-2 BY Samju Construction Engineering
      ¾çÁöÃµ(¿ËÃµÀ¾): 30,50,80,100,150³âºóµµ °³¼öÀü
END DESCRIPTION:
DSS Export Rating Curves= 0
DSS Export Rating Curve Sorted= 0
DSS Export Volume Flow Curves= 0
DXF OffsetX= 0
DXF OffsetY= 0
DXF ScaleX= 1
DXF ScaleY= 10

--- yanggi-ch.p01 (plan) ---

Plan Title=Imported Plan 01
Version=Version 3.0.1  Mar 2001
Short Identifier=Imported Pla
Geom File=g01
Flow File=f01
Subcritical Flow
K Sum by GR= 0
Std Step Tol= 0.003
Critical Tol= 0.003
Num of Std Step Trials= 20
Max Error Tol= 0.1
Flow Tol Ratio= 0.001
Split Flow NTrial= 30
Split Flow Tol= 0.02
Split Flow Ratio= 0.02
Log Output Level= 0
Friction Slope Method= 1
Unsteady Friction Slope Method= 2
Parabolic Critical Depth
Global Vel Dist= 0 , 0 , 0
Global Log Level= 0
CheckData=True
Encroach Param=-1 ,0,0, 0
Computation Interval=1HOUR
Output Interval=1HOUR
Run HTab= 0
Run UNet= 0
Run PostProcess= 0
UNET Theta= 1
UNET ZTol= 0.02
UNET ZSATol= 0.1
UNET MxIter= 20
UNET MaxInSteps= 20
UNET DtIC= 0
UNET DtMin= 0
UNET MaxCRTS= 20
UNET WFStab= 2
UNET SFStab= 1
UNET WFX= 1
UNET SFX= 1
UNET Convert EG Bridges=-1
UNET Use Existing IB Tables=-1
Instantaneous Interval=1HOUR
Write IC File= 0
Write Velocity= 0
Write Detailed= 0

--- yanggi-ch.f01 (steady flow) ---

Flow Title=Imported Flow 01
Version=Version 3.0.1  Mar 2001
Number of Profiles= 5
Profile Names=PF 1,PF 2,PF 3,PF 4,PF 5
River Rch & RM=RIVER-1,Reach-1         ,25
     180     200     220     230     240
Boundary for River Rch & Prof#=RIVER-1,Reach-1         , 1
Up Type= 0
Dn Type= 3
Dn Slope=.0109
Boundary for River Rch & Prof#=RIVER-1,Reach-1         , 2
Up Type= 0
Dn Type= 3
Dn Slope=.0109
Boundary for River Rch & Prof#=RIVER-1,Reach-1         , 3
Up Type= 0
Dn Type= 3
Dn Slope=.0109
Boundary for River Rch & Prof#=RIVER-1,Reach-1         , 4
Up Type= 0
Dn Type= 3
Dn Slope=.0109
Boundary for River Rch & Prof#=RIVER-1,Reach-1         , 5
Up Type= 0
Dn Type= 3
Dn Slope=.0109
DSS Import GetInterval= 0
DSS Import GetPeak= 0
DSS Import FillOption= 0

--- yanggi-ch.g01 (geometry) ---

Geom Title=Imported Geom 01
Version=Version 3.0.1  Mar 2001

River Reach=RIVER-1         ,Reach-1
Reach XY= 2
              .5             .95              .5             .05

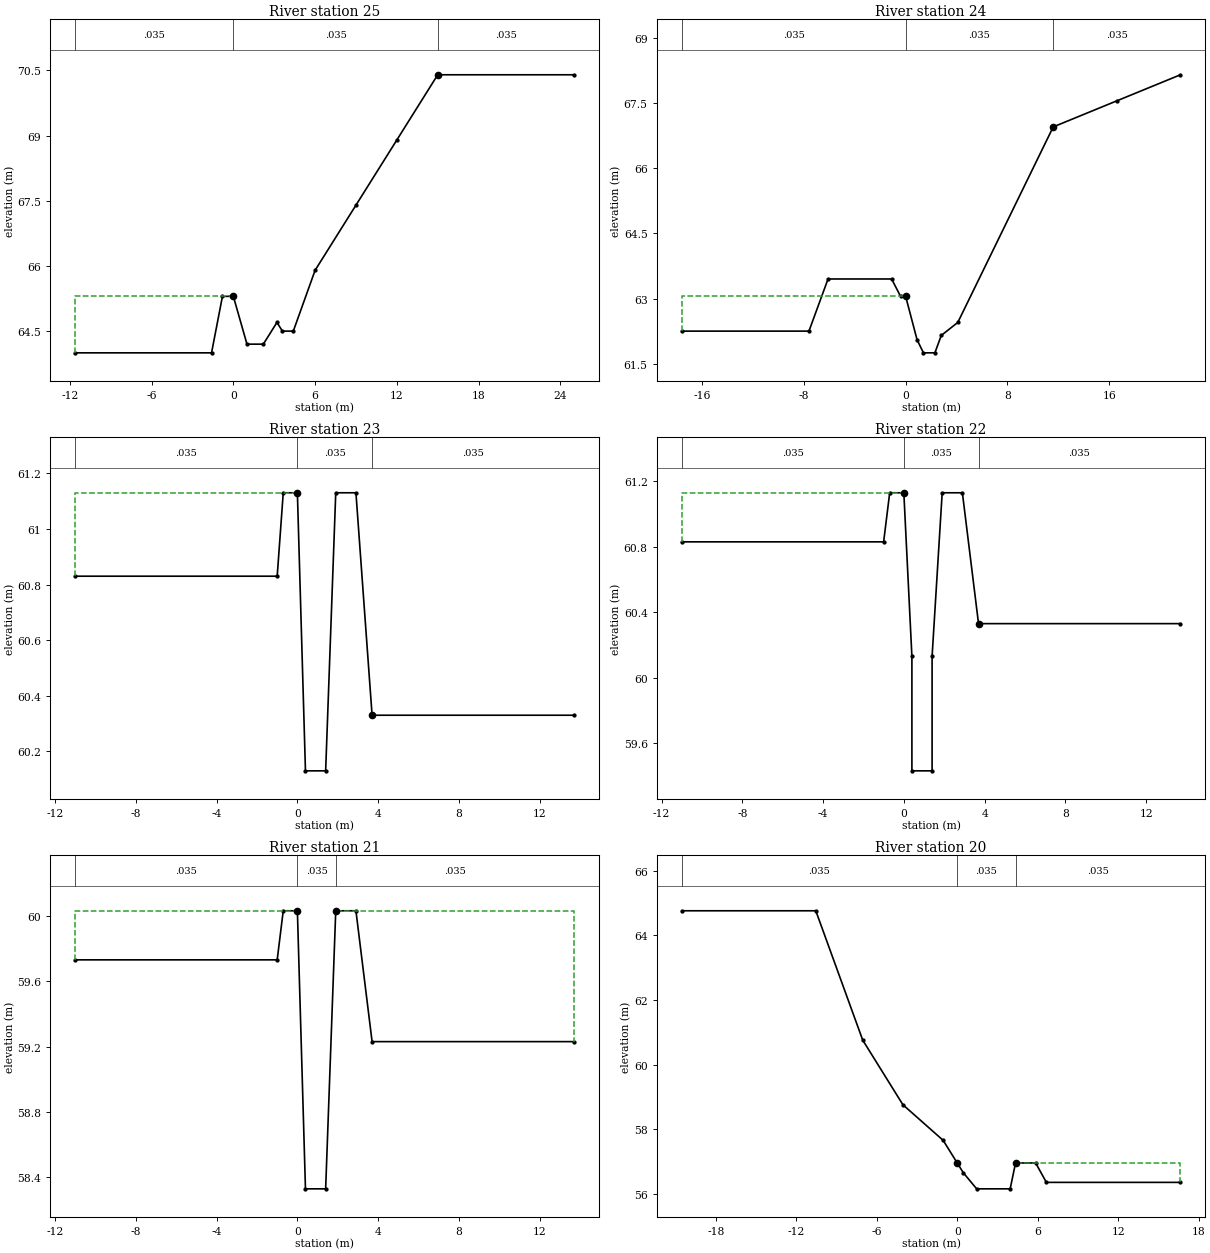
Type RM Length L Ch R = 1 ,25      ,47,47,47
BEGIN DESCRIPTION:
14.047
END DESCRIPTION:
#Sta/Elev= 14
   -11.6      64    -1.6      64     -.8    65.3       0    65.3       1    64.2
     2.2    64.2     3.2    64.7     3.6    64.5     4.4    64.5       6    65.9
       9    67.4      12    68.9      15    70.4      25    70.4
#Mann= 3 , 0 , 0
   -11.6    .035       0       0    .035       0      15    .035       0
#XS Ineff= 2 , 0
               0    65.3      15            70.4
Permanent Ineff=
       F       F
Bank Sta=0,15
XS Rating Curve= 0
Exp/Cntr=.3,.1

Type RM Length L Ch R = 1 ,24      ,31,31,31
BEGIN DESCRIPTION:
14
END DESCRIPTION:
#Sta/Elev= 14
   -17.6   62.25    -7.6   62.25    -6.1   63.45    -1.1   63.45     -.4   63.05
       0   63.05      .9   62.05     1.4   61.75     2.3   61.75     2.8   62.15
     4.1   62.45    11.6   66.95    16.6   67.55    21.6   68.15
#Mann= 3 , 0 , 0
   -17.6    .035       0       0    .035       0    11.6    .035       0
#XS Ineff= 2 , 0
               0   63.05    11.6           66.95
Permanent Ineff=
       F       F
Bank Sta=0,11.6
XS Rating Curve= 0
Exp/Cntr=.3,.1

Type RM Length L Ch R = 1 ,23      ,1,1,1
BEGIN DESCRIPTION:
13.019
END DESCRIPTION:
#Sta/Elev= 10
     -11   60.83      -1   60.83     -.7   61.13       0   61.13      .4   60.13
     1.4   60.13     1.9   61.13     2.9   61.13     3.7   60.33    13.7   60.33
#Mann= 3 , 0 , 0
     -11    .035       0       0    .035       0     3.7    .035       0
#XS Ineff= 2 , 0
               0   61.13     3.7           60.33
Permanent Ineff=
       F       F
Bank Sta=0,3.7
XS Rating Curve= 0
Exp/Cntr=.3,.1

Type RM Length L Ch R = 1 ,22      ,18,18,18
BEGIN DESCRIPTION:
13.018
END DESCRIPTION:
#Sta/Elev= 12
     -11   60.83      -1   60.83     -.7   61.13       0   61.13      .4   60.13
      .4   59.43     1.4   59.43     1.4   60.13     1.9   61.13     2.9   61.13
     3.7   60.33    13.7   60.33
#Mann= 3 , 0 , 0
     -11    .035       0       0    .035       0     3.7    .035       0
#XS Ineff= 2 , 0
               0   61.13     3.7           60.33
Permanent Ineff=
       F       F
Bank Sta=0,3.7
XS Rating Curve= 0
Exp/Cntr=.3,.1

Type RM Length L Ch R = 1 ,21      ,50,50,50
BEGIN DESCRIPTION:
13
END DESCRIPTION:
#Sta/Elev= 10
     -11   59.73      -1   59.73     -.7   60.03       0   60.03      .4   58.33
     1.4   58.33     1.9   60.03     2.9   60.03     3.7   59.23    13.7   59.23
#Mann= 3 , 0 , 0
     -11    .035       0       0    .035       0     1.9    .035       0
#XS Ineff= 2 , 0
               0   60.03     1.9           60.03
Permanent Ineff=
       F       F
Bank Sta=0,1.9
XS Rating Curve= 0
Exp/Cntr=.3,.1

Type RM Length L Ch R = 1 ,20      ,50,50,50
BEGIN DESCRIPTION:
12
END DESCRIPTION:
#Sta/Elev= 13
  -20.55   64.76  -10.55   64.76   -7.05   60.76   -4.05   58.76   -1.05   57.66
       0   56.96     .45   56.66    1.45   56.16    3.95   56.16    4.35   56.96
    5.85   56.96    6.65   56.36   16.65   56.36
#Mann= 3 , 0 , 0
  -20.55    .035       0       0    .035       0    4.35    .035       0
#XS Ineff= 2 , 0
               0   56.96    4.35           56.96
Permanent Ineff=
       F       F
Bank Sta=0,4.35
XS Rating Curve= 0
Exp/Cntr=.3,.1

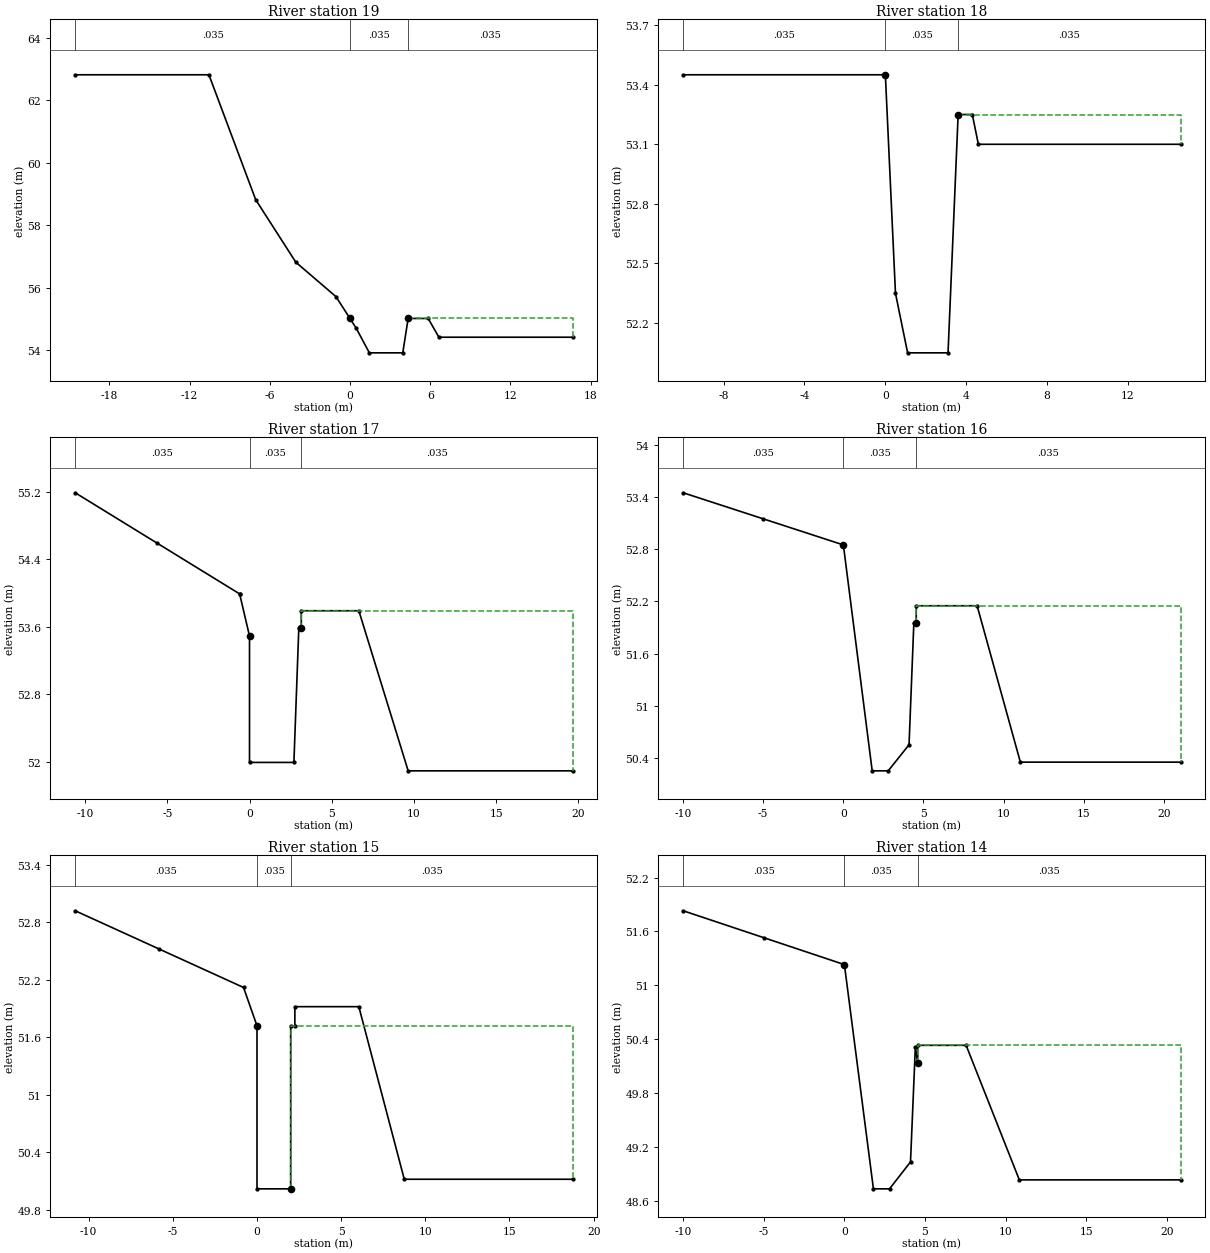
Type RM Length L Ch R = 1 ,19      ,50,50,50
BEGIN DESCRIPTION:
11
END DESCRIPTION:
#Sta/Elev= 13
  -20.55   62.82  -10.55   62.82   -7.05   58.82   -4.05   56.82   -1.05   55.72
       0   55.02     .45   54.72    1.45   53.92    3.95   53.92    4.35   55.02
    5.85   55.02    6.65   54.42   16.65   54.42
#Mann= 3 , 0 , 0
  -20.55    .035       0       0    .035       0    4.35    .035       0
#XS Ineff= 2 , 0
               0   55.02    4.35           55.02
Permanent Ineff=
       F       F
Bank Sta=0,4.35
XS Rating Curve= 0
Exp/Cntr=.3,.1

Type RM Length L Ch R = 1 ,18      ,15,15,15
BEGIN DESCRIPTION:
10
END DESCRIPTION:
#Sta/Elev= 9
     -10   53.45       0   53.45      .5   52.35     1.1   52.05     3.1   52.05
     3.6   53.25     4.3   53.25     4.6    53.1    14.6    53.1
#Mann= 3 , 0 , 0
     -10    .035       0       0    .035       0     3.6    .035       0
#XS Ineff= 2 , 0
               0   53.45     3.6           53.25
Permanent Ineff=
       F       F
Bank Sta=0,3.6
XS Rating Curve= 0
Exp/Cntr=.3,.1

Type RM Length L Ch R = 1 ,17      ,35,35,35
BEGIN DESCRIPTION:
9.035
END DESCRIPTION:
#Sta/Elev= 13
   -10.6   55.19    -5.6   54.59     -.6   53.99     -.6   53.99       0   53.49
       0   51.99     2.7   51.99       3   53.59    3.15   53.59    3.15   53.79
    6.65   53.79    9.65   51.89   19.65   51.89
#Mann= 3 , 0 , 0
   -10.6    .035       0       0    .035       0    3.15    .035       0
#XS Ineff= 2 , 0
               0   53.49    3.15           53.79
Permanent Ineff=
       F       F
Bank Sta=0,3.15
XS Rating Curve= 0
Exp/Cntr=.3,.1

Type RM Length L Ch R = 1 ,16      ,5,5,5
BEGIN DESCRIPTION:
9
END DESCRIPTION:
#Sta/Elev= 12
     -10   53.45      -5   53.15       0   52.85     1.8   50.25     2.8   50.25
     4.1   50.55     4.4   51.95    4.55   51.95    4.55   52.15    8.35   52.15
   11.05   50.35   21.05   50.35
#Mann= 3 , 0 , 0
     -10    .035       0       0    .035       0    4.55    .035       0
#XS Ineff= 2 , 0
               0   52.85    4.55           52.15
Permanent Ineff=
       F       F
Bank Sta=0,4.55
XS Rating Curve= 0
Exp/Cntr=.3,.1

Type RM Length L Ch R = 1 ,15      ,45,45,45
BEGIN DESCRIPTION:
8.045
END DESCRIPTION:
#Sta/Elev= 12
   -10.8   52.92    -5.8   52.52     -.8   52.12       0   51.72       0   50.02
       2   50.02       2   51.72    2.25   51.72    2.25   51.92    6.05   51.92
    8.75   50.12   18.75   50.12
#Mann= 3 , 0 , 0
   -10.8    .035       0       0    .035       0       2    .035       0
#XS Ineff= 2 , 0
               0   51.72       2           51.72
Permanent Ineff=
       F       F
Bank Sta=0,2
XS Rating Curve= 0
Exp/Cntr=.3,.1

Type RM Length L Ch R = 1 ,14      ,50,50,50
BEGIN DESCRIPTION:
8
END DESCRIPTION:
#Sta/Elev= 12
     -10   51.83      -5   51.53       0   51.23     1.8   48.73     2.8   48.73
     4.1   49.03     4.4   50.31    4.55   50.13    4.55   50.33    7.55   50.33
   10.85   48.83   20.85   48.83
#Mann= 3 , 0 , 0
     -10    .035       0       0    .035       0    4.55    .035       0
#XS Ineff= 2 , 0
               0   51.23    4.55           50.33
Permanent Ineff=
       F       F
Bank Sta=0,4.55
XS Rating Curve= 0
Exp/Cntr=.3,.1

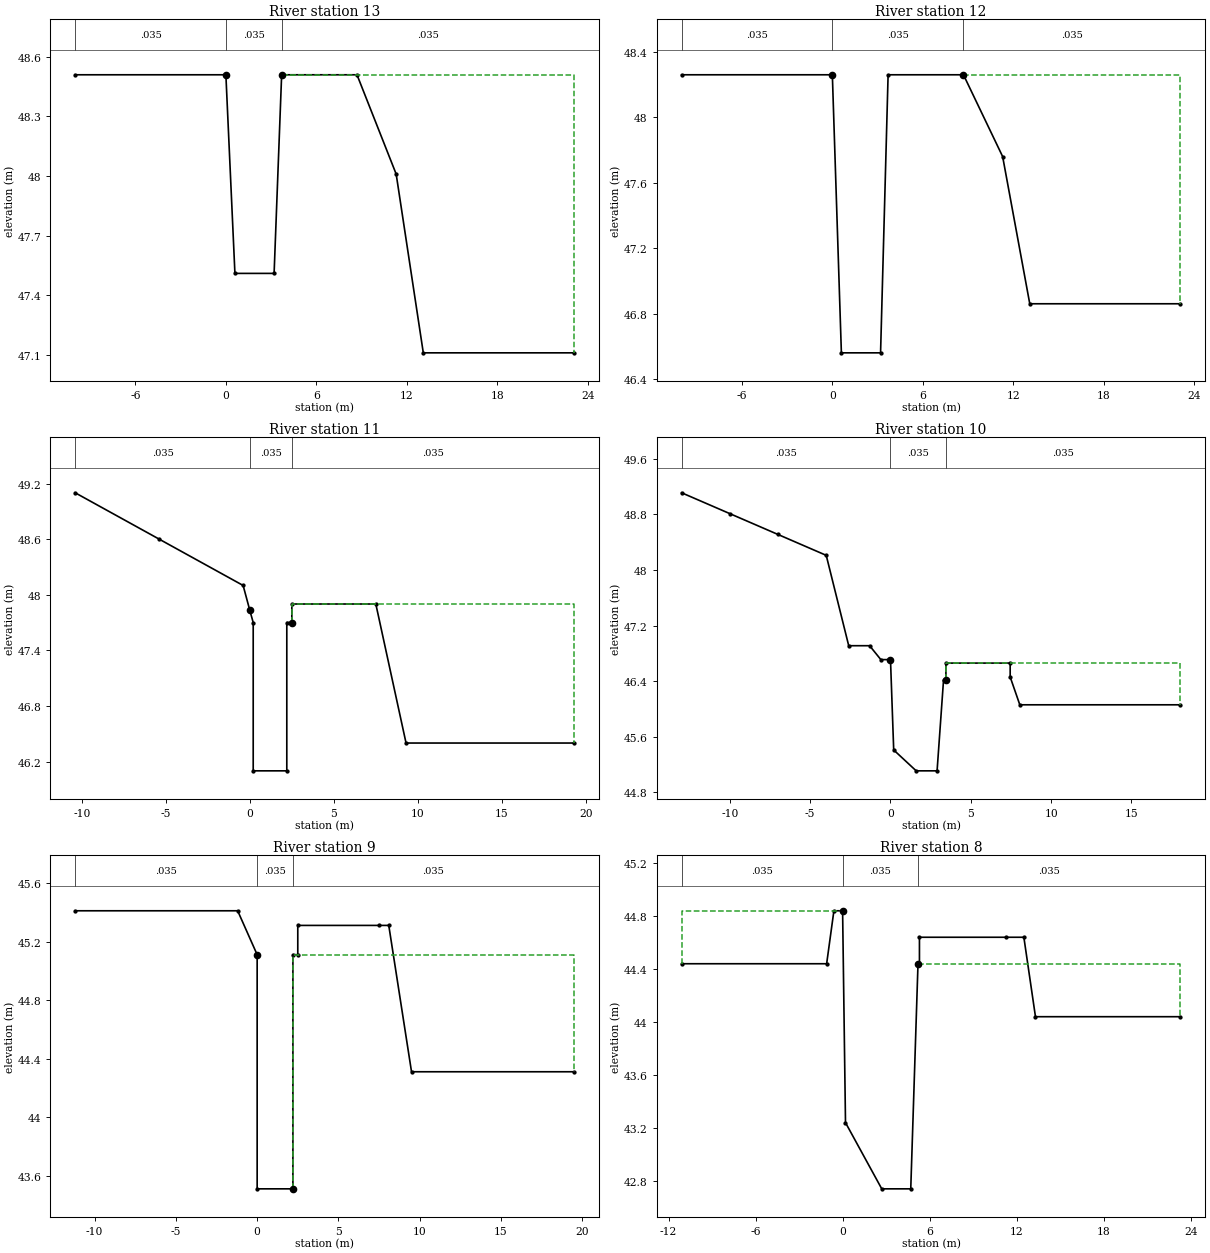
Type RM Length L Ch R = 1 ,13      ,7,7,7
BEGIN DESCRIPTION:
7
END DESCRIPTION:
#Sta/Elev= 9
     -10   48.51       0   48.51      .6   47.51     3.2   47.51     3.7   48.51
     8.7   48.51    11.3   48.01    13.1   47.11    23.1   47.11
#Mann= 3 , 0 , 0
     -10    .035       0       0    .035       0     3.7    .035       0
#XS Ineff= 2 , 0
               0   48.51     3.7           48.51
Permanent Ineff=
       F       F
Bank Sta=0,3.7
XS Rating Curve= 0
Exp/Cntr=.3,.1

Type RM Length L Ch R = 1 ,12      ,22,22,22
BEGIN DESCRIPTION:
6.043
END DESCRIPTION:
#Sta/Elev= 9
     -10   48.26       0   48.26      .6   46.56     3.2   46.56     3.7   48.26
     8.7   48.26    11.3   47.76    13.1   46.86    23.1   46.86
#Mann= 3 , 0 , 0
     -10    .035       0       0    .035       0     8.7    .035       0
#XS Ineff= 2 , 0
               0   48.26     8.7           48.26
Permanent Ineff=
       F       F
Bank Sta=0,8.7
XS Rating Curve= 0
Exp/Cntr=.3,.1

Type RM Length L Ch R = 1 ,11      ,21,21,21
BEGIN DESCRIPTION:
6.021
END DESCRIPTION:
#Sta/Elev= 13
   -10.4    49.1    -5.4    48.6     -.4    48.1       0   47.83      .2    47.7
      .2    46.1     2.2    46.1     2.2    47.7     2.5    47.7     2.5    47.9
     7.5    47.9     9.3    46.4    19.3    46.4
#Mann= 3 , 0 , 0
   -10.4    .035       0       0    .035       0     2.5    .035       0
#XS Ineff= 2 , 0
               0   47.83     2.5            47.9
Permanent Ineff=
       F       F
Bank Sta=0,2.5
XS Rating Curve= 0
Exp/Cntr=.3,.1

Type RM Length L Ch R = 1 ,10      ,37,37,37
BEGIN DESCRIPTION:
6
END DESCRIPTION:
#Sta/Elev= 18
     -13   49.11     -10   48.81      -7   48.51      -4   48.21    -2.6   46.91
    -1.3   46.91     -.6   46.71       0   46.71      .2   45.41     1.6   45.11
     2.9   45.11     3.3   46.41    3.45   46.41    3.45   46.66    7.45   46.66
    7.45   46.46    8.05   46.06   18.05   46.06
#Mann= 3 , 0 , 0
     -13    .035       0       0    .035       0    3.45    .035       0
#XS Ineff= 2 , 0
               0   46.71    3.45           46.66
Permanent Ineff=
       F       F
Bank Sta=0,3.45
XS Rating Curve= 0
Exp/Cntr=.3,.1

Type RM Length L Ch R = 1 ,9       ,13,13,13
BEGIN DESCRIPTION:
5.013
END DESCRIPTION:
#Sta/Elev= 12
   -11.2   45.41    -1.2   45.41       0   45.11       0   43.51     2.2   43.51
     2.2   45.11     2.5   45.11     2.5   45.31     7.5   45.31     8.1   45.31
     9.5   44.31    19.5   44.31
#Mann= 3 , 0 , 0
   -11.2    .035       0       0    .035       0     2.2    .035       0
#XS Ineff= 2 , 0
               0   45.11     2.2           45.11
Permanent Ineff=
       F       F
Bank Sta=0,2.2
XS Rating Curve= 0
Exp/Cntr=.3,.1

Type RM Length L Ch R = 1 ,8       ,50,50,50
BEGIN DESCRIPTION:
5
END DESCRIPTION:
#Sta/Elev= 14
   -11.1   44.44    -1.1   44.44     -.6   44.84       0   44.84      .2   43.24
     2.7   42.74     4.7   42.74     5.2   44.44     5.3   44.44     5.3   44.64
    11.3   44.64    12.5   44.64    13.3   44.04    23.3   44.04
#Mann= 3 , 0 , 0
   -11.1    .035       0       0    .035       0     5.2    .035       0
#XS Ineff= 2 , 0
               0   44.84     5.2           44.44
Permanent Ineff=
       F       F
Bank Sta=0,5.2
XS Rating Curve= 0
Exp/Cntr=.3,.1

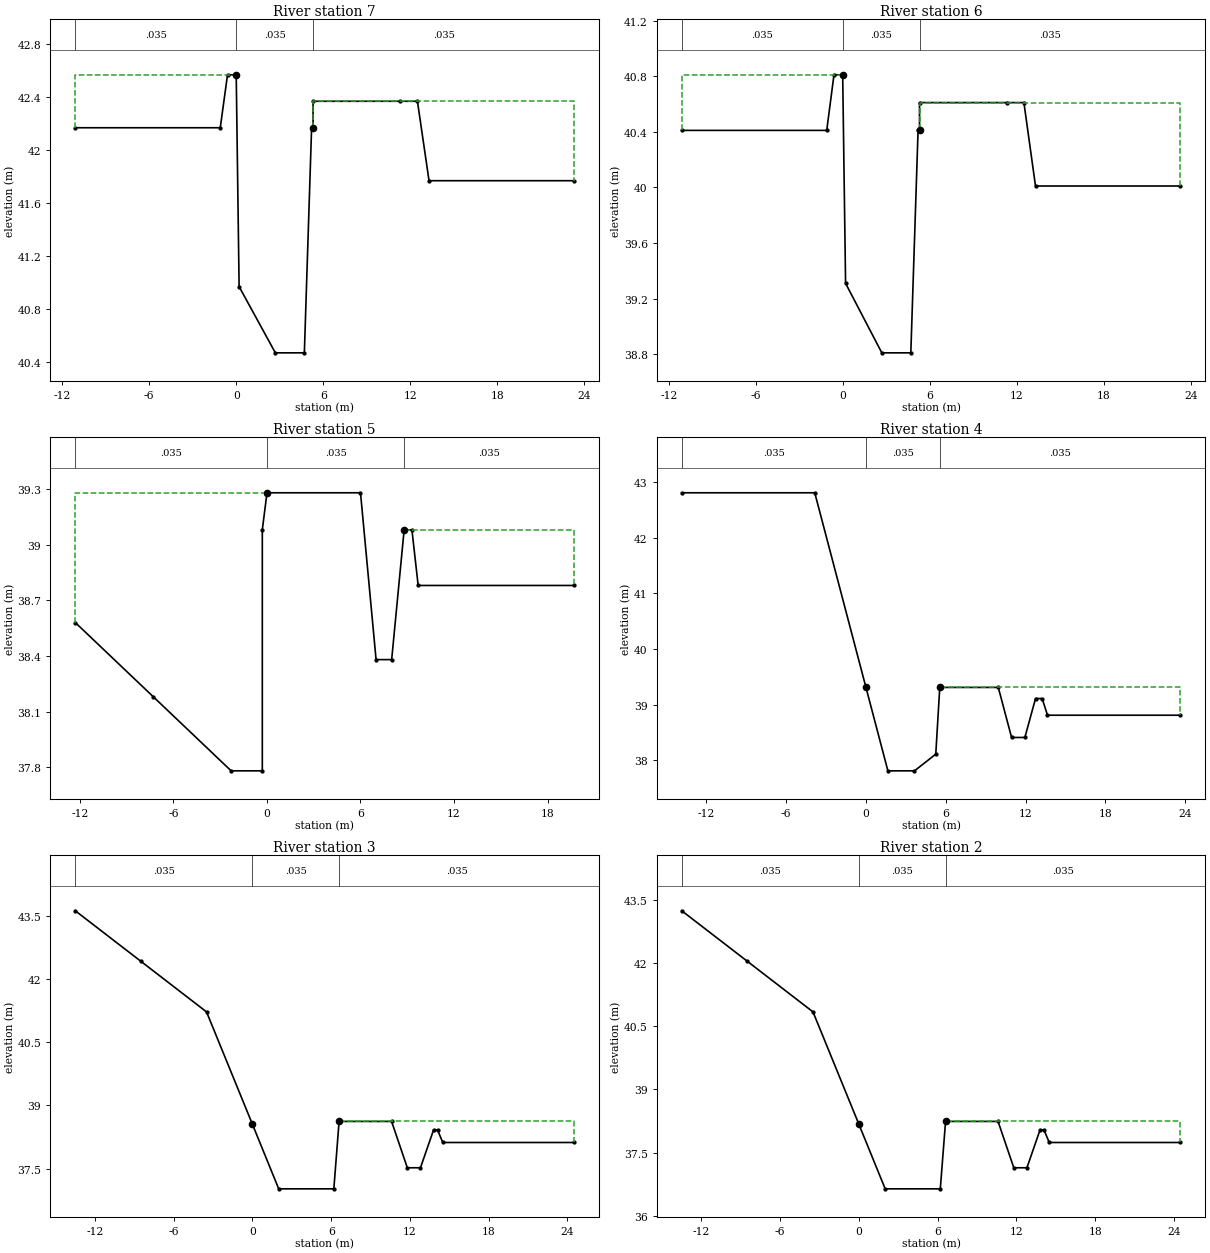
Type RM Length L Ch R = 1 ,7       ,50,50,50
BEGIN DESCRIPTION:
4
END DESCRIPTION:
#Sta/Elev= 14
   -11.1   42.17    -1.1   42.17     -.6   42.57       0   42.57      .2   40.97
     2.7   40.47     4.7   40.47     5.2   42.17     5.3   42.17     5.3   42.37
    11.3   42.37    12.5   42.37    13.3   41.77    23.3   41.77
#Mann= 3 , 0 , 0
   -11.1    .035       0       0    .035       0     5.3    .035       0
#XS Ineff= 2 , 0
               0   42.57     5.3           42.37
Permanent Ineff=
       F       F
Bank Sta=0,5.3
XS Rating Curve= 0
Exp/Cntr=.3,.1

Type RM Length L Ch R = 1 ,6       ,44,44,44
BEGIN DESCRIPTION:
3
END DESCRIPTION:
#Sta/Elev= 14
   -11.1   40.41    -1.1   40.41     -.6   40.81       0   40.81      .2   39.31
     2.7   38.81     4.7   38.81     5.2   40.41     5.3   40.41     5.3   40.61
    11.3   40.61    12.5   40.61    13.3   40.01    23.3   40.01
#Mann= 3 , 0 , 0
   -11.1    .035       0       0    .035       0     5.3    .035       0
#XS Ineff= 2 , 0
               0   40.81     5.3           40.61
Permanent Ineff=
       F       F
Bank Sta=0,5.3
XS Rating Curve= 0
Exp/Cntr=.3,.1

Type RM Length L Ch R = 1 ,5       ,6,6,6
BEGIN DESCRIPTION:
2.006
END DESCRIPTION:
#Sta/Elev= 13
   -12.3   38.58    -7.3   38.18    -2.3   37.78     -.3   37.78     -.3   39.08
       0   39.28       6   39.28       7   38.38       8   38.38     8.8   39.08
     9.3   39.08     9.7   38.78    19.7   38.78
#Mann= 3 , 0 , 0
   -12.3    .035       0       0    .035       0     8.8    .035       0
#XS Ineff= 2 , 0
               0   39.28     8.8           39.08
Permanent Ineff=
       F       F
Bank Sta=0,8.8
XS Rating Curve= 0
Exp/Cntr=.3,.1

Type RM Length L Ch R = 1 ,4       ,33,33,33
BEGIN DESCRIPTION:
2
END DESCRIPTION:
#Sta/Elev= 14
  -13.85   42.81   -3.85   42.81       0   39.31    1.65   37.81    3.65   37.81
    5.25   38.11    5.55   39.31    9.95   39.31   10.95   38.41   11.95   38.41
   12.75   39.11   13.25   39.11   13.65   38.81   23.65   38.81
#Mann= 3 , 0 , 0
  -13.85    .035       0       0    .035       0    5.55    .035       0
#XS Ineff= 2 , 0
               0   39.31    5.55           39.31
Permanent Ineff=
       F       F
Bank Sta=0,5.55
XS Rating Curve= 0
Exp/Cntr=.3,.1

Type RM Length L Ch R = 1 ,3       ,17,17,17
BEGIN DESCRIPTION:
0.017
END DESCRIPTION:
#Sta/Elev= 14
   -13.5   43.62    -8.5   42.42    -3.5   41.22       0   38.55       2   37.02
     6.2   37.02     6.6   38.62    10.6   38.62    11.8   37.52    12.8   37.52
    13.8   38.42    14.1   38.42    14.5   38.12    24.5   38.12
#Mann= 3 , 0 , 0
   -13.5    .035       0       0    .035       0     6.6    .035       0
#XS Ineff= 2 , 0
               0   38.55     6.6           38.62
Permanent Ineff=
       F       F
Bank Sta=0,6.6
XS Rating Curve= 0
Exp/Cntr=.3,.1

Type RM Length L Ch R = 1 ,2       ,50,50,50
BEGIN DESCRIPTION:
1
END DESCRIPTION:
#Sta/Elev= 14
   -13.5   43.24    -8.5   42.04    -3.5   40.84       0   38.17       2   36.64
     6.2   36.64     6.6   38.24    10.6   38.24    11.8   37.14    12.8   37.14
    13.8   38.04    14.1   38.04    14.5   37.74    24.5   37.74
#Mann= 3 , 0 , 0
   -13.5    .035       0       0    .035       0     6.6    .035       0
#XS Ineff= 2 , 0
               0   38.17     6.6           38.24
Permanent Ineff=
       F       F
Bank Sta=0,6.6
XS Rating Curve= 0
Exp/Cntr=.3,.1

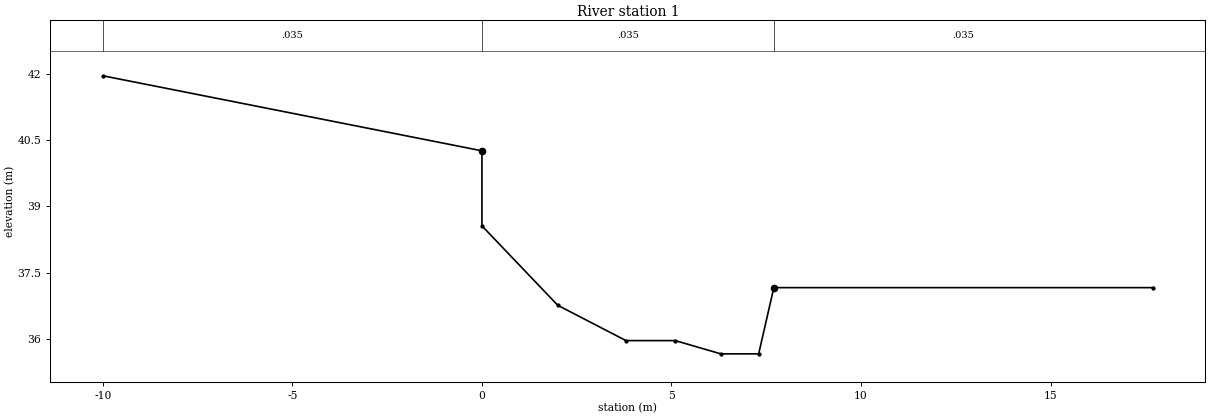
Type RM Length L Ch R = 1 ,1       ,0,0,0
BEGIN DESCRIPTION:
0
END DESCRIPTION:
#Sta/Elev= 10
     -10   41.96       0   40.26       0   38.56       2   36.76     3.8   35.96
     5.1   35.96     6.3   35.66     7.3   35.66     7.7   37.16    17.7   37.16
#Mann= 3 , 0 , 0
     -10    .035       0       0    .035       0     7.7    .035       0
#XS Ineff= 2 , 0
               0   40.26     7.7           37.16
Permanent Ineff=
       F       F
Bank Sta=0,7.7
XS Rating Curve= 0
Exp/Cntr=.3,.1

Chan Stop Cuts=-1