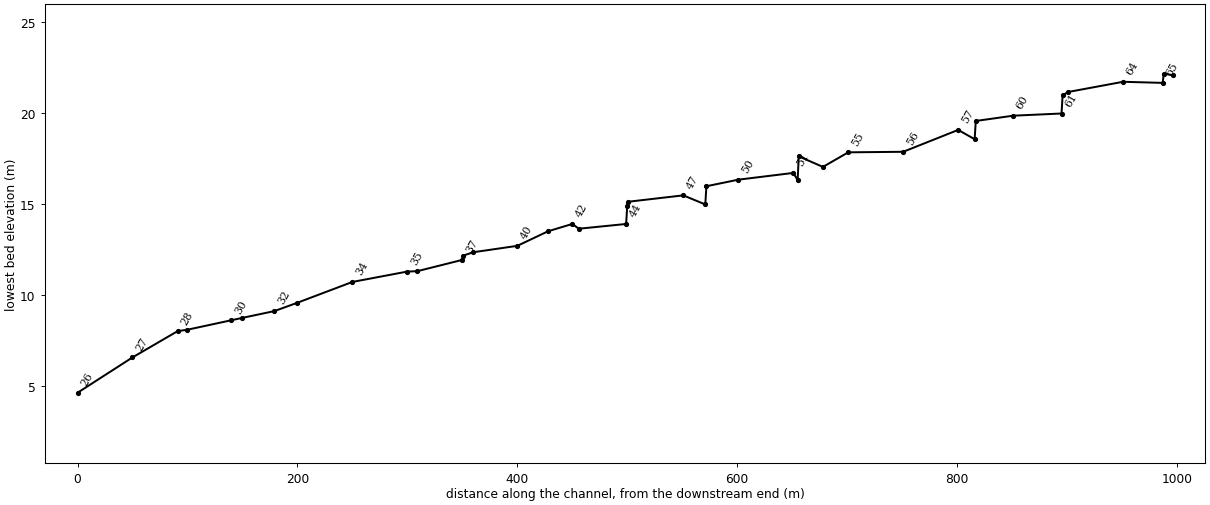
--- machawool-ch.prj (project) ---

Proj Title=machawool-ch
Current Plan=p01
Default Exp/Contr=.3,.1
SI Units
Geom File=g01
Flow File=f01
Plan File=p01
Y Axis Title=Elevation
X Axis Title(PF)=Main Channel Distance
X Axis Title(XS)=Station
BEGIN DESCRIPTION:
           BACK WATER COMPUTATION
      APPLICATION OF HEC-2 BY Samju Construction Engineering
    ¸¶Â÷¿ïÃµ(¿ËÃµÀ¾): 30,50,80,100,150³âºóµµ °³¼öÀü
END DESCRIPTION:
DSS Export Rating Curves= 0
DSS Export Rating Curve Sorted= 0
DSS Export Volume Flow Curves= 0
DXF OffsetX= 0
DXF OffsetY= 0
DXF ScaleX= 1
DXF ScaleY= 10

--- machawool-ch.p01 (plan) ---

Plan Title=Imported Plan 01
Version=Version 3.0.1  Mar 2001
Short Identifier=Imported Pla
Geom File=g01
Flow File=f01
Subcritical Flow
K Sum by GR= 0
Std Step Tol= 0.003
Critical Tol= 0.003
Num of Std Step Trials= 20
Max Error Tol= 0.1
Flow Tol Ratio= 0.001
Split Flow NTrial= 30
Split Flow Tol= 0.02
Split Flow Ratio= 0.02
Log Output Level= 0
Friction Slope Method= 1
Unsteady Friction Slope Method= 2
Parabolic Critical Depth
Global Vel Dist= 0 , 0 , 0
Global Log Level= 0
CheckData=True
Encroach Param=-1 ,0,0, 0
Computation Interval=1HOUR
Output Interval=1HOUR
Run HTab= 0
Run UNet= 0
Run PostProcess= 0
UNET Theta= 1
UNET ZTol= 0.02
UNET ZSATol= 0.1
UNET MxIter= 20
UNET MaxInSteps= 20
UNET DtIC= 0
UNET DtMin= 0
UNET MaxCRTS= 20
UNET WFStab= 2
UNET SFStab= 1
UNET WFX= 1
UNET SFX= 1
UNET Convert EG Bridges=-1
UNET Use Existing IB Tables=-1
Instantaneous Interval=1HOUR
Write IC File= 0
Write Velocity= 0
Write Detailed= 0

--- machawool-ch.f01 (steady flow) ---

Flow Title=Imported Flow 01
Version=Version 3.0.1  Mar 2001
Number of Profiles= 5
Profile Names=PF 1,PF 2,PF 3,PF 4,PF 5
River Rch & RM=RIVER-1,Reach-1         ,67
     180     200     220     230     240
Boundary for River Rch & Prof#=RIVER-1,Reach-1         , 1
Up Type= 0
Dn Type= 3
Dn Slope=.0109
Boundary for River Rch & Prof#=RIVER-1,Reach-1         , 2
Up Type= 0
Dn Type= 3
Dn Slope=.0109
Boundary for River Rch & Prof#=RIVER-1,Reach-1         , 3
Up Type= 0
Dn Type= 3
Dn Slope=.0109
Boundary for River Rch & Prof#=RIVER-1,Reach-1         , 4
Up Type= 0
Dn Type= 3
Dn Slope=.0109
Boundary for River Rch & Prof#=RIVER-1,Reach-1         , 5
Up Type= 0
Dn Type= 3
Dn Slope=.0109
DSS Import GetInterval= 0
DSS Import GetPeak= 0
DSS Import FillOption= 0

--- machawool-ch.g01 (geometry) ---

Geom Title=Imported Geom 01
Version=Version 3.0.1  Mar 2001

River Reach=RIVER-1         ,Reach-1
Reach XY= 2
              .5             .95              .5             .05

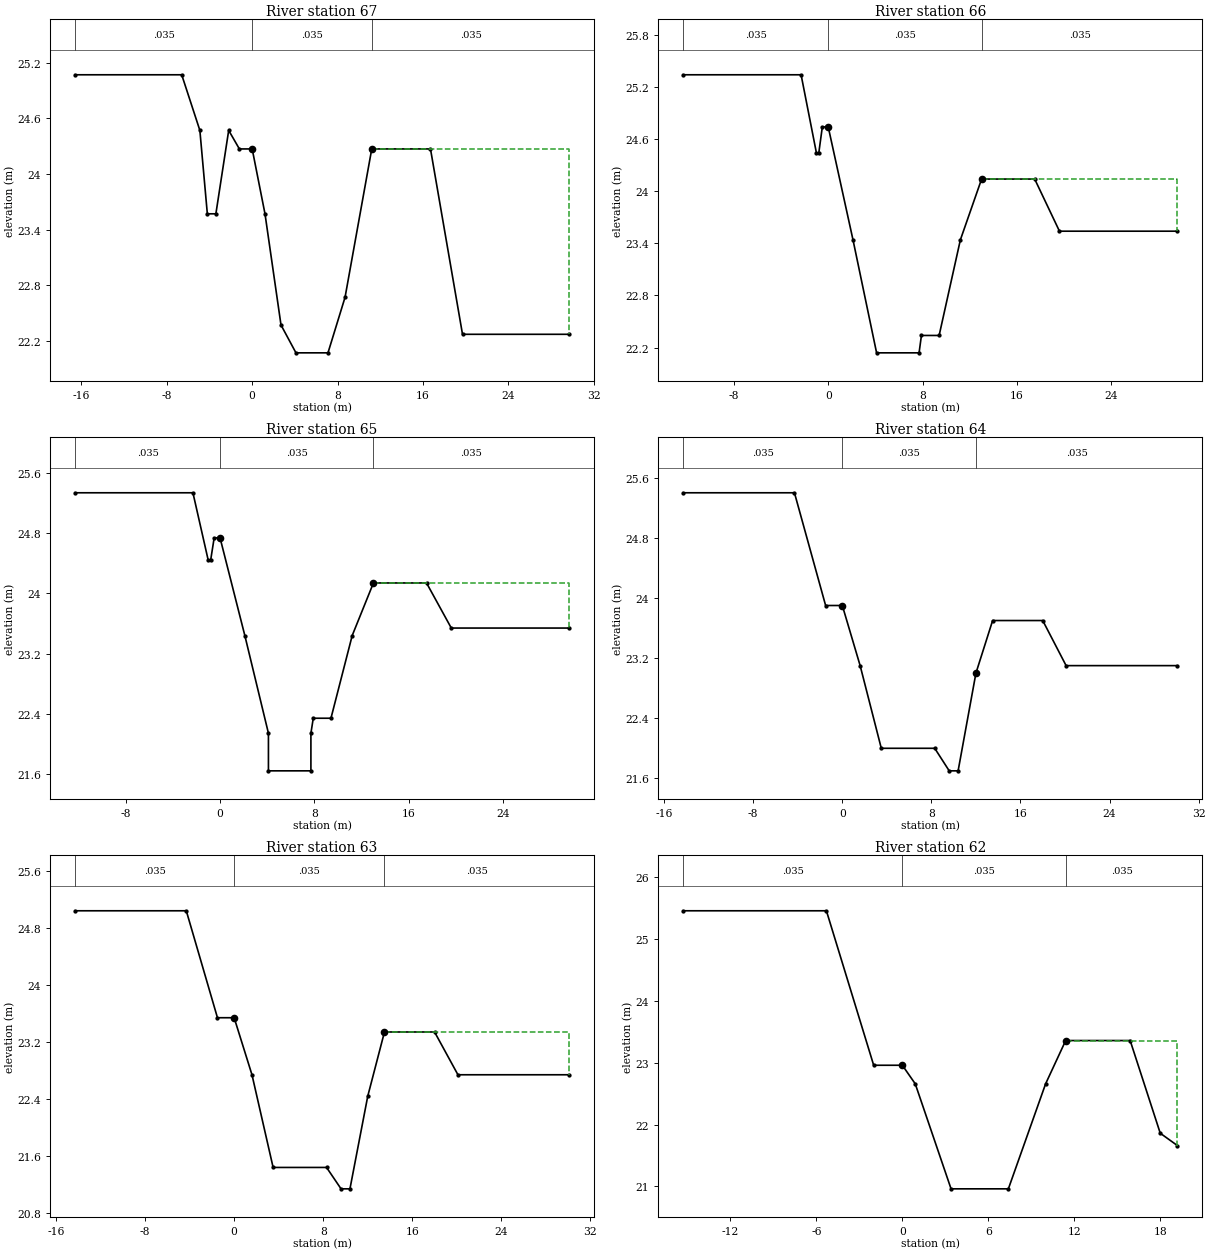
Type RM Length L Ch R = 1 ,67      ,8,8,8
BEGIN DESCRIPTION:
40.045
END DESCRIPTION:
#Sta/Elev= 17
   -16.6   25.07    -6.6   25.07    -4.9   24.47    -4.2   23.57    -3.4   23.57
    -2.2   24.47    -1.2   24.27       0   24.27     1.2   23.57     2.7   22.37
     4.1   22.07     7.1   22.07     8.7   22.67    11.2   24.27    16.7   24.27
    19.7   22.27    29.7   22.27
#Mann= 3 , 0 , 0
   -16.6    .035       0       0    .035       0    11.2    .035       0
#XS Ineff= 2 , 0
               0   24.27    11.2           24.27
Permanent Ineff=
       F       F
Bank Sta=0,11.2
XS Rating Curve= 0
Exp/Cntr=.3,.1

Type RM Length L Ch R = 1 ,66      ,1,1,1
BEGIN DESCRIPTION:
40.037
END DESCRIPTION:
#Sta/Elev= 16
   -12.3   25.34    -2.3   25.34      -1   24.44     -.8   24.44     -.5   24.74
       0   24.74     2.1   23.44     4.1   22.14     7.7   22.14     7.9   22.34
     9.4   22.34    11.2   23.44      13   24.14    17.5   24.14    19.6   23.54
    29.6   23.54
#Mann= 3 , 0 , 0
   -12.3    .035       0       0    .035       0      13    .035       0
#XS Ineff= 2 , 0
               0   24.74      13           24.14
Permanent Ineff=
       F       F
Bank Sta=0,13
XS Rating Curve= 0
Exp/Cntr=.3,.1

Type RM Length L Ch R = 1 ,65      ,36,36,36
BEGIN DESCRIPTION:
40.036
END DESCRIPTION:
#Sta/Elev= 18
   -12.3   25.34    -2.3   25.34      -1   24.44     -.8   24.44     -.5   24.74
       0   24.74     2.1   23.44     4.1   22.14     4.1   21.64     7.7   21.64
     7.7   22.14     7.9   22.34     9.4   22.34    11.2   23.44      13   24.14
    17.5   24.14    19.6   23.54    29.6   23.54
#Mann= 3 , 0 , 0
   -12.3    .035       0       0    .035       0      13    .035       0
#XS Ineff= 2 , 0
               0   24.74      13           24.14
Permanent Ineff=
       F       F
Bank Sta=0,13
XS Rating Curve= 0
Exp/Cntr=.3,.1

Type RM Length L Ch R = 1 ,64      ,50,50,50
BEGIN DESCRIPTION:
40
END DESCRIPTION:
#Sta/Elev= 14
   -14.3    25.4    -4.3    25.4    -1.5    23.9       0    23.9     1.6    23.1
     3.5      22     8.3      22     9.6    21.7    10.4    21.7      12      23
    13.5    23.7      18    23.7    20.1    23.1    30.1    23.1
#Mann= 3 , 0 , 0
   -14.3    .035       0       0    .035       0      12    .035       0
#XS Ineff= 2 , 0
               0    23.9      12              23
Permanent Ineff=
       F       F
Bank Sta=0,12
XS Rating Curve= 0
Exp/Cntr=.3,.1

Type RM Length L Ch R = 1 ,63      ,5,5,5
BEGIN DESCRIPTION:
39
END DESCRIPTION:
#Sta/Elev= 14
   -14.3   25.04    -4.3   25.04    -1.5   23.54       0   23.54     1.6   22.74
     3.5   21.44     8.3   21.44     9.6   21.14    10.4   21.14      12   22.44
    13.5   23.34      18   23.34    20.1   22.74    30.1   22.74
#Mann= 3 , 0 , 0
   -14.3    .035       0       0    .035       0    13.5    .035       0
#XS Ineff= 2 , 0
               0   23.54    13.5           23.34
Permanent Ineff=
       F       F
Bank Sta=0,13.5
XS Rating Curve= 0
Exp/Cntr=.3,.1

Type RM Length L Ch R = 1 ,62      ,1,1,1
BEGIN DESCRIPTION:
38.045
END DESCRIPTION:
#Sta/Elev= 12
   -15.3   25.46    -5.3   25.46      -2   22.96       0   22.96      .9   22.66
     3.4   20.96     7.4   20.96      10   22.66    11.4   23.36    15.9   23.36
      18   21.86    19.2   21.66
#Mann= 3 , 0 , 0
   -15.3    .035       0       0    .035       0    11.4    .035       0
#XS Ineff= 2 , 0
               0   22.96    11.4           23.36
Permanent Ineff=
       F       F
Bank Sta=0,11.4
XS Rating Curve= 0
Exp/Cntr=.3,.1

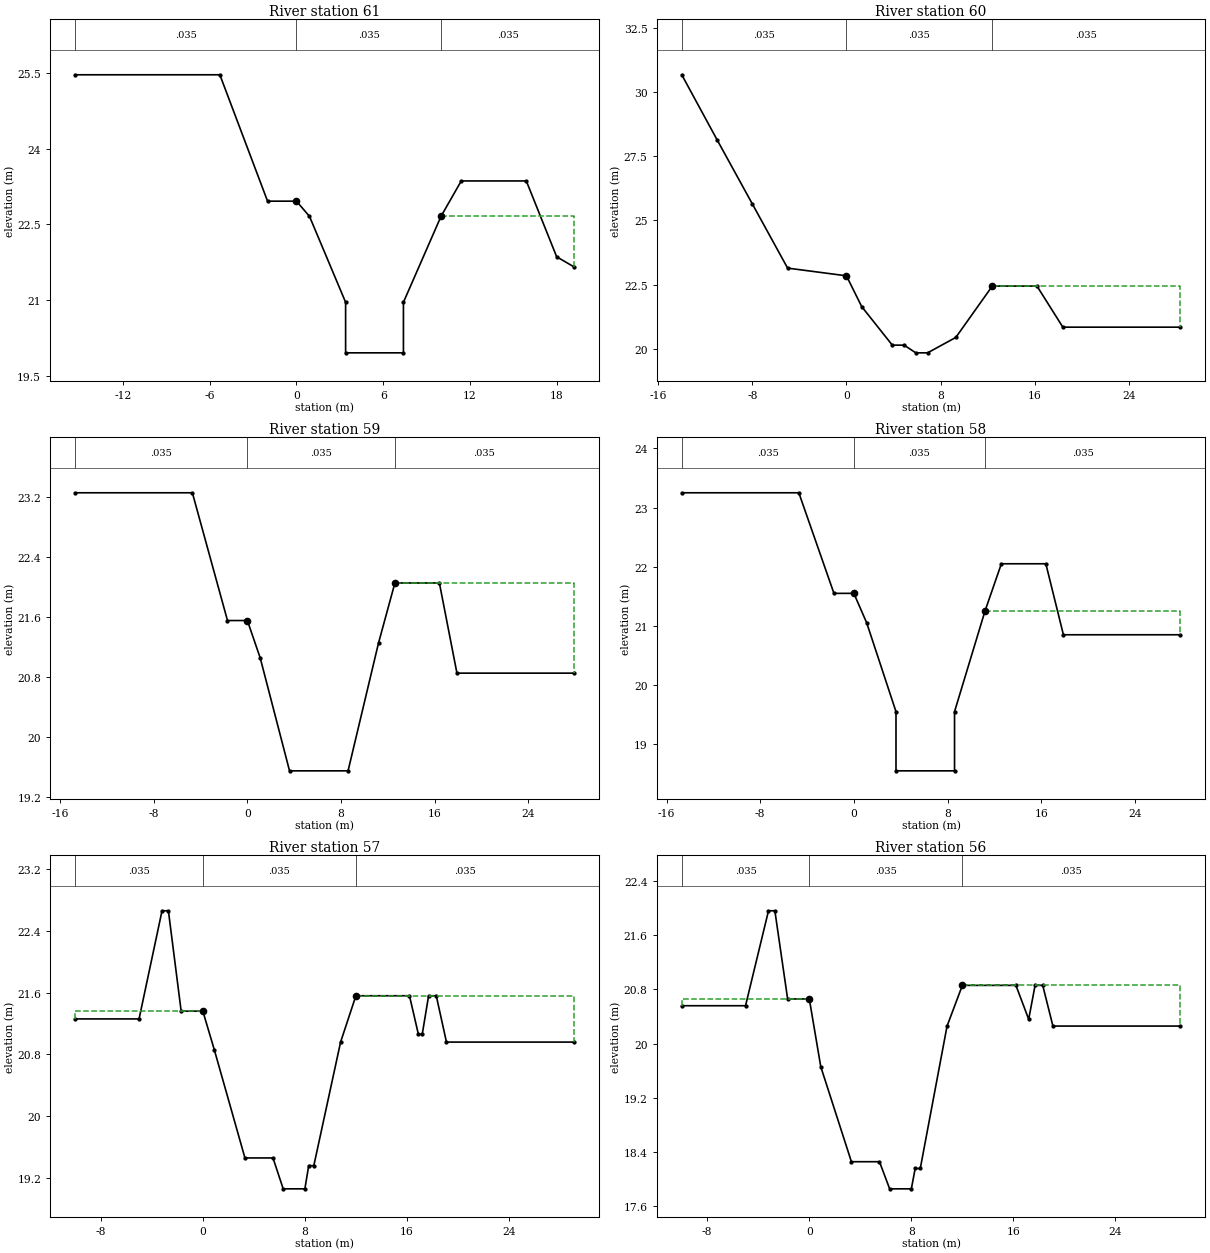
Type RM Length L Ch R = 1 ,61      ,44,44,44
BEGIN DESCRIPTION:
38.044
END DESCRIPTION:
#Sta/Elev= 14
   -15.3   25.46    -5.3   25.46      -2   22.96       0   22.96      .9   22.66
     3.4   20.96     3.4   19.96     7.4   19.96     7.4   20.96      10   22.66
    11.4   23.36    15.9   23.36      18   21.86    19.2   21.66
#Mann= 3 , 0 , 0
   -15.3    .035       0       0    .035       0      10    .035       0
#XS Ineff= 2 , 0
               0   22.96      10           22.66
Permanent Ineff=
       F       F
Bank Sta=0,10
XS Rating Curve= 0
Exp/Cntr=.3,.1

Type RM Length L Ch R = 1 ,60      ,34,34,34
BEGIN DESCRIPTION:
38
END DESCRIPTION:
#Sta/Elev= 15
     -14   30.67     -11   28.14      -8   25.64      -5   23.14       0   22.84
     1.3   21.64     3.9   20.14     4.9   20.14     5.9   19.84     6.9   19.84
     9.3   20.44    12.4   22.44    16.2   22.44    18.4   20.84    28.4   20.84
#Mann= 3 , 0 , 0
     -14    .035       0       0    .035       0    12.4    .035       0
#XS Ineff= 2 , 0
               0   22.84    12.4           22.44
Permanent Ineff=
       F       F
Bank Sta=0,12.4
XS Rating Curve= 0
Exp/Cntr=.3,.1

Type RM Length L Ch R = 1 ,59      ,1,1,1
BEGIN DESCRIPTION:
37.016
END DESCRIPTION:
#Sta/Elev= 12
   -14.7   23.25    -4.7   23.25    -1.7   21.55       0   21.55     1.1   21.05
     3.6   19.55     8.6   19.55    11.2   21.25    12.6   22.05    16.4   22.05
    17.9   20.85    27.9   20.85
#Mann= 3 , 0 , 0
   -14.7    .035       0       0    .035       0    12.6    .035       0
#XS Ineff= 2 , 0
               0   21.55    12.6           22.05
Permanent Ineff=
       F       F
Bank Sta=0,12.6
XS Rating Curve= 0
Exp/Cntr=.3,.1

Type RM Length L Ch R = 1 ,58      ,15,15,15
BEGIN DESCRIPTION:
37.015
END DESCRIPTION:
#Sta/Elev= 14
   -14.7   23.25    -4.7   23.25    -1.7   21.55       0   21.55     1.1   21.05
     3.6   19.55     3.6   18.55     8.6   18.55     8.6   19.55    11.2   21.25
    12.6   22.05    16.4   22.05    17.9   20.85    27.9   20.85
#Mann= 3 , 0 , 0
   -14.7    .035       0       0    .035       0    11.2    .035       0
#XS Ineff= 2 , 0
               0   21.55    11.2           21.25
Permanent Ineff=
       F       F
Bank Sta=0,11.2
XS Rating Curve= 0
Exp/Cntr=.3,.1

Type RM Length L Ch R = 1 ,57      ,50,50,50
BEGIN DESCRIPTION:
37
END DESCRIPTION:
#Sta/Elev= 22
     -10   21.26      -5   21.26    -3.2   22.66    -2.7   22.66    -1.7   21.36
       0   21.36      .9   20.86     3.3   19.46     5.5   19.46     6.3   19.06
       8   19.06     8.3   19.36     8.7   19.36    10.8   20.96      12   21.56
    16.2   21.56    16.9   21.06    17.2   21.06    17.7   21.56    18.3   21.56
    19.1   20.96    29.1   20.96
#Mann= 3 , 0 , 0
     -10    .035       0       0    .035       0      12    .035       0
#XS Ineff= 2 , 0
               0   21.36      12           21.56
Permanent Ineff=
       F       F
Bank Sta=0,12
XS Rating Curve= 0
Exp/Cntr=.3,.1

Type RM Length L Ch R = 1 ,56      ,50,50,50
BEGIN DESCRIPTION:
36
END DESCRIPTION:
#Sta/Elev= 21
     -10   20.56      -5   20.56    -3.2   21.96    -2.7   21.96    -1.7   20.66
       0   20.66      .9   19.66     3.3   18.26     5.5   18.26     6.3   17.86
       8   17.86     8.3   18.16     8.7   18.16    10.8   20.26      12   20.86
    16.2   20.86    17.2   20.36    17.7   20.86    18.3   20.86    19.1   20.26
    29.1   20.26
#Mann= 3 , 0 , 0
     -10    .035       0       0    .035       0      12    .035       0
#XS Ineff= 2 , 0
               0   20.66      12           20.86
Permanent Ineff=
       F       F
Bank Sta=0,12
XS Rating Curve= 0
Exp/Cntr=.3,.1

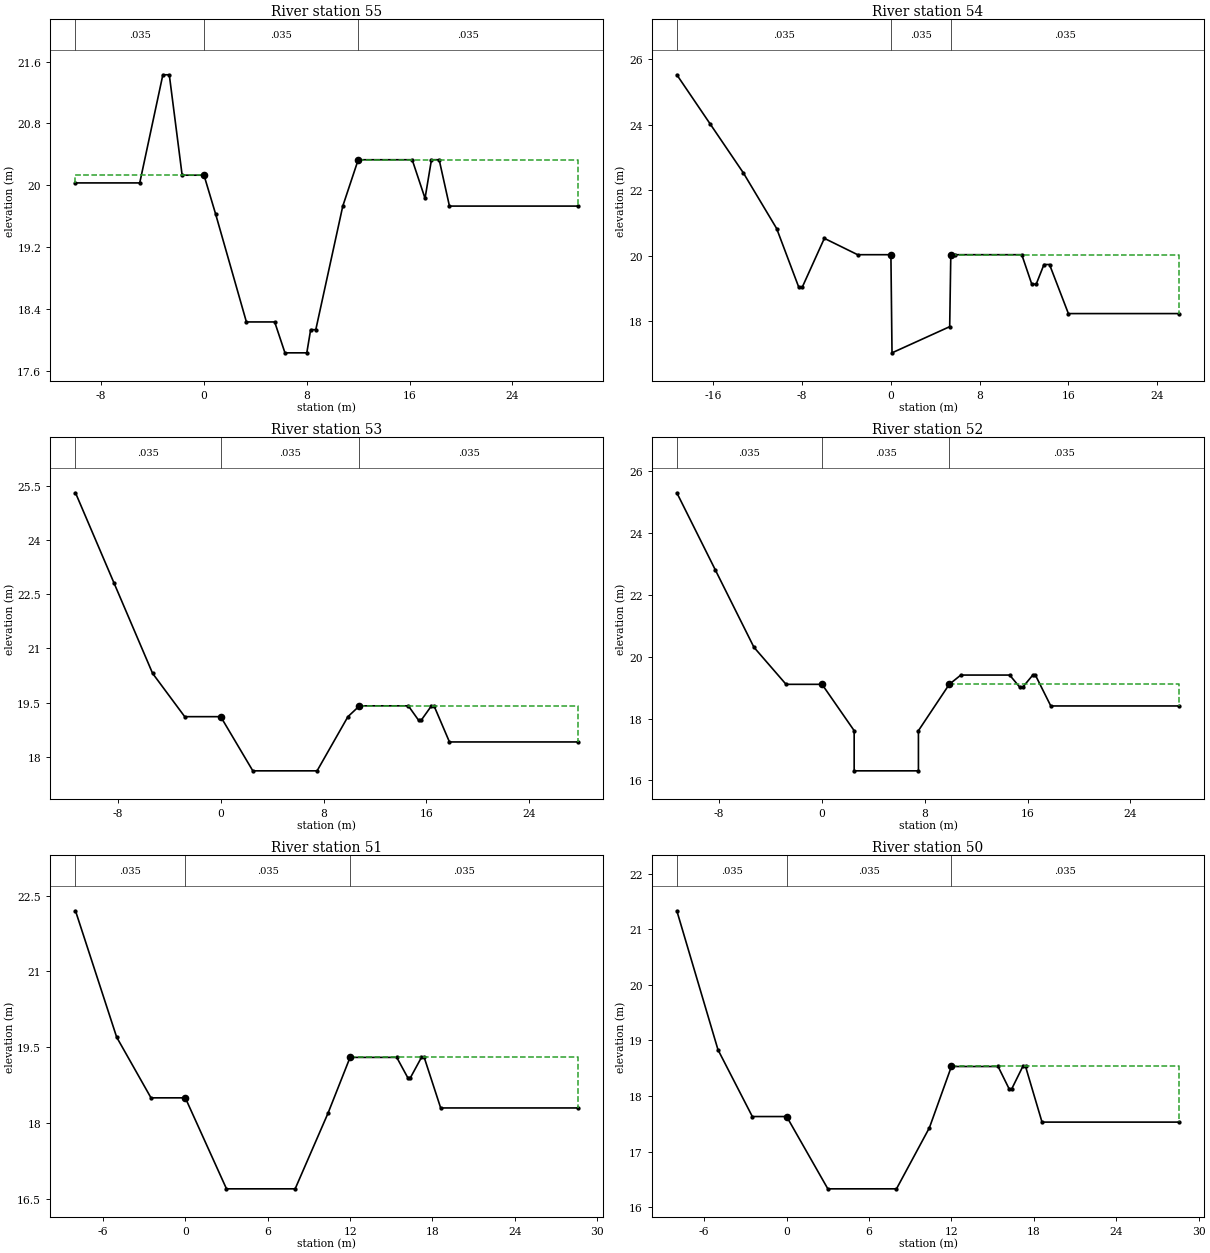
Type RM Length L Ch R = 1 ,55      ,23,23,23
BEGIN DESCRIPTION:
35
END DESCRIPTION:
#Sta/Elev= 21
     -10   20.03      -5   20.03    -3.2   21.43    -2.7   21.43    -1.7   20.13
       0   20.13      .9   19.63     3.3   18.23     5.5   18.23     6.3   17.83
       8   17.83     8.3   18.13     8.7   18.13    10.8   19.73      12   20.33
    16.2   20.33    17.2   19.83    17.7   20.33    18.3   20.33    19.1   19.73
    29.1   19.73
#Mann= 3 , 0 , 0
     -10    .035       0       0    .035       0      12    .035       0
#XS Ineff= 2 , 0
               0   20.13      12           20.33
Permanent Ineff=
       F       F
Bank Sta=0,12
XS Rating Curve= 0
Exp/Cntr=.3,.1

Type RM Length L Ch R = 1 ,54      ,22,22,22
BEGIN DESCRIPTION:
34.027
END DESCRIPTION:
#Sta/Elev= 20
   -19.3   25.53   -16.3   24.03   -13.3   22.53   -10.3   20.83    -8.3   19.03
      -8   19.03      -6   20.53      -3   20.03       0   20.03      .1   17.03
     5.3   17.83     5.4   20.03     5.8   20.03    11.8   20.03    12.7   19.13
    13.1   19.13    13.8   19.73    14.3   19.73      16   18.23      26   18.23
#Mann= 3 , 0 , 0
   -19.3    .035       0       0    .035       0     5.4    .035       0
#XS Ineff= 2 , 0
               0   20.03     5.4           20.03
Permanent Ineff=
       F       F
Bank Sta=0,5.4
XS Rating Curve= 0
Exp/Cntr=.3,.1

Type RM Length L Ch R = 1 ,53      ,1,1,1
BEGIN DESCRIPTION:
34.005
END DESCRIPTION:
#Sta/Elev= 16
   -11.3   25.31    -8.3   22.81    -5.3   20.31    -2.8   19.11       0   19.11
     2.5   17.61     7.5   17.61     9.9   19.11    10.8   19.41    14.6   19.41
    15.4   19.01    15.6   19.01    16.4   19.41    16.6   19.41    17.8   18.41
    27.8   18.41
#Mann= 3 , 0 , 0
   -11.3    .035       0       0    .035       0    10.8    .035       0
#XS Ineff= 2 , 0
               0   19.11    10.8           19.41
Permanent Ineff=
       F       F
Bank Sta=0,10.8
XS Rating Curve= 0
Exp/Cntr=.3,.1

Type RM Length L Ch R = 1 ,52      ,4,4,4
BEGIN DESCRIPTION:
34.004
END DESCRIPTION:
#Sta/Elev= 18
   -11.3   25.31    -8.3   22.81    -5.3   20.31    -2.8   19.11       0   19.11
     2.5   17.61     2.5   16.31     7.5   16.31     7.5   17.61     9.9   19.11
    10.8   19.41    14.6   19.41    15.4   19.01    15.6   19.01    16.4   19.41
    16.6   19.41    17.8   18.41    27.8   18.41
#Mann= 3 , 0 , 0
   -11.3    .035       0       0    .035       0     9.9    .035       0
#XS Ineff= 2 , 0
               0   19.11     9.9           19.11
Permanent Ineff=
       F       F
Bank Sta=0,9.9
XS Rating Curve= 0
Exp/Cntr=.3,.1

Type RM Length L Ch R = 1 ,51      ,50,50,50
BEGIN DESCRIPTION:
34
END DESCRIPTION:
#Sta/Elev= 15
      -8    22.2      -5    19.7    -2.5    18.5       0    18.5       3    16.7
       8    16.7    10.4    18.2      12    19.3    15.4    19.3    16.2    18.9
    16.4    18.9    17.2    19.3    17.4    19.3    18.6    18.3    28.6    18.3
#Mann= 3 , 0 , 0
      -8    .035       0       0    .035       0      12    .035       0
#XS Ineff= 2 , 0
               0    18.5      12            19.3
Permanent Ineff=
       F       F
Bank Sta=0,12
XS Rating Curve= 0
Exp/Cntr=.3,.1

Type RM Length L Ch R = 1 ,50      ,29,29,29
BEGIN DESCRIPTION:
33
END DESCRIPTION:
#Sta/Elev= 15
      -8   21.33      -5   18.83    -2.5   17.63       0   17.63       3   16.33
       8   16.33    10.4   17.43      12   18.53    15.4   18.53    16.2   18.13
    16.4   18.13    17.2   18.53    17.4   18.53    18.6   17.53    28.6   17.53
#Mann= 3 , 0 , 0
      -8    .035       0       0    .035       0      12    .035       0
#XS Ineff= 2 , 0
               0   17.63      12           18.53
Permanent Ineff=
       F       F
Bank Sta=0,12
XS Rating Curve= 0
Exp/Cntr=.3,.1

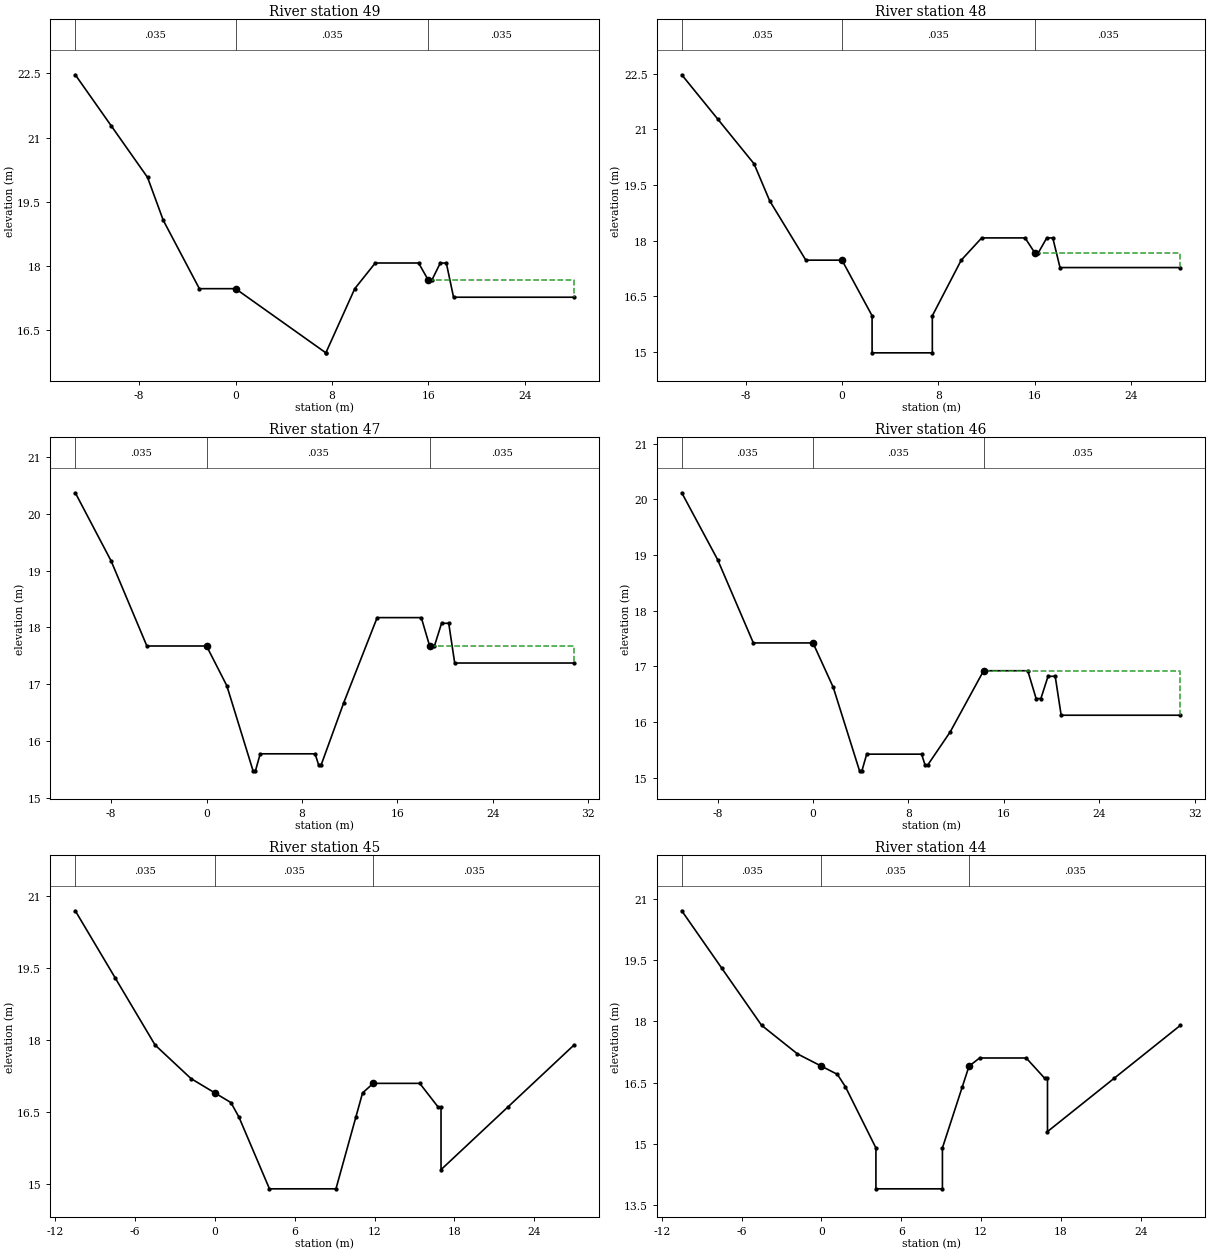
Type RM Length L Ch R = 1 ,49      ,1,1,1
BEGIN DESCRIPTION:
32.021
END DESCRIPTION:
#Sta/Elev= 17
   -13.3   22.47   -10.3   21.27    -7.3   20.07      -6   19.07      -3   17.47
       0   17.47     7.5   15.97     7.5   15.97     9.9   17.47    11.6   18.07
    15.2   18.07      16   17.67    16.3   17.67      17   18.07    17.5   18.07
    18.1   17.27    28.1   17.27
#Mann= 3 , 0 , 0
   -13.3    .035       0       0    .035       0      16    .035       0
#XS Ineff= 2 , 0
               0   17.47      16           17.67
Permanent Ineff=
       F       F
Bank Sta=0,16
XS Rating Curve= 0
Exp/Cntr=.3,.1

Type RM Length L Ch R = 1 ,48      ,20,20,20
BEGIN DESCRIPTION:
32.02
END DESCRIPTION:
#Sta/Elev= 19
   -13.3   22.47   -10.3   21.27    -7.3   20.07      -6   19.07      -3   17.47
       0   17.47     2.5   15.97     2.5   14.97     7.5   14.97     7.5   15.97
     9.9   17.47    11.6   18.07    15.2   18.07      16   17.67    16.3   17.67
      17   18.07    17.5   18.07    18.1   17.27    28.1   17.27
#Mann= 3 , 0 , 0
   -13.3    .035       0       0    .035       0      16    .035       0
#XS Ineff= 2 , 0
               0   17.47      16           17.67
Permanent Ineff=
       F       F
Bank Sta=0,16
XS Rating Curve= 0
Exp/Cntr=.3,.1

Type RM Length L Ch R = 1 ,47      ,50,50,50
BEGIN DESCRIPTION:
32
END DESCRIPTION:
#Sta/Elev= 20
     -11   20.37      -8   19.17      -5   17.67       0   17.67     1.7   16.97
     3.9   15.47     4.1   15.47     4.5   15.77     9.1   15.77     9.4   15.57
     9.6   15.57    11.5   16.67    14.3   18.17      18   18.17    18.7   17.67
    19.1   17.67    19.7   18.07    20.3   18.07    20.8   17.37    30.8   17.37
#Mann= 3 , 0 , 0
     -11    .035       0       0    .035       0    18.7    .035       0
#XS Ineff= 2 , 0
               0   17.67    18.7           17.67
Permanent Ineff=
       F       F
Bank Sta=0,18.7
XS Rating Curve= 0
Exp/Cntr=.3,.1

Type RM Length L Ch R = 1 ,46      ,1,1,1
BEGIN DESCRIPTION:
31
END DESCRIPTION:
#Sta/Elev= 20
     -11   20.12      -8   18.92      -5   17.42       0   17.42     1.7   16.62
     3.9   15.12     4.1   15.12     4.5   15.42     9.1   15.42     9.4   15.22
     9.6   15.22    11.5   15.82    14.3   16.92      18   16.92    18.7   16.42
    19.1   16.42    19.7   16.82    20.3   16.82    20.8   16.12    30.8   16.12
#Mann= 3 , 0 , 0
     -11    .035       0       0    .035       0    14.3    .035       0
#XS Ineff= 2 , 0
               0   17.42    14.3           16.92
Permanent Ineff=
       F       F
Bank Sta=0,14.3
XS Rating Curve= 0
Exp/Cntr=.3,.1

Type RM Length L Ch R = 1 ,45      ,1,1,1
BEGIN DESCRIPTION:
30.049
END DESCRIPTION:
#Sta/Elev= 18
   -10.5    20.7    -7.5    19.3    -4.5    17.9    -1.8    17.2       0    16.9
     1.2    16.7     1.8    16.4     4.1    14.9     9.1    14.9    10.6    16.4
    11.1    16.9    11.9    17.1    15.4    17.1    16.8    16.6      17    16.6
      17    15.3      22    16.6      27    17.9
#Mann= 3 , 0 , 0
   -10.5    .035       0       0    .035       0    11.9    .035       0
#XS Ineff= 2 , 0
               0    16.9    11.9            17.1
Permanent Ineff=
       F       F
Bank Sta=0,11.9
XS Rating Curve= 0
Exp/Cntr=.3,.1

Type RM Length L Ch R = 1 ,44      ,43,43,43
BEGIN DESCRIPTION:
30.049
END DESCRIPTION:
#Sta/Elev= 20
   -10.5    20.7    -7.5    19.3    -4.5    17.9    -1.8    17.2       0    16.9
     1.2    16.7     1.8    16.4     4.1    14.9     4.1    13.9     9.1    13.9
     9.1    14.9    10.6    16.4    11.1    16.9    11.9    17.1    15.4    17.1
    16.8    16.6      17    16.6      17    15.3      22    16.6      27    17.9
#Mann= 3 , 0 , 0
   -10.5    .035       0       0    .035       0    11.1    .035       0
#XS Ineff= 2 , 0
               0    16.9    11.1            16.9
Permanent Ineff=
       F       F
Bank Sta=0,11.1
XS Rating Curve= 0
Exp/Cntr=.3,.1

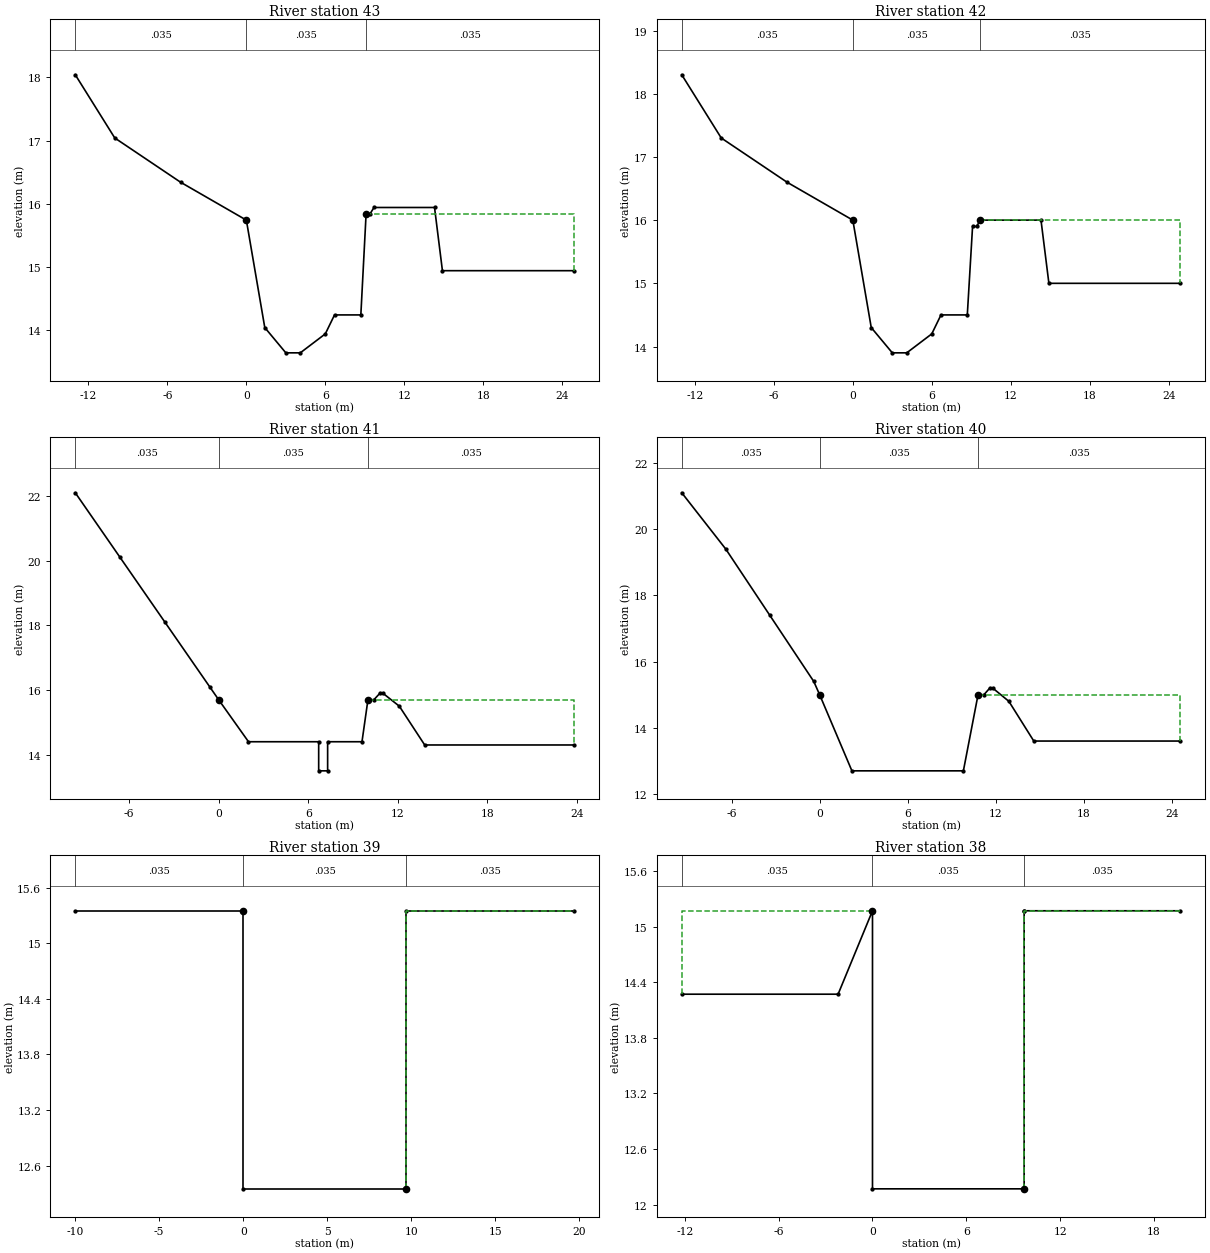
Type RM Length L Ch R = 1 ,43      ,6,6,6
BEGIN DESCRIPTION:
30.006
END DESCRIPTION:
#Sta/Elev= 16
     -13   18.04     -10   17.04      -5   16.34       0   15.74     1.4   14.04
       3   13.64     4.1   13.64       6   13.94     6.7   14.24     8.7   14.24
     9.1   15.84     9.4   15.84     9.7   15.94    14.3   15.94    14.9   14.94
    24.9   14.94
#Mann= 3 , 0 , 0
     -13    .035       0       0    .035       0     9.1    .035       0
#XS Ineff= 2 , 0
               0   15.74     9.1           15.84
Permanent Ineff=
       F       F
Bank Sta=0,9.1
XS Rating Curve= 0
Exp/Cntr=.3,.1

Type RM Length L Ch R = 1 ,42      ,22,22,22
BEGIN DESCRIPTION:
30
END DESCRIPTION:
#Sta/Elev= 16
     -13    18.3     -10    17.3      -5    16.6       0      16     1.4    14.3
       3    13.9     4.1    13.9       6    14.2     6.7    14.5     8.7    14.5
     9.1    15.9     9.4    15.9     9.7      16    14.3      16    14.9      15
    24.9      15
#Mann= 3 , 0 , 0
     -13    .035       0       0    .035       0     9.7    .035       0
#XS Ineff= 2 , 0
               0      16     9.7              16
Permanent Ineff=
       F       F
Bank Sta=0,9.7
XS Rating Curve= 0
Exp/Cntr=.3,.1

Type RM Length L Ch R = 1 ,41      ,28,28,28
BEGIN DESCRIPTION:
29.028
END DESCRIPTION:
#Sta/Elev= 18
    -9.6    22.1    -6.6    20.1    -3.6    18.1     -.6    16.1       0    15.7
       2    14.4     6.7    14.4     6.7    13.5     7.3    13.5     7.3    14.4
     9.6    14.4      10    15.7    10.4    15.7    10.8    15.9      11    15.9
    12.1    15.5    13.8    14.3    23.8    14.3
#Mann= 3 , 0 , 0
    -9.6    .035       0       0    .035       0      10    .035       0
#XS Ineff= 2 , 0
               0    15.7      10            15.7
Permanent Ineff=
       F       F
Bank Sta=0,10
XS Rating Curve= 0
Exp/Cntr=.3,.1

Type RM Length L Ch R = 1 ,40      ,40,40,40
BEGIN DESCRIPTION:
29
END DESCRIPTION:
#Sta/Elev= 14
    -9.4    21.1    -6.4    19.4    -3.4    17.4     -.4    15.4       0      15
     2.2    12.7     9.8    12.7    10.8      15    11.2      15    11.6    15.2
    11.8    15.2    12.9    14.8    14.6    13.6    24.6    13.6
#Mann= 3 , 0 , 0
    -9.4    .035       0       0    .035       0    10.8    .035       0
#XS Ineff= 2 , 0
               0      15    10.8              15
Permanent Ineff=
       F       F
Bank Sta=0,10.8
XS Rating Curve= 0
Exp/Cntr=.3,.1

Type RM Length L Ch R = 1 ,39      ,9,9,9
BEGIN DESCRIPTION:
28.01
END DESCRIPTION:
#Sta/Elev= 6
     -10   15.35       0   15.35       0   12.35     9.7   12.35     9.7   15.35
    19.7   15.35
#Mann= 3 , 0 , 0
     -10    .035       0       0    .035       0     9.7    .035       0
#XS Ineff= 2 , 0
               0   15.35     9.7           15.35
Permanent Ineff=
       F       F
Bank Sta=0,9.7
XS Rating Curve= 0
Exp/Cntr=.3,.1

Type RM Length L Ch R = 1 ,38      ,1,1,1
BEGIN DESCRIPTION:
28.001
END DESCRIPTION:
#Sta/Elev= 8
   -12.2   14.27    -2.2   14.27       0   15.17       0   12.17     9.7   12.17
     9.7   15.17     9.7   15.17    19.7   15.17
#Mann= 3 , 0 , 0
   -12.2    .035       0       0    .035       0     9.7    .035       0
#XS Ineff= 2 , 0
               0   15.17     9.7           15.17
Permanent Ineff=
       F       F
Bank Sta=0,9.7
XS Rating Curve= 0
Exp/Cntr=.3,.1

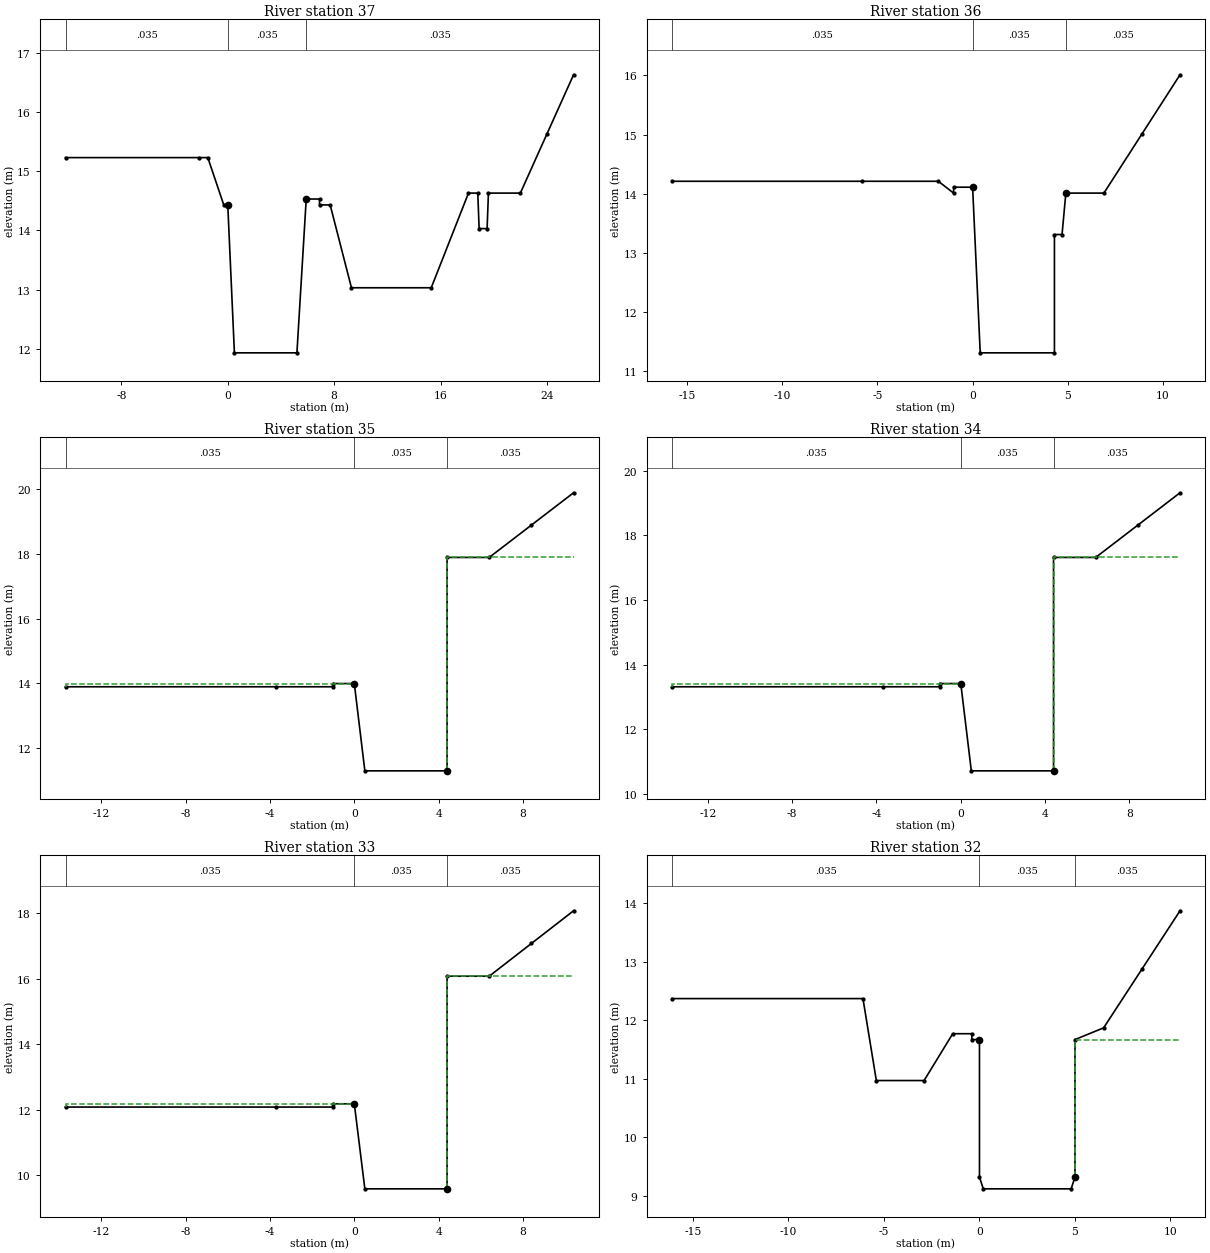
Type RM Length L Ch R = 1 ,37      ,41,41,41
BEGIN DESCRIPTION:
28
END DESCRIPTION:
#Sta/Elev= 21
   -12.2   15.23    -2.2   15.23    -1.5   15.23     -.3   14.43       0   14.43
      .5   11.93     5.2   11.93     5.9   14.53     6.9   14.53     6.9   14.43
     7.7   14.43     9.3   13.03    15.3   13.03    18.1   14.63    18.8   14.63
    18.9   14.03    19.5   14.03    19.6   14.63      22   14.63      24   15.63
      26   16.63
#Mann= 3 , 0 , 0
   -12.2    .035       0       0    .035       0     5.9    .035       0
#XS Ineff= 2 , 0
               0   14.43     5.9           14.53
Permanent Ineff=
       F       F
Bank Sta=0,5.9
XS Rating Curve= 0
Exp/Cntr=.3,.1

Type RM Length L Ch R = 1 ,36      ,9,9,9
BEGIN DESCRIPTION:
27.009
END DESCRIPTION:
#Sta/Elev= 14
   -15.8   14.21    -5.8   14.21    -1.8   14.21      -1   14.01      -1   14.11
       0   14.11      .4   11.31     4.3   11.31     4.3   13.31     4.7   13.31
     4.9   14.01     6.9   14.01     8.9   15.01    10.9   16.01
#Mann= 3 , 0 , 0
   -15.8    .035       0       0    .035       0     4.9    .035       0
#XS Ineff= 2 , 0
               0   14.11     4.9           14.01
Permanent Ineff=
       F       F
Bank Sta=0,4.9
XS Rating Curve= 0
Exp/Cntr=.3,.1

Type RM Length L Ch R = 1 ,35      ,50,50,50
BEGIN DESCRIPTION:
27
END DESCRIPTION:
#Sta/Elev= 11
   -13.7   13.89    -3.7   13.89      -1   13.89      -1   13.99       0   13.99
      .5   11.29     4.4   11.29     4.4   17.89     6.4   17.89     8.4   18.89
    10.4   19.89
#Mann= 3 , 0 , 0
   -13.7    .035       0       0    .035       0     4.4    .035       0
#XS Ineff= 2 , 0
               0   13.99     4.4           17.89
Permanent Ineff=
       F       F
Bank Sta=0,4.4
XS Rating Curve= 0
Exp/Cntr=.3,.1

Type RM Length L Ch R = 1 ,34      ,50,50,50
BEGIN DESCRIPTION:
26
END DESCRIPTION:
#Sta/Elev= 11
   -13.7   13.32    -3.7   13.32      -1   13.32      -1   13.42       0   13.42
      .5   10.72     4.4   10.72     4.4   17.32     6.4   17.32     8.4   18.32
    10.4   19.32
#Mann= 3 , 0 , 0
   -13.7    .035       0       0    .035       0     4.4    .035       0
#XS Ineff= 2 , 0
               0   13.42     4.4           17.32
Permanent Ineff=
       F       F
Bank Sta=0,4.4
XS Rating Curve= 0
Exp/Cntr=.3,.1

Type RM Length L Ch R = 1 ,33      ,21,21,21
BEGIN DESCRIPTION:
25
END DESCRIPTION:
#Sta/Elev= 11
   -13.7   12.08    -3.7   12.08      -1   12.08      -1   12.18       0   12.18
      .5    9.58     4.4    9.58     4.4   16.08     6.4   16.08     8.4   17.08
    10.4   18.08
#Mann= 3 , 0 , 0
   -13.7    .035       0       0    .035       0     4.4    .035       0
#XS Ineff= 2 , 0
               0   12.18     4.4           16.08
Permanent Ineff=
       F       F
Bank Sta=0,4.4
XS Rating Curve= 0
Exp/Cntr=.3,.1

Type RM Length L Ch R = 1 ,32      ,29,29,29
BEGIN DESCRIPTION:
24.029
END DESCRIPTION:
#Sta/Elev= 16
   -16.1   12.37    -6.1   12.37    -5.4   10.97    -2.9   10.97    -1.4   11.77
     -.4   11.77     -.4   11.67       0   11.67       0    9.32      .2    9.12
     4.8    9.12       5    9.32       5   11.67     6.5   11.87     8.5   12.87
    10.5   13.87
#Mann= 3 , 0 , 0
   -16.1    .035       0       0    .035       0       5    .035       0
#XS Ineff= 2 , 0
               0   11.67       5           11.67
Permanent Ineff=
       F       F
Bank Sta=0,5
XS Rating Curve= 0
Exp/Cntr=.3,.1

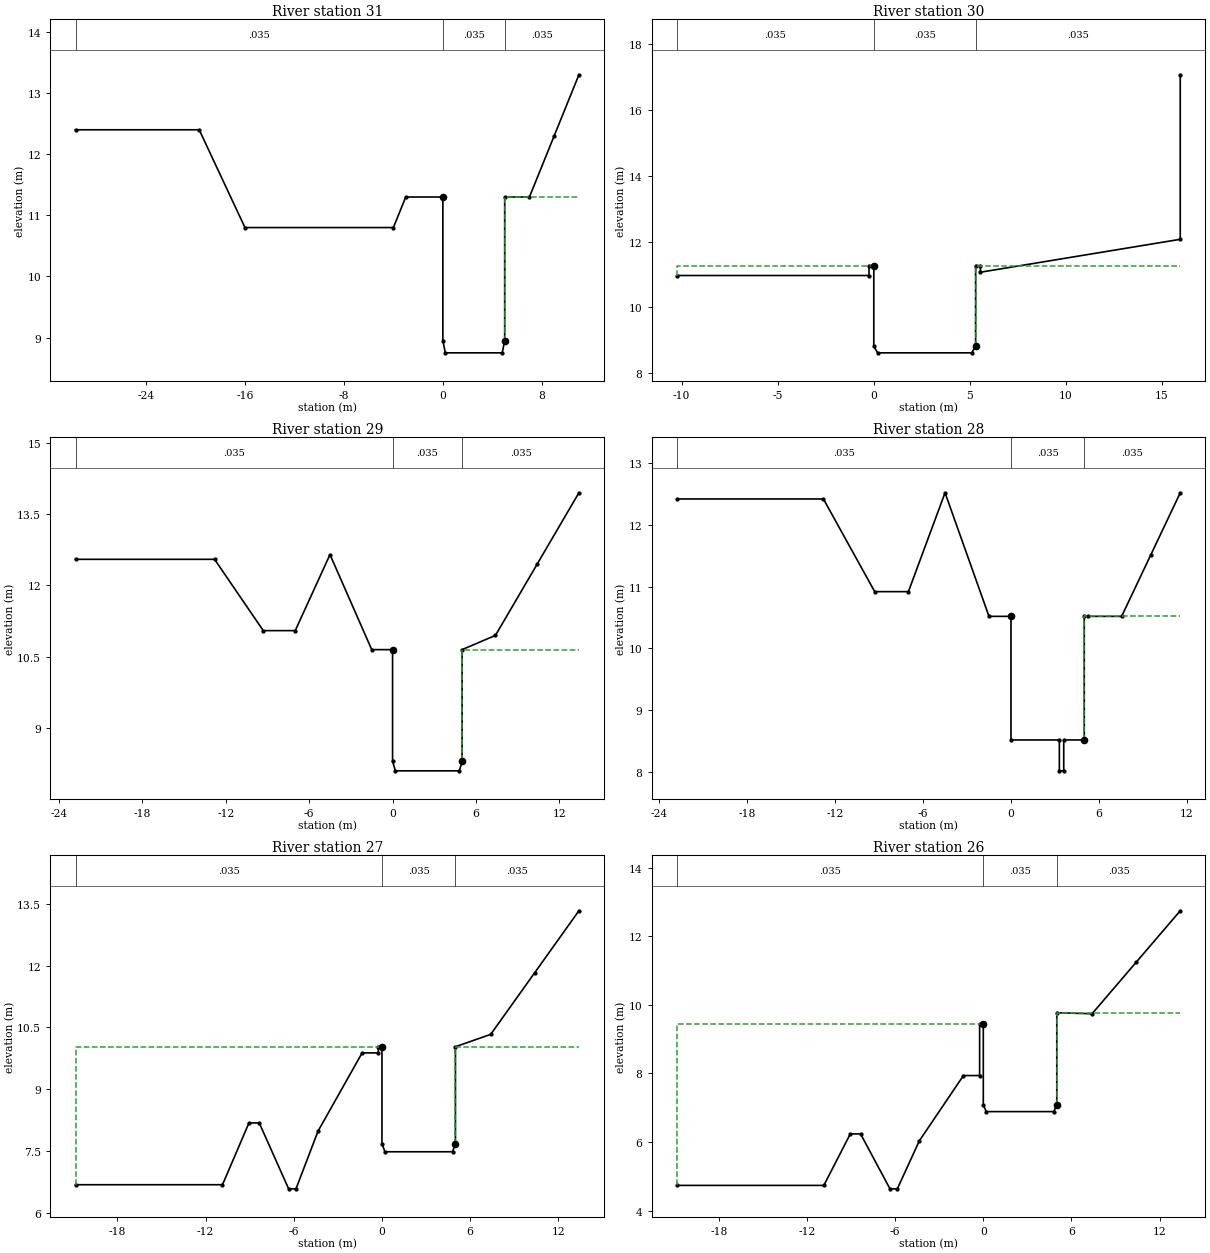
Type RM Length L Ch R = 1 ,31      ,10,10,10
BEGIN DESCRIPTION:
24
END DESCRIPTION:
#Sta/Elev= 14
   -29.7    12.4   -19.7    12.4     -16    10.8      -4    10.8      -3    11.3
       0    11.3       0    8.95      .2    8.75     4.8    8.75       5    8.95
       5    11.3       7    11.3       9    12.3      11    13.3
#Mann= 3 , 0 , 0
   -29.7    .035       0       0    .035       0       5    .035       0
#XS Ineff= 2 , 0
               0    11.3       5            11.3
Permanent Ineff=
       F       F
Bank Sta=0,5
XS Rating Curve= 0
Exp/Cntr=.3,.1

Type RM Length L Ch R = 1 ,30      ,40,40,40
BEGIN DESCRIPTION:
23.04
END DESCRIPTION:
#Sta/Elev= 13
  -10.25   10.97    -.25   10.97    -.25   11.27       0   11.27       0    8.82
      .2    8.62     5.1    8.62     5.3    8.82     5.3   11.27    5.55   11.27
    5.55   11.07   15.95   12.07   15.95   17.07
#Mann= 3 , 0 , 0
  -10.25    .035       0       0    .035       0     5.3    .035       0
#XS Ineff= 2 , 0
               0   11.27     5.3           11.27
Permanent Ineff=
       F       F
Bank Sta=0,5.3
XS Rating Curve= 0
Exp/Cntr=.3,.1

Type RM Length L Ch R = 1 ,29      ,9,9,9
BEGIN DESCRIPTION:
23
END DESCRIPTION:
#Sta/Elev= 15
   -22.8   12.55   -12.8   12.55    -9.3   11.05      -7   11.05    -4.5   12.65
    -1.5   10.65       0   10.65       0     8.3      .2     8.1     4.8     8.1
       5     8.3       5   10.65     7.4   10.95    10.4   12.45    13.4   13.95
#Mann= 3 , 0 , 0
   -22.8    .035       0       0    .035       0       5    .035       0
#XS Ineff= 2 , 0
               0   10.65       5           10.65
Permanent Ineff=
       F       F
Bank Sta=0,5
XS Rating Curve= 0
Exp/Cntr=.3,.1

Type RM Length L Ch R = 1 ,28      ,41,41,41
BEGIN DESCRIPTION:
22.041
END DESCRIPTION:
#Sta/Elev= 18
   -22.8   12.42   -12.8   12.42    -9.3   10.92      -7   10.92    -4.5   12.52
    -1.5   10.52       0   10.52       0    8.52     3.3    8.52     3.3    8.02
     3.6    8.02     3.6    8.52       5    8.52       5   10.52    5.25   10.52
    7.55   10.52    9.55   11.52   11.55   12.52
#Mann= 3 , 0 , 0
   -22.8    .035       0       0    .035       0       5    .035       0
#XS Ineff= 2 , 0
               0   10.52       5           10.52
Permanent Ineff=
       F       F
Bank Sta=0,5
XS Rating Curve= 0
Exp/Cntr=.3,.1

Type RM Length L Ch R = 1 ,27      ,50,50,50
BEGIN DESCRIPTION:
22
END DESCRIPTION:
#Sta/Elev= 19
  -20.85    6.68  -10.85    6.68   -9.05    8.18   -8.35    8.18   -6.35    6.58
   -5.85    6.58   -4.35    7.98   -1.35    9.88    -.25    9.88    -.25   10.03
       0   10.03       0    7.68      .2    7.48     4.8    7.48       5    7.68
       5   10.03     7.4   10.33    10.4   11.83    13.4   13.33
#Mann= 3 , 0 , 0
  -20.85    .035       0       0    .035       0       5    .035       0
#XS Ineff= 2 , 0
               0   10.03       5           10.03
Permanent Ineff=
       F       F
Bank Sta=0,5
XS Rating Curve= 0
Exp/Cntr=.3,.1

Type RM Length L Ch R = 1 ,26      ,50,50,50
BEGIN DESCRIPTION:
21
END DESCRIPTION:
#Sta/Elev= 19
  -20.85    4.74  -10.85    4.74   -9.05    6.24   -8.35    6.24   -6.35    4.64
   -5.85    4.64   -4.35    6.04   -1.35    7.94    -.25    7.94    -.25    9.44
       0    9.44       0    7.09      .2    6.89     4.8    6.89       5    7.09
       5    9.77     7.4    9.74    10.4   11.24    13.4   12.74
#Mann= 3 , 0 , 0
  -20.85    .035       0       0    .035       0       5    .035       0
#XS Ineff= 2 , 0
               0    9.44       5            9.77
Permanent Ineff=
       F       F
Bank Sta=0,5
XS Rating Curve= 0
Exp/Cntr=.3,.1