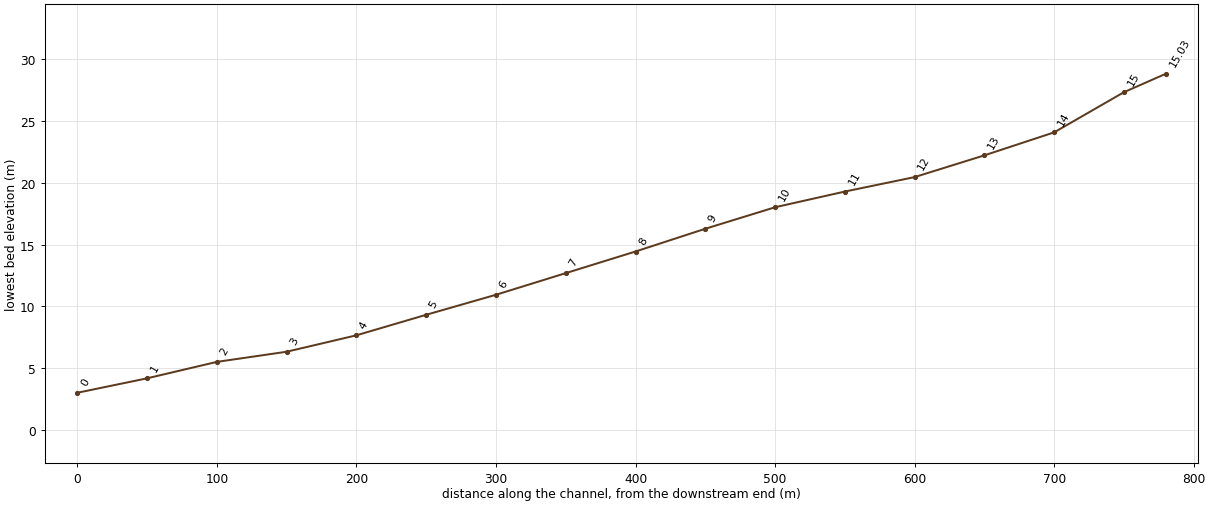
--- KIPEUN.prj (project) ---

Proj Title=KIPEUN
Current Plan=p01
Default Exp/Contr=.3,.1
SI Units
Geom File=g01
Flow File=f01
Plan File=p01
Y Axis Title=Elevation
X Axis Title(PF)=Main Channel Distance
X Axis Title(XS)=Station
BEGIN DESCRIPTION:
           BACK WATER COMPUTATION
      APPLICATION OF HEC-2 BY Samju Construction Engineering
      KIPEUN-STREEM : 30 YR
END DESCRIPTION:
DSS Export Rating Curves= 0
DSS Export Rating Curve Sorted= 0
DSS Export Volume Flow Curves= 0
DXF OffsetX= 0
DXF OffsetY= 0
DXF ScaleX= 1
DXF ScaleY= 10

--- KIPEUN.p01 (plan) ---

Plan Title=Imported Plan 01
Version=Version 3.0.1  Mar 2001
Short Identifier=Imported Pla
Geom File=g01
Flow File=f01
Subcritical Flow
K Sum by GR= 0
Std Step Tol= 0.003
Critical Tol= 0.003
Num of Std Step Trials= 20
Max Error Tol= 0.1
Flow Tol Ratio= 0.001
Split Flow NTrial= 30
Split Flow Tol= 0.02
Split Flow Ratio= 0.02
Log Output Level= 0
Friction Slope Method= 1
Unsteady Friction Slope Method= 2
Parabolic Critical Depth
Global Vel Dist= 0 , 0 , 0
Global Log Level= 0
CheckData=True
Encroach Param=-1 ,0,0, 0
Computation Interval=1HOUR
Output Interval=1HOUR
Run HTab= 0
Run UNet= 0
Run PostProcess= 0
UNET Theta= 1
UNET ZTol= 0.02
UNET ZSATol= 0.1
UNET MxIter= 20
UNET MaxInSteps= 20
UNET DtIC= 0
UNET DtMin= 0
UNET MaxCRTS= 20
UNET WFStab= 2
UNET SFStab= 1
UNET WFX= 1
UNET SFX= 1
UNET Convert EG Bridges=-1
UNET Use Existing IB Tables=-1
Instantaneous Interval=1HOUR
Write IC File= 0
Write Velocity= 0
Write Detailed= 0

--- KIPEUN.f01 (steady flow) ---

Flow Title=Imported Flow 01
Version=Version 3.0.1  Mar 2001
Number of Profiles= 1
Profile Names=PF 1
River Rch & RM=RIVER-1,Reach-1         ,15.03
   15.24
Boundary for River Rch & Prof#=RIVER-1,Reach-1         , 1
Up Type= 0
Dn Type= 3
Dn Slope=.0109
DSS Import GetInterval= 0
DSS Import GetPeak= 0
DSS Import FillOption= 0

--- KIPEUN.g01 (geometry) ---

Geom Title=Imported Geom 01
Version=Version 3.0.1  Mar 2001

River Reach=RIVER-1         ,Reach-1
Reach XY= 2
              .5             .95              .5             .05

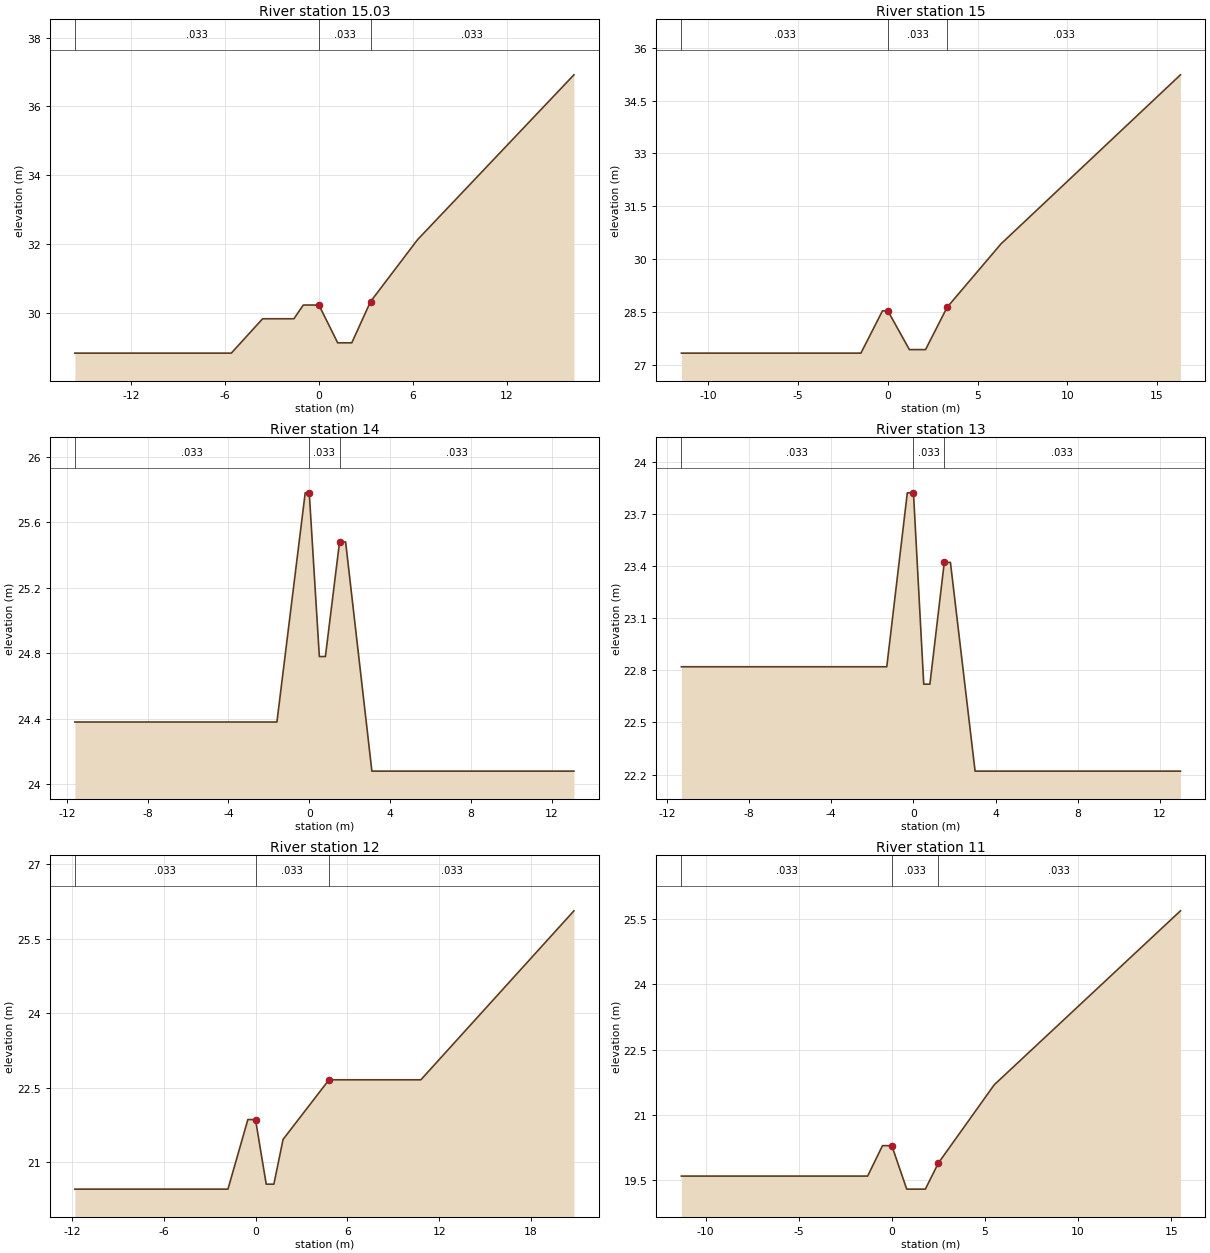
Type RM Length L Ch R = 1 ,15.03   ,30,30,30
#Sta/Elev= 12
   -15.6   28.82    -5.6   28.82    -3.6   29.82    -1.6   29.82      -1   30.22
       0   30.22     1.2   29.12     2.1   29.12     3.3   30.32     6.3   32.12
    11.3   34.52    16.3   36.92
#Mann= 3 , 0 , 0
   -15.6    .033       0       0    .033       0     3.3    .033       0
Bank Sta=0,3.3
XS Rating Curve= 0
Exp/Cntr=.3,.1

Type RM Length L Ch R = 1 ,15      ,50,50,50
#Sta/Elev= 10
   -11.5   27.33    -1.5   27.33     -.3   28.53       0   28.53     1.2   27.43
     2.1   27.43     3.3   28.63     6.3   30.43    11.3   32.83    16.3   35.23
#Mann= 3 , 0 , 0
   -11.5    .033       0       0    .033       0     3.3    .033       0
Bank Sta=0,3.3
XS Rating Curve= 0
Exp/Cntr=.3,.1

Type RM Length L Ch R = 1 ,14      ,50,50,50
#Sta/Elev= 10
   -11.6   24.38    -1.6   24.38     -.2   25.78       0   25.78      .5   24.78
      .8   24.78     1.5   25.48     1.8   25.48     3.1   24.08    13.1   24.08
#Mann= 3 , 0 , 0
   -11.6    .033       0       0    .033       0     1.5    .033       0
Bank Sta=0,1.5
XS Rating Curve= 0
Exp/Cntr=.3,.1

Type RM Length L Ch R = 1 ,13      ,50,50,50
#Sta/Elev= 10
   -11.3   22.82    -1.3   22.82     -.3   23.82       0   23.82      .5   22.72
      .8   22.72     1.5   23.42     1.8   23.42       3   22.22      13   22.22
#Mann= 3 , 0 , 0
   -11.3    .033       0       0    .033       0     1.5    .033       0
Bank Sta=0,1.5
XS Rating Curve= 0
Exp/Cntr=.3,.1

Type RM Length L Ch R = 1 ,12      ,50,50,50
#Sta/Elev= 11
   -11.8   20.46    -1.8   20.46     -.5   21.86       0   21.86      .7   20.56
     1.2   20.56     1.8   21.46     4.8   22.66    10.8   22.66    15.8   24.36
    20.8   26.06
#Mann= 3 , 0 , 0
   -11.8    .033       0       0    .033       0     4.8    .033       0
Bank Sta=0,4.8
XS Rating Curve= 0
Exp/Cntr=.3,.1

Type RM Length L Ch R = 1 ,11      ,50,50,50
#Sta/Elev= 10
   -11.3   19.59    -1.3   19.59     -.5   20.29       0   20.29      .8   19.29
     1.8   19.29     2.5   19.89     5.5   21.69    10.5   23.69    15.5   25.69
#Mann= 3 , 0 , 0
   -11.3    .033       0       0    .033       0     2.5    .033       0
Bank Sta=0,2.5
XS Rating Curve= 0
Exp/Cntr=.3,.1

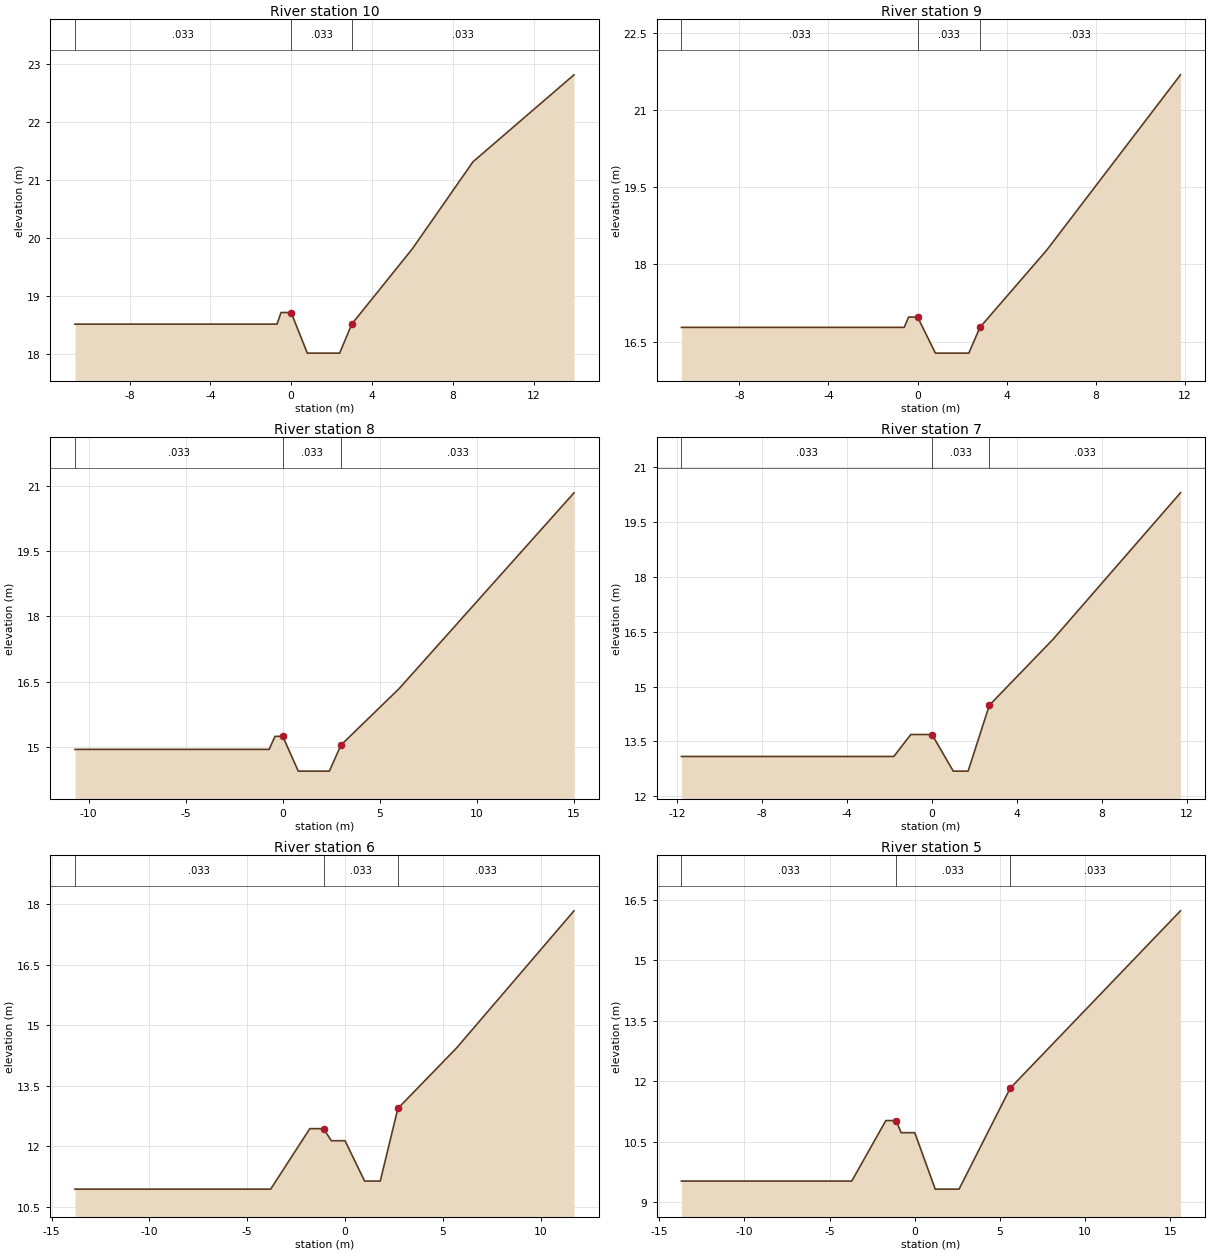
Type RM Length L Ch R = 1 ,10      ,50,50,50
#Sta/Elev= 10
   -10.7   18.52     -.7   18.52     -.5   18.72       0   18.72      .8   18.02
     2.4   18.02       3   18.52       6   19.82       9   21.32      14   22.82
#Mann= 3 , 0 , 0
   -10.7    .033       0       0    .033       0       3    .033       0
Bank Sta=0,3
XS Rating Curve= 0
Exp/Cntr=.3,.1

Type RM Length L Ch R = 1 ,9       ,50,50,50
#Sta/Elev= 10
   -10.6   16.78     -.6   16.78     -.4   16.98       0   16.98      .8   16.28
     2.3   16.28     2.8   16.78     5.8   18.28     8.8   19.98    11.8   21.68
#Mann= 3 , 0 , 0
   -10.6    .033       0       0    .033       0     2.8    .033       0
Bank Sta=0,2.8
XS Rating Curve= 0
Exp/Cntr=.3,.1

Type RM Length L Ch R = 1 ,8       ,50,50,50
#Sta/Elev= 11
   -10.7   14.94     -.7   14.94     -.4   15.24       0   15.24      .8   14.44
     2.4   14.44       3   15.04       6   16.34       9   17.84      12   19.34
      15   20.84
#Mann= 3 , 0 , 0
   -10.7    .033       0       0    .033       0       3    .033       0
Bank Sta=0,3
XS Rating Curve= 0
Exp/Cntr=.3,.1

Type RM Length L Ch R = 1 ,7       ,50,50,50
#Sta/Elev= 10
   -11.8   13.09    -1.8   13.09      -1   13.69       0   13.69       1   12.69
     1.7   12.69     2.7   14.49     5.7   16.29     8.7   18.29    11.7   20.29
#Mann= 3 , 0 , 0
   -11.8    .033       0       0    .033       0     2.7    .033       0
Bank Sta=0,2.7
XS Rating Curve= 0
Exp/Cntr=.3,.1

Type RM Length L Ch R = 1 ,6       ,50,50,50
#Sta/Elev= 12
   -13.8   10.94    -3.8   10.94    -1.8   12.44    -1.1   12.44     -.7   12.14
       0   12.14       1   11.14     1.8   11.14     2.7   12.94     5.7   14.44
     8.7   16.14    11.7   17.84
#Mann= 3 , 0 , 0
   -13.8    .033       0    -1.1    .033       0     2.7    .033       0
Bank Sta=-1.1,2.7
XS Rating Curve= 0
Exp/Cntr=.3,.1

Type RM Length L Ch R = 1 ,5       ,50,50,50
#Sta/Elev= 11
   -13.7    9.52    -3.7    9.52    -1.7   11.02    -1.1   11.02     -.8   10.72
       0   10.72     1.2    9.32     2.6    9.32     5.6   11.82    10.6   14.02
    15.6   16.22
#Mann= 3 , 0 , 0
   -13.7    .033       0    -1.1    .033       0     5.6    .033       0
Bank Sta=-1.1,5.6
XS Rating Curve= 0
Exp/Cntr=.3,.1

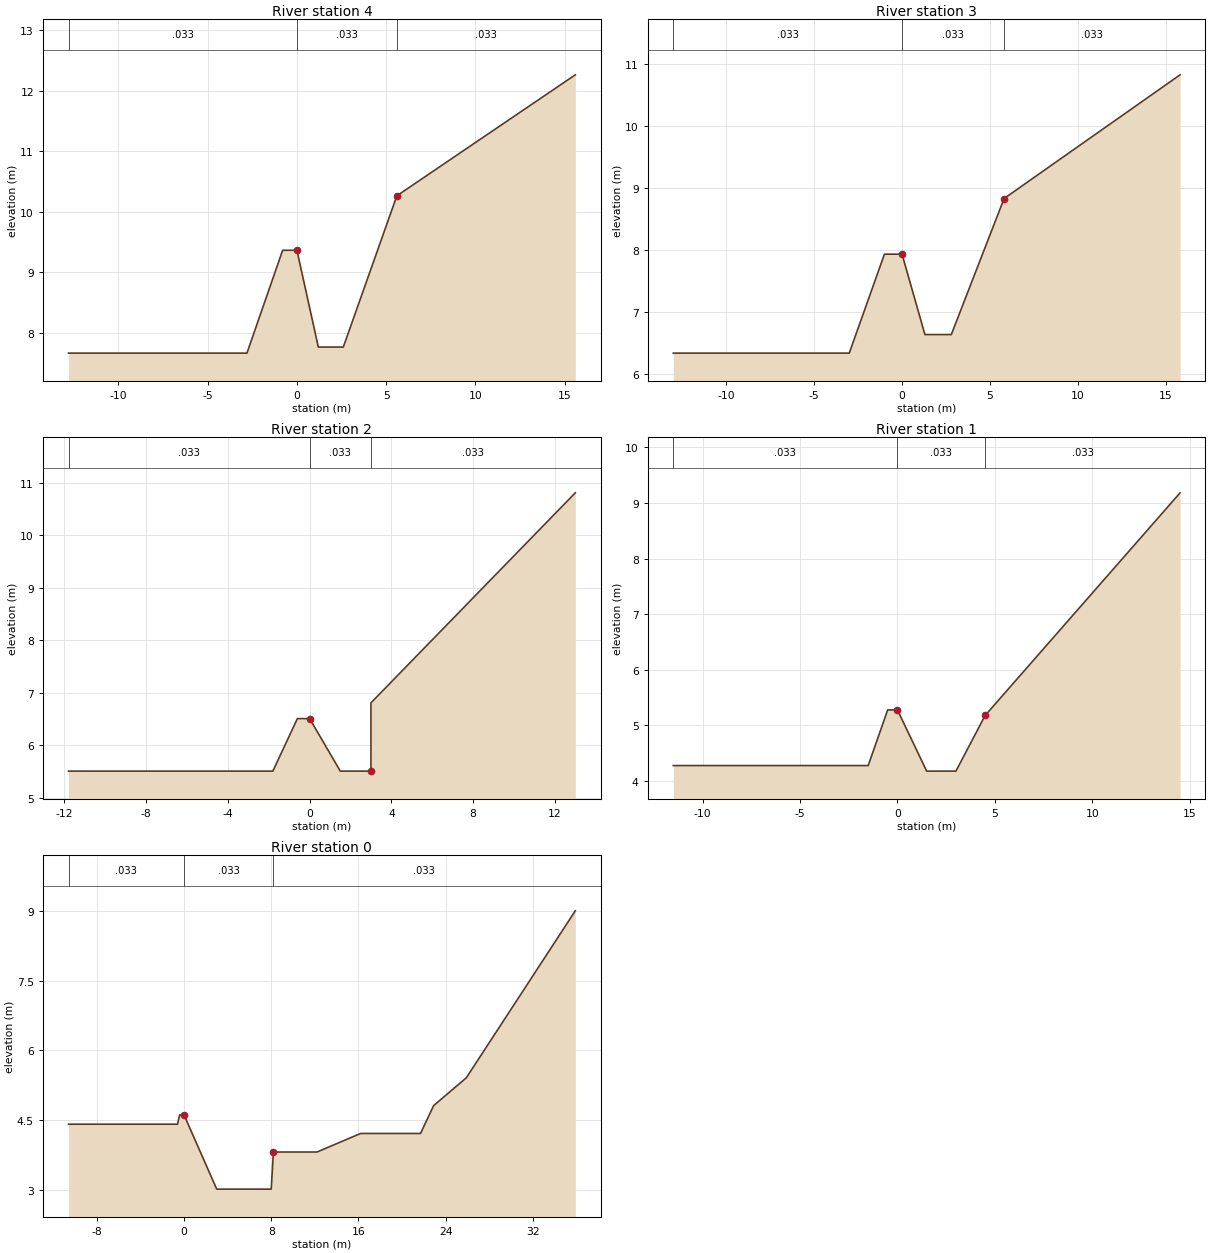
Type RM Length L Ch R = 1 ,4       ,50,50,50
#Sta/Elev= 9
   -12.8    7.66    -2.8    7.66     -.8    9.36       0    9.36     1.2    7.76
     2.6    7.76     5.6   10.26    10.6   11.26    15.6   12.26
#Mann= 3 , 0 , 0
   -12.8    .033       0       0    .033       0     5.6    .033       0
Bank Sta=0,5.6
XS Rating Curve= 0
Exp/Cntr=.3,.1

Type RM Length L Ch R = 1 ,3       ,50,50,50
#Sta/Elev= 9
     -13    6.33      -3    6.33      -1    7.93       0    7.93     1.3    6.63
     2.8    6.63     5.8    8.83    10.8    9.83    15.8   10.83
#Mann= 3 , 0 , 0
     -13    .033       0       0    .033       0     5.8    .033       0
Bank Sta=0,5.8
XS Rating Curve= 0
Exp/Cntr=.3,.1

Type RM Length L Ch R = 1 ,2       ,50,50,50
#Sta/Elev= 9
   -11.8    5.51    -1.8    5.51     -.6    6.51       0    6.51     1.5    5.51
       3    5.51       3    6.81       8    8.81      13   10.81
#Mann= 3 , 0 , 0
   -11.8    .033       0       0    .033       0       3    .033       0
Bank Sta=0,3
XS Rating Curve= 0
Exp/Cntr=.3,.1

Type RM Length L Ch R = 1 ,1       ,50,50,50
#Sta/Elev= 9
   -11.5    4.28    -1.5    4.28     -.5    5.28       0    5.28     1.5    4.18
       3    4.18     4.5    5.18     9.5    7.18    14.5    9.18
#Mann= 3 , 0 , 0
   -11.5    .033       0       0    .033       0     4.5    .033       0
Bank Sta=0,4.5
XS Rating Curve= 0
Exp/Cntr=.3,.1

Type RM Length L Ch R = 1 ,0       ,0,0,0
#Sta/Elev= 15
   -10.6    4.41     -.6    4.41     -.4    4.61       0    4.61       3    3.01
       8    3.01     8.2    3.81    12.2    3.81    14.2    4.01    16.2    4.21
    21.7    4.21    22.9    4.81    25.9    5.41    30.9    7.21    35.9    9.01
#Mann= 3 , 0 , 0
   -10.6    .033       0       0    .033       0     8.2    .033       0
Bank Sta=0,8.2
XS Rating Curve= 0
Exp/Cntr=.3,.1

Chan Stop Cuts=-1