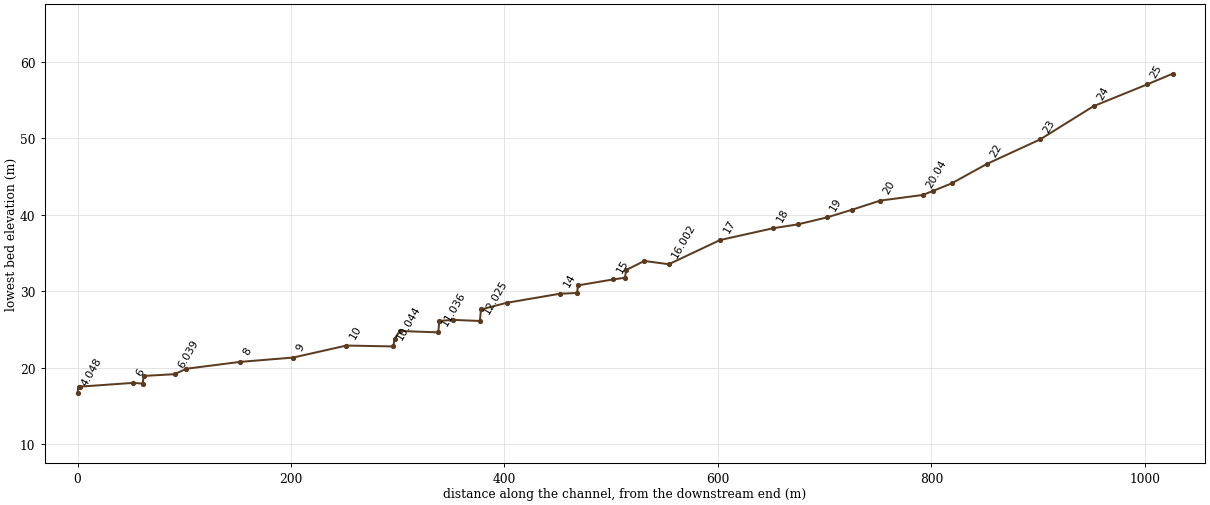
--- jejung-ch.prj (project) ---

Proj Title=jejung-ch
Current Plan=p01
Default Exp/Contr=.3,.1
SI Units
Geom File=g01
Flow File=f01
Plan File=p01
Y Axis Title=Elevation
X Axis Title(PF)=Main Channel Distance
X Axis Title(XS)=Station
BEGIN DESCRIPTION:
           BACK WATER COMPUTATION
      APPLICATION OF HEC-2 BY Samju Construction Engineering
      jejung-ch: 10,20,30,50,80 yr
END DESCRIPTION:
DSS Export Rating Curves= 0
DSS Export Rating Curve Sorted= 0
DSS Export Volume Flow Curves= 0
DXF OffsetX= 0
DXF OffsetY= 0
DXF ScaleX= 1
DXF ScaleY= 10

--- jejung-ch.p01 (plan) ---

Plan Title=Imported Plan 01
Version=Version 3.0.1  Mar 2001
Short Identifier=Imported Pla
Geom File=g01
Flow File=f01
Subcritical Flow
K Sum by GR= 0
Std Step Tol= 0.003
Critical Tol= 0.003
Num of Std Step Trials= 20
Max Error Tol= 0.1
Flow Tol Ratio= 0.001
Split Flow NTrial= 30
Split Flow Tol= 0.02
Split Flow Ratio= 0.02
Log Output Level= 0
Friction Slope Method= 1
Unsteady Friction Slope Method= 2
Parabolic Critical Depth
Global Vel Dist= 0 , 0 , 0
Global Log Level= 0
CheckData=True
Encroach Param=-1 ,0,0, 0
Computation Interval=1HOUR
Output Interval=1HOUR
Run HTab= 0
Run UNet= 0
Run PostProcess= 0
UNET Theta= 1
UNET ZTol= 0.02
UNET ZSATol= 0.1
UNET MxIter= 20
UNET MaxInSteps= 20
UNET DtIC= 0
UNET DtMin= 0
UNET MaxCRTS= 20
UNET WFStab= 2
UNET SFStab= 1
UNET WFX= 1
UNET SFX= 1
UNET Convert EG Bridges=-1
UNET Use Existing IB Tables=-1
Instantaneous Interval=1HOUR
Write IC File= 0
Write Velocity= 0
Write Detailed= 0

--- jejung-ch.f01 (steady flow) ---

Flow Title=Imported Flow 01
Version=Version 3.0.1  Mar 2001
Number of Profiles= 5
Profile Names=PF 1,PF 2,PF 3,PF 4,PF 5
River Rch & RM=RIVER-1,Reach-1         ,25.024
     180     200     220     230     240
Boundary for River Rch & Prof#=RIVER-1,Reach-1         , 1
Up Type= 0
Dn Type= 3
Dn Slope=.0109
Boundary for River Rch & Prof#=RIVER-1,Reach-1         , 2
Up Type= 0
Dn Type= 3
Dn Slope=.0109
Boundary for River Rch & Prof#=RIVER-1,Reach-1         , 3
Up Type= 0
Dn Type= 3
Dn Slope=.0109
Boundary for River Rch & Prof#=RIVER-1,Reach-1         , 4
Up Type= 0
Dn Type= 3
Dn Slope=.0109
Boundary for River Rch & Prof#=RIVER-1,Reach-1         , 5
Up Type= 0
Dn Type= 3
Dn Slope=.0109
DSS Import GetInterval= 0
DSS Import GetPeak= 0
DSS Import FillOption= 0

--- jejung-ch.g01 (geometry) ---

Geom Title=Imported Geom 01
Version=Version 3.0.1  Mar 2001

River Reach=RIVER-1         ,Reach-1
Reach XY= 2
              .5             .95              .5             .05

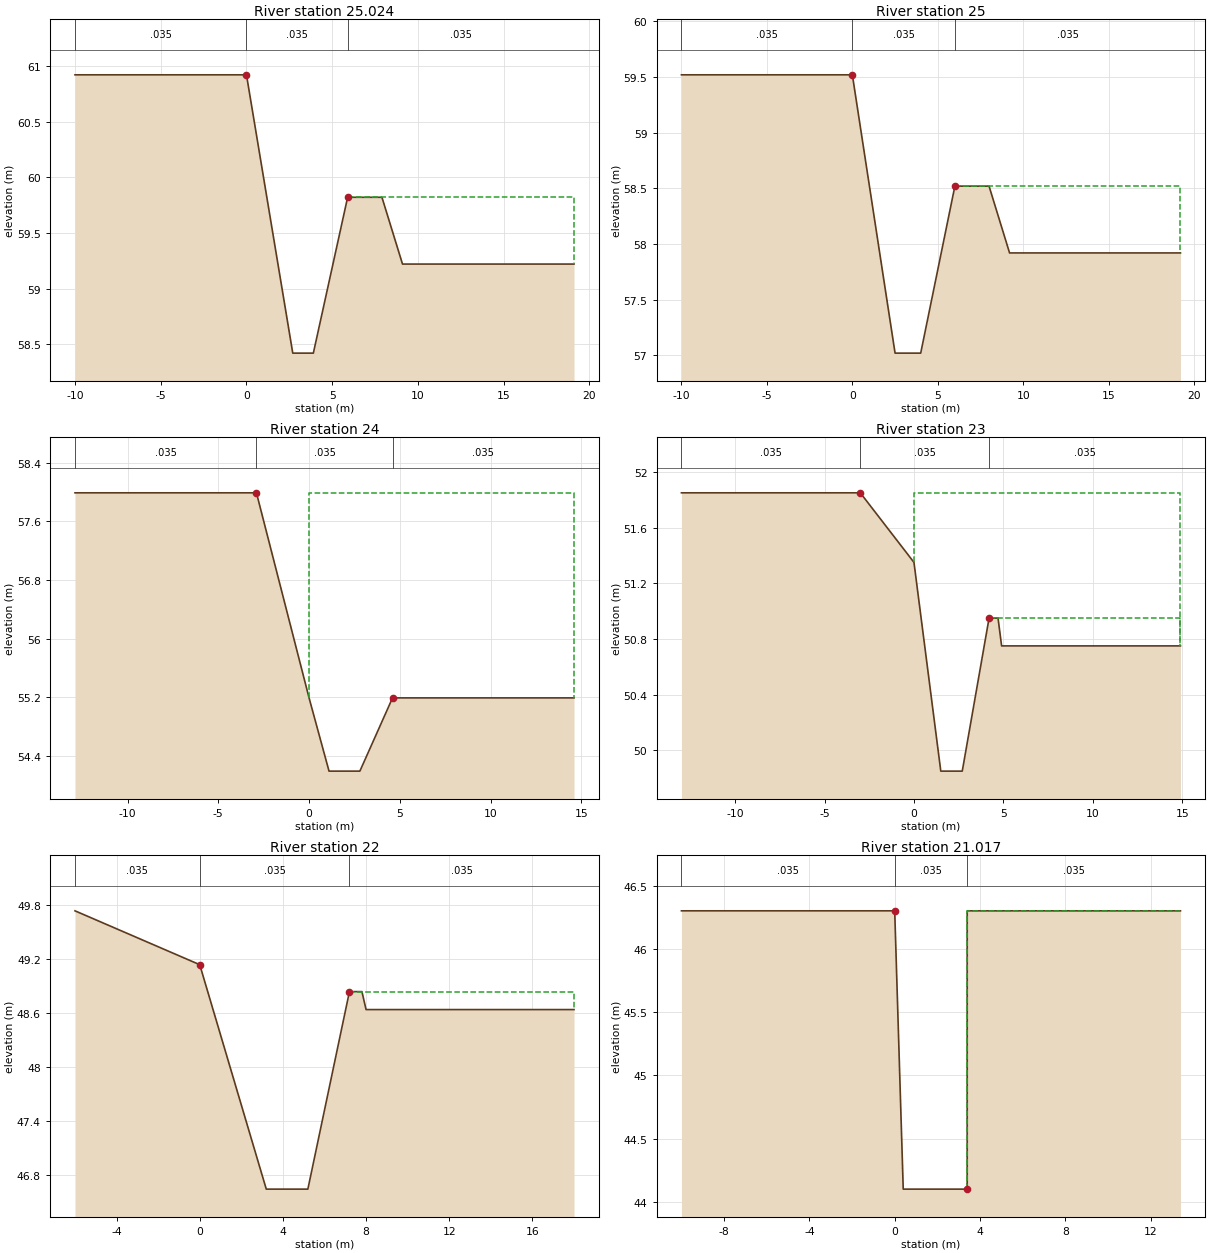
Type RM Length L Ch R = 1 ,25.024  ,24,24,24
#Sta/Elev= 8
     -10   60.92       0   60.92     2.7   58.42     3.9   58.42     5.9   59.82
     7.9   59.82     9.1   59.22    19.1   59.22
#Mann= 3 , 0 , 0
     -10    .035       0       0    .035       0     5.9    .035       0
#XS Ineff= 2 , 0
               0   60.92     5.9           59.82
Permanent Ineff=
       F       F
Bank Sta=0,5.9
XS Rating Curve= 0
Exp/Cntr=.3,.1

Type RM Length L Ch R = 1 ,25      ,50,50,50
#Sta/Elev= 8
     -10   59.52       0   59.52     2.5   57.02       4   57.02       6   58.52
       8   58.52     9.2   57.92    19.2   57.92
#Mann= 3 , 0 , 0
     -10    .035       0       0    .035       0       6    .035       0
#XS Ineff= 2 , 0
               0   59.52       6           58.52
Permanent Ineff=
       F       F
Bank Sta=0,6
XS Rating Curve= 0
Exp/Cntr=.3,.1

Type RM Length L Ch R = 1 ,24      ,50,50,50
#Sta/Elev= 7
   -12.9   57.99    -2.9   57.99       0   55.19     1.1   54.19     2.8   54.19
     4.6   55.19    14.6   55.19
#Mann= 3 , 0 , 0
   -12.9    .035       0    -2.9    .035       0     4.6    .035       0
#XS Ineff= 2 , 0
       0    -2.9   57.99     4.6       0   55.19
Permanent Ineff=
       F       F
Bank Sta=-2.9,4.6
XS Rating Curve= 0
Exp/Cntr=.3,.1

Type RM Length L Ch R = 1 ,23      ,50,50,50
#Sta/Elev= 9
     -13   51.85      -3   51.85       0   51.35     1.5   49.85     2.7   49.85
     4.2   50.95     4.7   50.95     4.9   50.75    14.9   50.75
#Mann= 3 , 0 , 0
     -13    .035       0      -3    .035       0     4.2    .035       0
#XS Ineff= 2 , 0
       0      -3   51.85     4.2       0   50.95
Permanent Ineff=
       F       F
Bank Sta=-3,4.2
XS Rating Curve= 0
Exp/Cntr=.3,.1

Type RM Length L Ch R = 1 ,22      ,33,33,33
#Sta/Elev= 9
      -6   49.74      -3   49.44       0   49.14     3.2   46.64     5.2   46.64
     7.2   48.84     7.8   48.84       8   48.64      18   48.64
#Mann= 3 , 0 , 0
      -6    .035       0       0    .035       0     7.2    .035       0
#XS Ineff= 2 , 0
               0   49.14     7.2           48.84
Permanent Ineff=
       F       F
Bank Sta=0,7.2
XS Rating Curve= 0
Exp/Cntr=.3,.1

Type RM Length L Ch R = 1 ,21.017  ,17,17,17
#Sta/Elev= 6
     -10    46.3       0    46.3      .4    44.1     3.4    44.1     3.4    46.3
    13.4    46.3
#Mann= 3 , 0 , 0
     -10    .035       0       0    .035       0     3.4    .035       0
#XS Ineff= 2 , 0
               0    46.3     3.4            46.3
Permanent Ineff=
       F       F
Bank Sta=0,3.4
XS Rating Curve= 0
Exp/Cntr=.3,.1

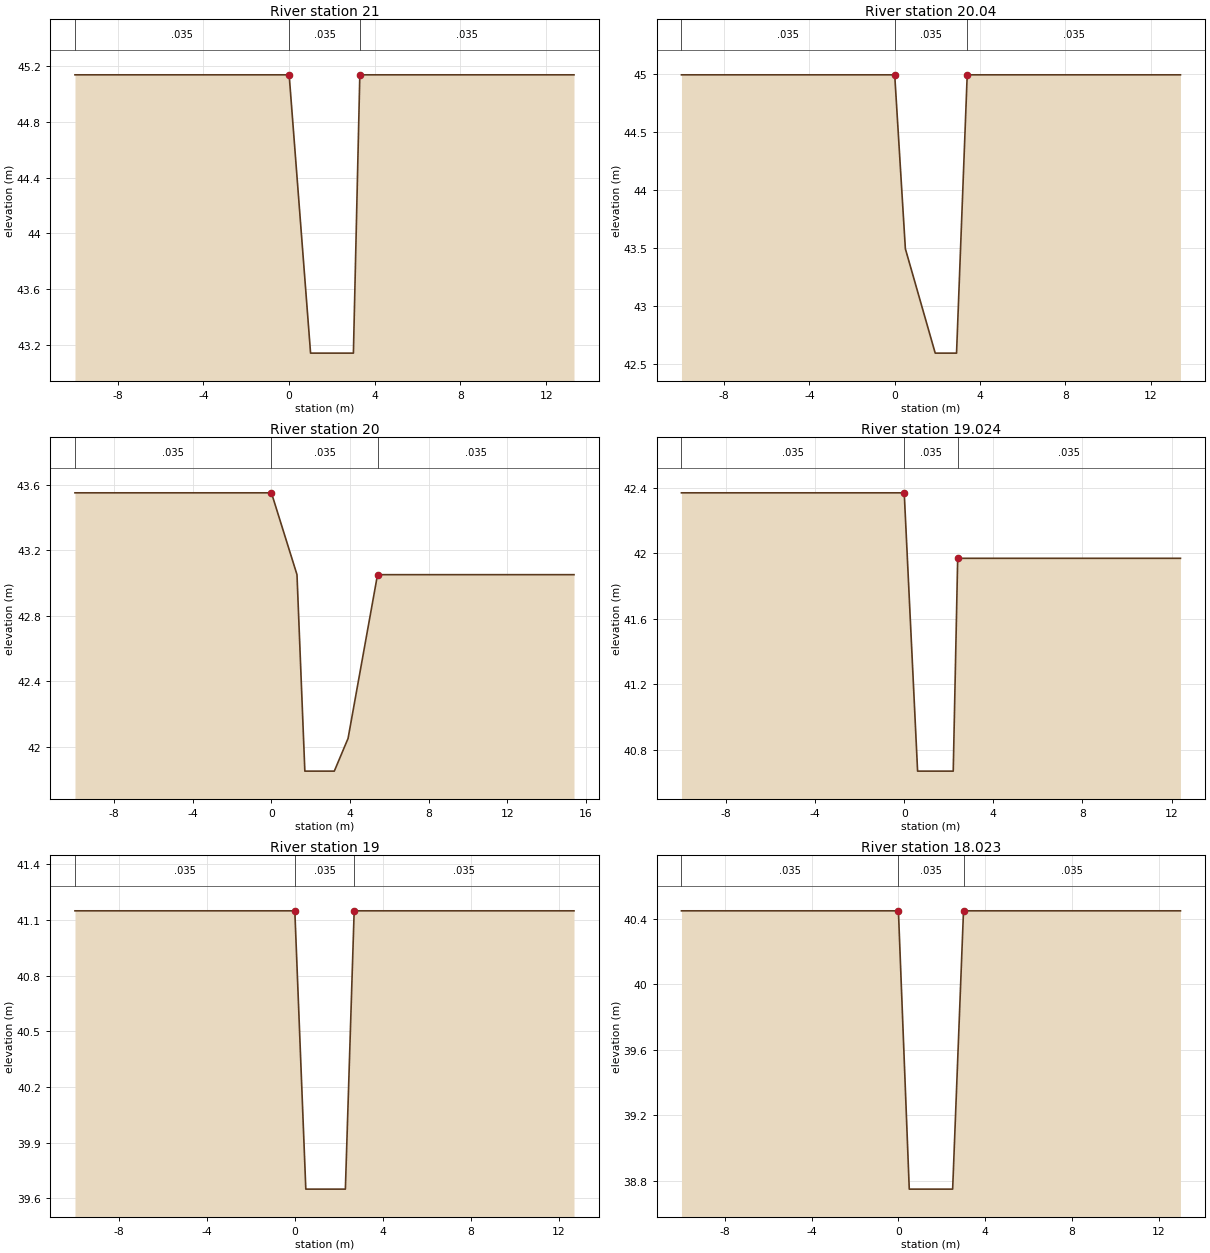
Type RM Length L Ch R = 1 ,21      ,10,10,10
#Sta/Elev= 6
     -10   45.14       0   45.14       1   43.14       3   43.14     3.3   45.14
    13.3   45.14
#Mann= 3 , 0 , 0
     -10    .035       0       0    .035       0     3.3    .035       0
#XS Ineff= 2 , 0
               0   45.14     3.3           45.14
Permanent Ineff=
       F       F
Bank Sta=0,3.3
XS Rating Curve= 0
Exp/Cntr=.3,.1

Type RM Length L Ch R = 1 ,20.04   ,40,40,40
#Sta/Elev= 7
     -10   44.99       0   44.99      .5   43.49     1.9   42.59     2.9   42.59
     3.4   44.99    13.4   44.99
#Mann= 3 , 0 , 0
     -10    .035       0       0    .035       0     3.4    .035       0
#XS Ineff= 2 , 0
               0   44.99     3.4           44.99
Permanent Ineff=
       F       F
Bank Sta=0,3.4
XS Rating Curve= 0
Exp/Cntr=.3,.1

Type RM Length L Ch R = 1 ,20      ,26,26,26
#Sta/Elev= 8
     -10   43.55       0   43.55     1.3   43.05     1.7   41.85     3.2   41.85
     3.9   42.05     5.4   43.05    15.4   43.05
#Mann= 3 , 0 , 0
     -10    .035       0       0    .035       0     5.4    .035       0
#XS Ineff= 2 , 0
               0   43.55     5.4           43.05
Permanent Ineff=
       F       F
Bank Sta=0,5.4
XS Rating Curve= 0
Exp/Cntr=.3,.1

Type RM Length L Ch R = 1 ,19.024  ,24,24,24
#Sta/Elev= 6
     -10   42.37       0   42.37      .6   40.67     2.2   40.67     2.4   41.97
    12.4   41.97
#Mann= 3 , 0 , 0
     -10    .035       0       0    .035       0     2.4    .035       0
#XS Ineff= 2 , 0
               0   42.37     2.4           41.97
Permanent Ineff=
       F       F
Bank Sta=0,2.4
XS Rating Curve= 0
Exp/Cntr=.3,.1

Type RM Length L Ch R = 1 ,19      ,27,27,27
#Sta/Elev= 6
     -10   41.15       0   41.15      .5   39.65     2.3   39.65     2.7   41.15
    12.7   41.15
#Mann= 3 , 0 , 0
     -10    .035       0       0    .035       0     2.7    .035       0
#XS Ineff= 2 , 0
               0   41.15     2.7           41.15
Permanent Ineff=
       F       F
Bank Sta=0,2.7
XS Rating Curve= 0
Exp/Cntr=.3,.1

Type RM Length L Ch R = 1 ,18.023  ,23,23,23
#Sta/Elev= 6
     -10   40.45       0   40.45      .5   38.75     2.5   38.75       3   40.45
      13   40.45
#Mann= 3 , 0 , 0
     -10    .035       0       0    .035       0       3    .035       0
#XS Ineff= 2 , 0
               0   40.45       3           40.45
Permanent Ineff=
       F       F
Bank Sta=0,3
XS Rating Curve= 0
Exp/Cntr=.3,.1

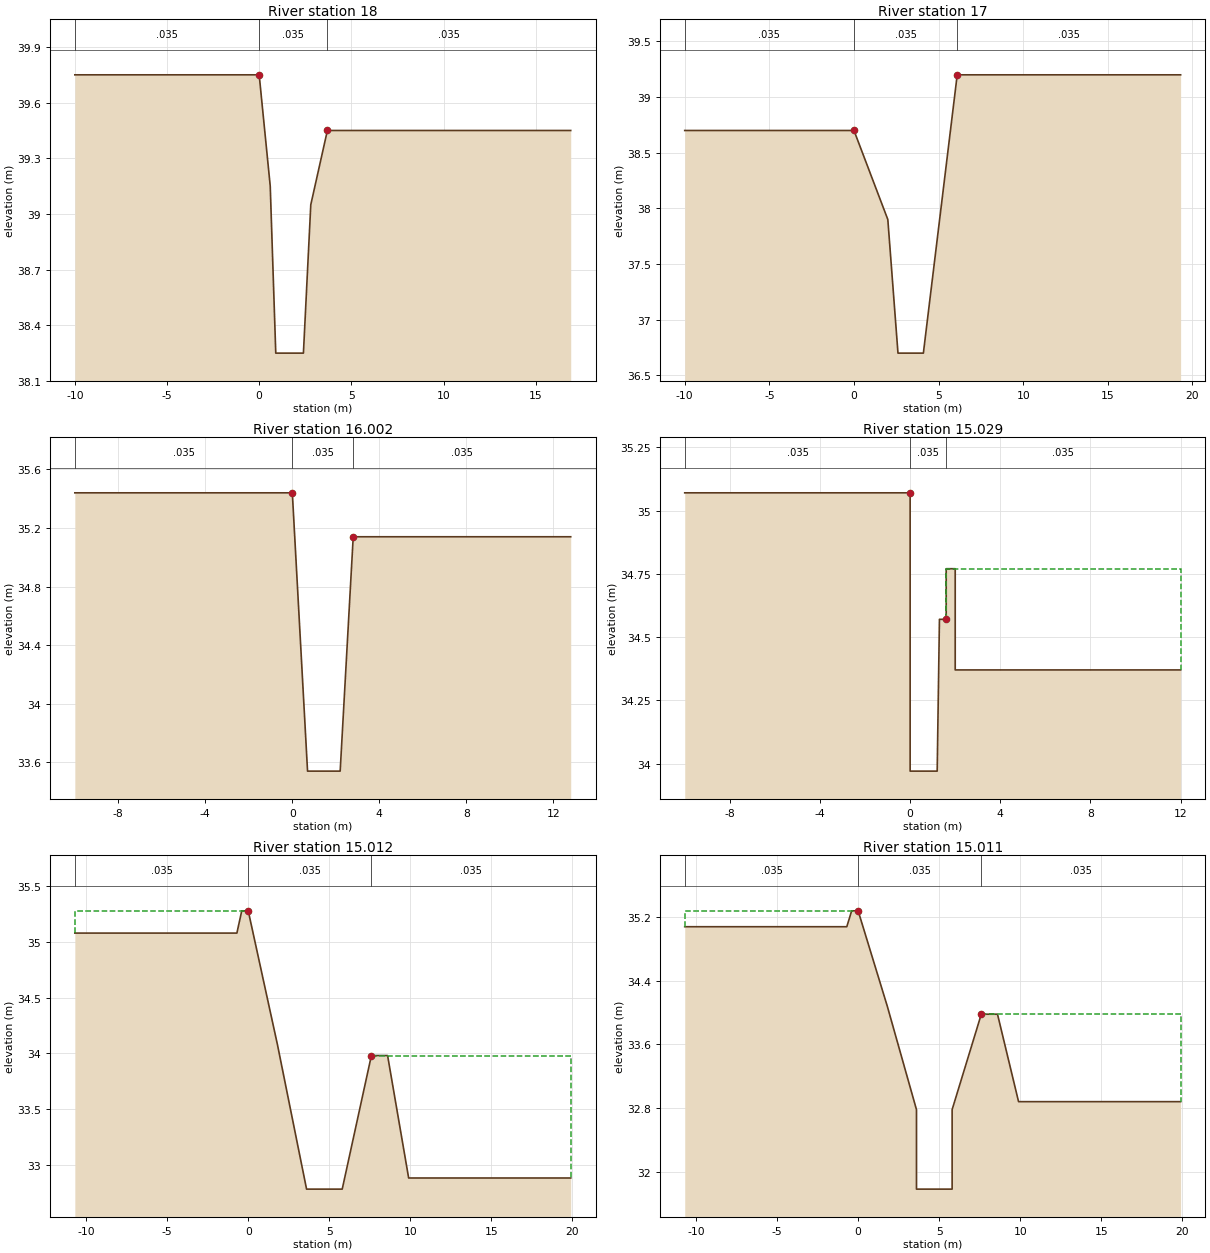
Type RM Length L Ch R = 1 ,18      ,50,50,50
#Sta/Elev= 9
     -10   39.75       0   39.75      .6   39.15      .9   38.25     2.4   38.25
     2.8   39.05     3.7   39.45     6.9   39.45    16.9   39.45
#Mann= 3 , 0 , 0
     -10    .035       0       0    .035       0     3.7    .035       0
#XS Ineff= 2 , 0
               0   39.75     3.7           39.45
Permanent Ineff=
       F       F
Bank Sta=0,3.7
XS Rating Curve= 0
Exp/Cntr=.3,.1

Type RM Length L Ch R = 1 ,17      ,48,48,48
#Sta/Elev= 8
     -10    38.7       0    38.7       2    37.9     2.6    36.7     4.1    36.7
     6.1    39.2     9.3    39.2    19.3    39.2
#Mann= 3 , 0 , 0
     -10    .035       0       0    .035       0     6.1    .035       0
#XS Ineff= 2 , 0
               0    38.7     6.1            39.2
Permanent Ineff=
       F       F
Bank Sta=0,6.1
XS Rating Curve= 0
Exp/Cntr=.3,.1

Type RM Length L Ch R = 1 ,16.002  ,23,23,23
#Sta/Elev= 7
     -10   35.44       0   35.44       0   35.44      .7   33.54     2.2   33.54
     2.8   35.14    12.8   35.14
#Mann= 3 , 0 , 0
     -10    .035       0       0    .035       0     2.8    .035       0
#XS Ineff= 2 , 0
               0   35.44     2.8           35.14
Permanent Ineff=
       F       F
Bank Sta=0,2.8
XS Rating Curve= 0
Exp/Cntr=.3,.1

Type RM Length L Ch R = 1 ,15.029  ,17,17,17
#Sta/Elev= 10
     -10   35.07       0   35.07       0   33.97     1.2   33.97     1.3   34.57
     1.6   34.57     1.6   34.77       2   34.77       2   34.37      12   34.37
#Mann= 3 , 0 , 0
     -10    .035       0       0    .035       0     1.6    .035       0
#XS Ineff= 2 , 0
               0   35.07     1.6           34.77
Permanent Ineff=
       F       F
Bank Sta=0,1.6
XS Rating Curve= 0
Exp/Cntr=.3,.1

Type RM Length L Ch R = 1 ,15.012  ,1,1,1
#Sta/Elev= 11
   -10.7   35.08     -.7   35.08     -.4   35.28       0   35.28     1.8   34.08
     3.6   32.78     5.8   32.78     7.6   33.98     8.6   33.98     9.9   32.88
    19.9   32.88
#Mann= 3 , 0 , 0
   -10.7    .035       0       0    .035       0     7.6    .035       0
#XS Ineff= 2 , 0
               0   35.28     7.6           33.98
Permanent Ineff=
       F       F
Bank Sta=0,7.6
XS Rating Curve= 0
Exp/Cntr=.3,.1

Type RM Length L Ch R = 1 ,15.011  ,11,11,11
#Sta/Elev= 13
   -10.7   35.08     -.7   35.08     -.4   35.28       0   35.28     1.8   34.08
     3.6   32.78     3.6   31.78     5.8   31.78     5.8   32.78     7.6   33.98
     8.6   33.98     9.9   32.88    19.9   32.88
#Mann= 3 , 0 , 0
   -10.7    .035       0       0    .035       0     7.6    .035       0
#XS Ineff= 2 , 0
               0   35.28     7.6           33.98
Permanent Ineff=
       F       F
Bank Sta=0,7.6
XS Rating Curve= 0
Exp/Cntr=.3,.1

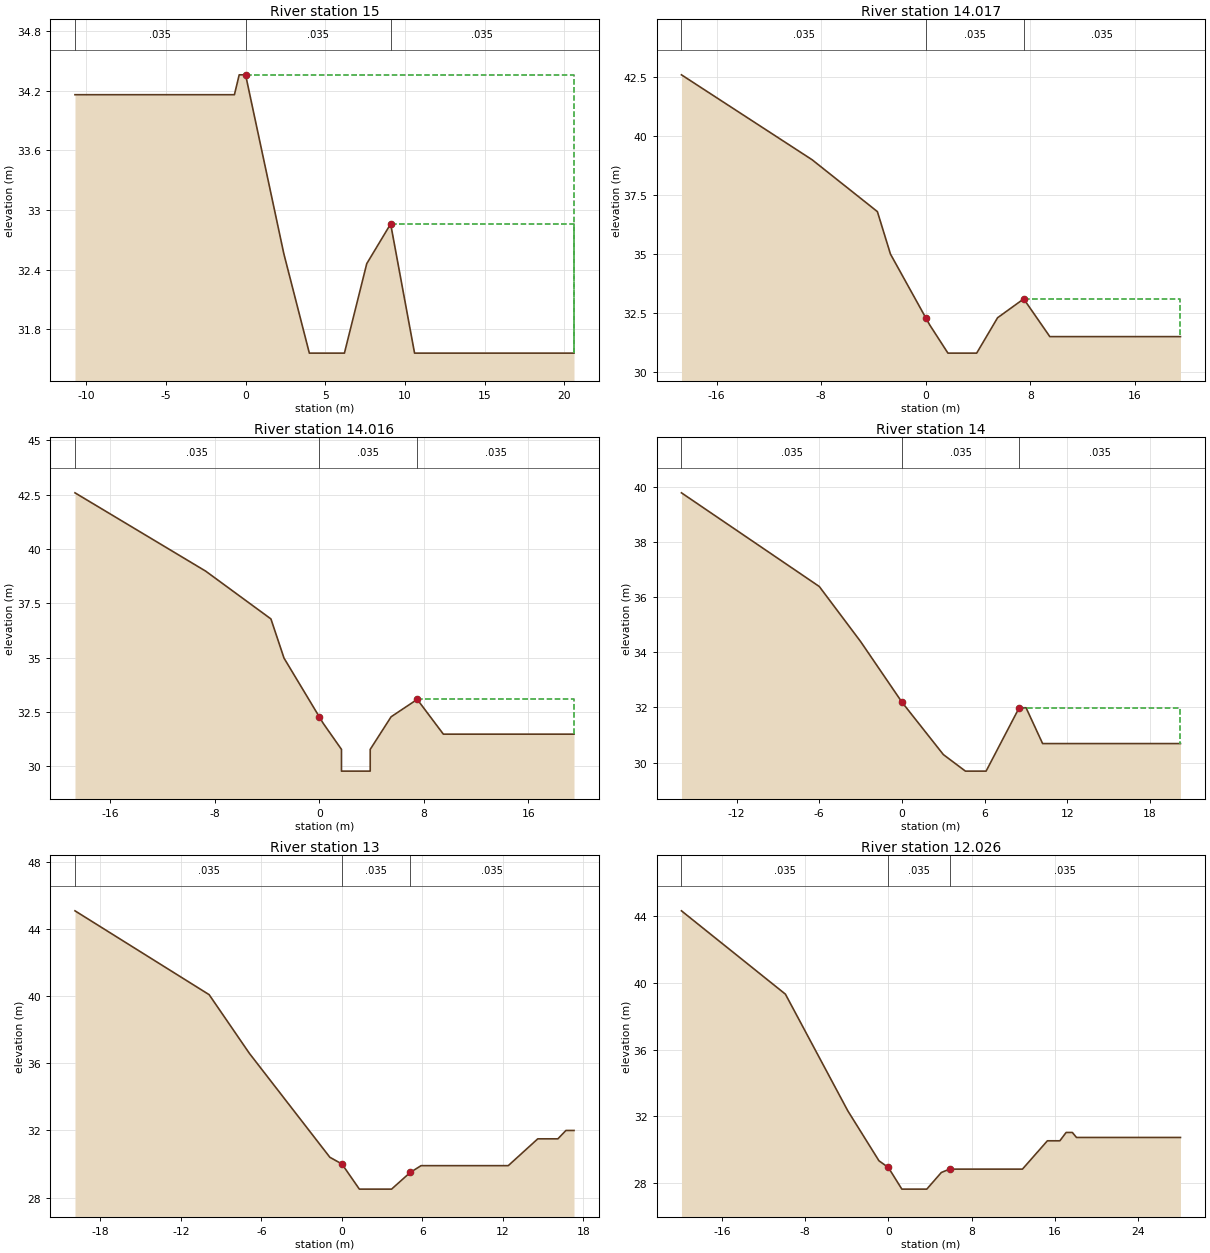
Type RM Length L Ch R = 1 ,15      ,33,33,33
#Sta/Elev= 11
   -10.7   34.16     -.7   34.16     -.4   34.36       0   34.36     2.4   32.56
       4   31.56     6.2   31.56     7.6   32.46     9.1   32.86    10.6   31.56
    20.6   31.56
#Mann= 3 , 0 , 0
   -10.7    .035       0       0    .035       0     9.1    .035       0
#XS Ineff= 2 , 0
       0       0   34.36     9.1       0   32.86
Permanent Ineff=
       F       F
Bank Sta=0,9.1
XS Rating Curve= 0
Exp/Cntr=.3,.1

Type RM Length L Ch R = 1 ,14.017  ,1,1,1
#Sta/Elev= 13
   -18.7   42.58   -13.7   40.78    -8.7   38.98    -3.7   36.78    -2.7   34.98
       0   32.28      .3   31.98     1.7   30.78     3.9   30.78     5.5   32.28
     7.5   33.08     9.5   31.48    19.5   31.48
#Mann= 3 , 0 , 0
   -18.7    .035       0       0    .035       0     7.5    .035       0
#XS Ineff= 2 , 0
               0   32.28     7.5           33.08
Permanent Ineff=
       F       F
Bank Sta=0,7.5
XS Rating Curve= 0
Exp/Cntr=.3,.1

Type RM Length L Ch R = 1 ,14.016  ,16,16,16
#Sta/Elev= 15
   -18.7   42.58   -13.7   40.78    -8.7   38.98    -3.7   36.78    -2.7   34.98
       0   32.28      .3   31.98     1.7   30.78     1.7   29.78     3.9   29.78
     3.9   30.78     5.5   32.28     7.5   33.08     9.5   31.48    19.5   31.48
#Mann= 3 , 0 , 0
   -18.7    .035       0       0    .035       0     7.5    .035       0
#XS Ineff= 2 , 0
               0   32.28     7.5           33.08
Permanent Ineff=
       F       F
Bank Sta=0,7.5
XS Rating Curve= 0
Exp/Cntr=.3,.1

Type RM Length L Ch R = 1 ,14      ,50,50,50
#Sta/Elev= 12
     -16   39.79     -11   38.09      -6   36.39      -3   34.39       0   32.19
       3   30.29     4.6   29.69     6.1   29.69     8.5   31.99       9   31.99
    10.2   30.69    20.2   30.69
#Mann= 3 , 0 , 0
     -16    .035       0       0    .035       0     8.5    .035       0
#XS Ineff= 2 , 0
               0   32.19     8.5           31.99
Permanent Ineff=
       F       F
Bank Sta=0,8.5
XS Rating Curve= 0
Exp/Cntr=.3,.1

Type RM Length L Ch R = 1 ,13      ,24,24,24
#Sta/Elev= 15
   -19.9    45.1   -14.9    42.6    -9.9    40.1    -6.9    36.6     -.9    30.4
       0      30     1.3    28.5     3.7    28.5     5.1    29.5     5.9    29.9
    12.4    29.9    14.6    31.5    16.1    31.5    16.7      32    17.3      32
#Mann= 3 , 0 , 0
   -19.9    .035       0       0    .035       0     5.1    .035       0
#XS Ineff= 2 , 0
               0      30     5.1            29.5
Permanent Ineff=
       F       F
Bank Sta=0,5.1
XS Rating Curve= 0
Exp/Cntr=.3,.1

Type RM Length L Ch R = 1 ,12.026  ,1,1,1
#Sta/Elev= 18
   -19.9   44.33   -14.9   41.83    -9.9   39.33    -6.9   35.83    -3.9   32.33
     -.9   29.33       0   28.93     1.3   27.63     3.7   27.63     5.1   28.63
     5.9   28.83    12.9   28.83    15.3   30.53    16.5   30.53    17.1   31.03
    17.7   31.03    18.1   30.73    28.1   30.73
#Mann= 3 , 0 , 0
   -19.9    .035       0       0    .035       0     5.9    .035       0
#XS Ineff= 2 , 0
               0   28.93     5.9           28.83
Permanent Ineff=
       F       F
Bank Sta=0,5.9
XS Rating Curve= 0
Exp/Cntr=.3,.1

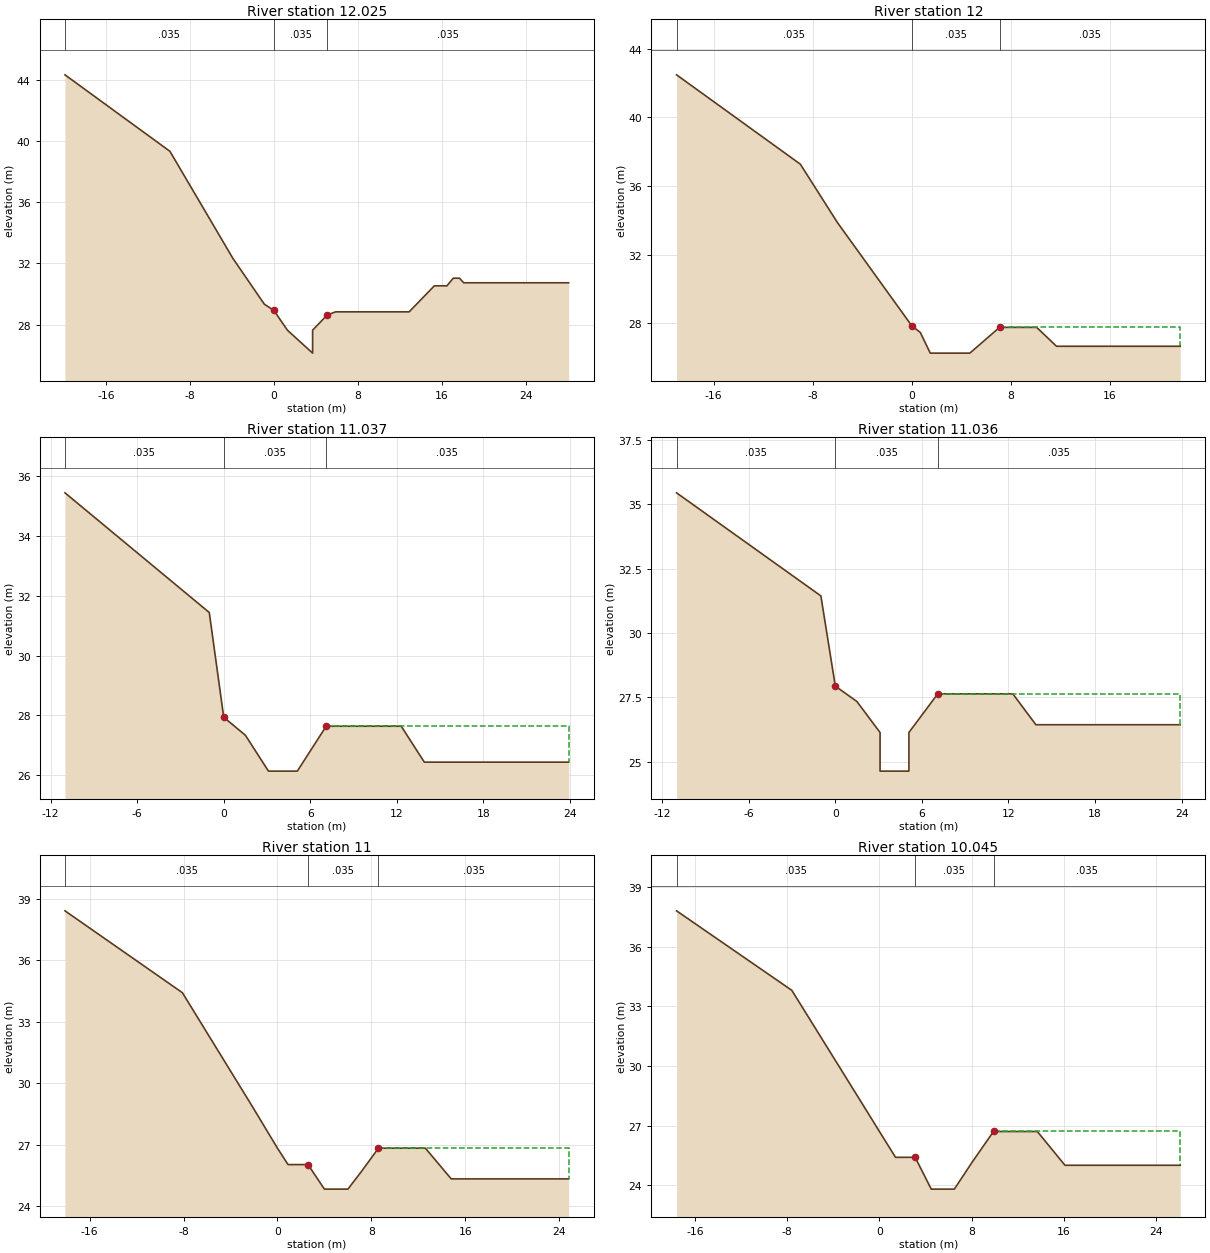
Type RM Length L Ch R = 1 ,12.025  ,25,25,25
#Sta/Elev= 19
   -19.9   44.33   -14.9   41.83    -9.9   39.33    -6.9   35.83    -3.9   32.33
     -.9   29.33       0   28.93     1.3   27.63     3.7   26.13     3.7   27.63
     5.1   28.63     5.9   28.83    12.9   28.83    15.3   30.53    16.5   30.53
    17.1   31.03    17.7   31.03    18.1   30.73    28.1   30.73
#Mann= 3 , 0 , 0
   -19.9    .035       0       0    .035       0     5.1    .035       0
#XS Ineff= 2 , 0
       0       0   28.93     5.1       0   28.63
Permanent Ineff=
       F       F
Bank Sta=0,5.1
XS Rating Curve= 0
Exp/Cntr=.3,.1

Type RM Length L Ch R = 1 ,12      ,13,13,13
#Sta/Elev= 13
     -19   42.47     -14   39.87      -9   37.27      -6   33.87      -3   30.87
       0   27.87      .7   27.47     1.5   26.27     4.7   26.27     7.1   27.77
    10.1   27.77    11.7   26.67    21.7   26.67
#Mann= 3 , 0 , 0
     -19    .035       0       0    .035       0     7.1    .035       0
#XS Ineff= 2 , 0
               0   27.87     7.1           27.77
Permanent Ineff=
       F       F
Bank Sta=0,7.1
XS Rating Curve= 0
Exp/Cntr=.3,.1

Type RM Length L Ch R = 1 ,11.037  ,1,1,1
#Sta/Elev= 11
     -11   35.44      -6   33.44      -1   31.44       0   27.94     1.5   27.34
     3.1   26.14     5.1   26.14     7.1   27.64    12.3   27.64    13.9   26.44
    23.9   26.44
#Mann= 3 , 0 , 0
     -11    .035       0       0    .035       0     7.1    .035       0
#XS Ineff= 2 , 0
               0   27.94     7.1           27.64
Permanent Ineff=
       F       F
Bank Sta=0,7.1
XS Rating Curve= 0
Exp/Cntr=.3,.1

Type RM Length L Ch R = 1 ,11.036  ,36,36,36
#Sta/Elev= 13
     -11   35.44      -6   33.44      -1   31.44       0   27.94     1.5   27.34
     3.1   26.14     3.1   24.64     5.1   24.64     5.1   26.14     7.1   27.64
    12.3   27.64    13.9   26.44    23.9   26.44
#Mann= 3 , 0 , 0
     -11    .035       0       0    .035       0     7.1    .035       0
#XS Ineff= 2 , 0
               0   27.94     7.1           27.64
Permanent Ineff=
       F       F
Bank Sta=0,7.1
XS Rating Curve= 0
Exp/Cntr=.3,.1

Type RM Length L Ch R = 1 ,11      ,5,5,5
#Sta/Elev= 14
   -18.1   38.42   -13.1   36.42    -8.1   34.42    -2.1   28.82       0   26.82
      .9   26.02     2.6   26.02       4   24.82       6   24.82     7.2   25.72
     8.6   26.82    12.6   26.82    14.8   25.32    24.8   25.32
#Mann= 3 , 0 , 0
   -18.1    .035       0     2.6    .035       0     8.6    .035       0
#XS Ineff= 2 , 0
       0     2.6   26.02     8.6       0   26.82
Permanent Ineff=
       F       F
Bank Sta=2.6,8.6
XS Rating Curve= 0
Exp/Cntr=.3,.1

Type RM Length L Ch R = 1 ,10.045  ,1,1,1
#Sta/Elev= 15
   -17.6    37.8   -12.6    35.8    -7.6    33.8    -4.6      31    -1.6    28.2
       0    26.7     1.4    25.4     3.1    25.4     4.5    23.8     6.5    23.8
     8.1    25.2     9.9    26.7    13.7    26.7    16.1      25    26.1      25
#Mann= 3 , 0 , 0
   -17.6    .035       0     3.1    .035       0     9.9    .035       0
#XS Ineff= 2 , 0
       0     3.1    25.4     9.9       0    26.7
Permanent Ineff=
       F       F
Bank Sta=3.1,9.9
XS Rating Curve= 0
Exp/Cntr=.3,.1

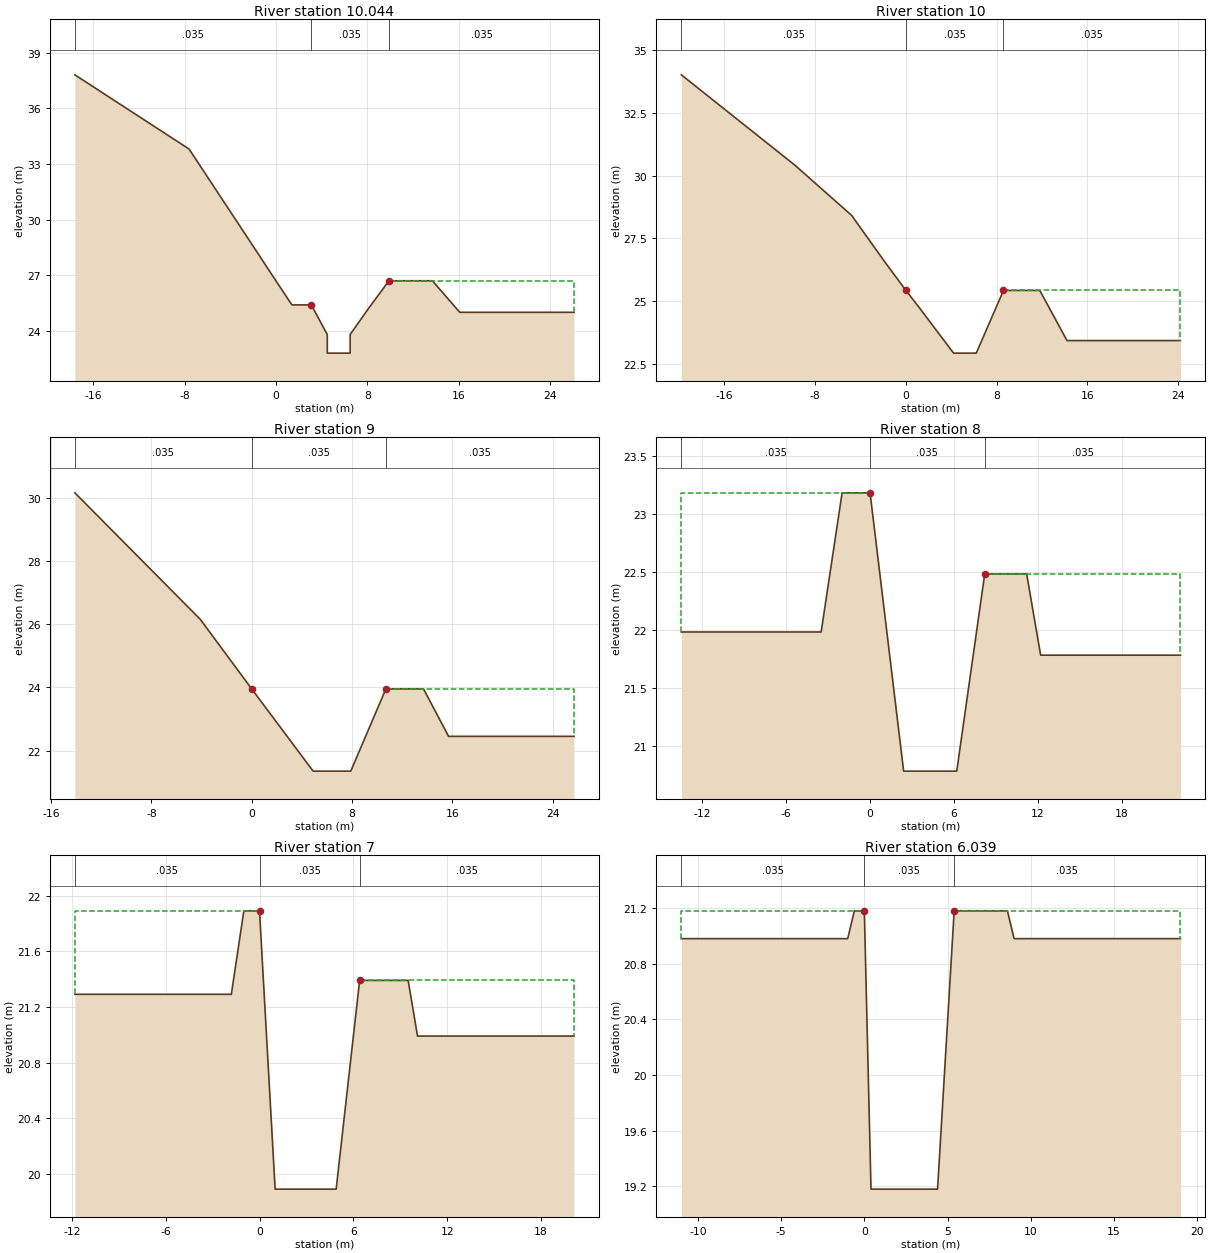
Type RM Length L Ch R = 1 ,10.044  ,44,44,44
#Sta/Elev= 17
   -17.6    37.8   -12.6    35.8    -7.6    33.8    -4.6      31    -1.6    28.2
       0    26.7     1.4    25.4     3.1    25.4     4.5    23.8     4.5    22.8
     6.5    22.8     6.5    23.8     8.1    25.2     9.9    26.7    13.7    26.7
    16.1      25    26.1      25
#Mann= 3 , 0 , 0
   -17.6    .035       0     3.1    .035       0     9.9    .035       0
#XS Ineff= 2 , 0
       0     3.1    25.4     9.9       0    26.7
Permanent Ineff=
       F       F
Bank Sta=3.1,9.9
XS Rating Curve= 0
Exp/Cntr=.3,.1

Type RM Length L Ch R = 1 ,10      ,50,50,50
#Sta/Elev= 13
   -19.8   34.02   -14.8   32.22    -9.8   30.42    -4.8   28.42    -1.8   26.52
       0   25.42     1.2   24.72     4.2   22.92     6.2   22.92     8.6   25.42
    11.8   25.42    14.2   23.42    24.2   23.42
#Mann= 3 , 0 , 0
   -19.8    .035       0       0    .035       0     8.6    .035       0
#XS Ineff= 2 , 0
               0   25.42     8.6           25.42
Permanent Ineff=
       F       F
Bank Sta=0,8.6
XS Rating Curve= 0
Exp/Cntr=.3,.1

Type RM Length L Ch R = 1 ,9       ,50,50,50
#Sta/Elev= 10
   -14.1   30.15    -9.1   28.15    -4.1   26.15       0   23.95     4.9   21.35
     7.9   21.35    10.7   23.95    13.7   23.95    15.7   22.45    25.7   22.45
#Mann= 3 , 0 , 0
   -14.1    .035       0       0    .035       0    10.7    .035       0
#XS Ineff= 2 , 0
               0   23.95    10.7           23.95
Permanent Ineff=
       F       F
Bank Sta=0,10.7
XS Rating Curve= 0
Exp/Cntr=.3,.1

Type RM Length L Ch R = 1 ,8       ,50,50,50
#Sta/Elev= 10
   -13.5   21.98    -3.5   21.98      -2   23.18       0   23.18     2.4   20.78
     6.2   20.78     8.2   22.48    11.2   22.48    12.2   21.78    22.2   21.78
#Mann= 3 , 0 , 0
   -13.5    .035       0       0    .035       0     8.2    .035       0
#XS Ineff= 2 , 0
               0   23.18     8.2           22.48
Permanent Ineff=
       F       F
Bank Sta=0,8.2
XS Rating Curve= 0
Exp/Cntr=.3,.1

Type RM Length L Ch R = 1 ,7       ,11,11,11
#Sta/Elev= 10
   -11.8   21.29    -1.8   21.29      -1   21.89       0   21.89       1   19.89
     4.9   19.89     6.4   21.39     9.5   21.39    10.1   20.99    20.1   20.99
#Mann= 3 , 0 , 0
   -11.8    .035       0       0    .035       0     6.4    .035       0
#XS Ineff= 2 , 0
               0   21.89     6.4           21.39
Permanent Ineff=
       F       F
Bank Sta=0,6.4
XS Rating Curve= 0
Exp/Cntr=.3,.1

Type RM Length L Ch R = 1 ,6.039   ,29,29,29
#Sta/Elev= 10
     -11   20.98      -1   20.98     -.6   21.18       0   21.18      .4   19.18
     4.4   19.18     5.4   21.18     8.6   21.18       9   20.98      19   20.98
#Mann= 3 , 0 , 0
     -11    .035       0       0    .035       0     5.4    .035       0
#XS Ineff= 2 , 0
               0   21.18     5.4           21.18
Permanent Ineff=
       F       F
Bank Sta=0,5.4
XS Rating Curve= 0
Exp/Cntr=.3,.1

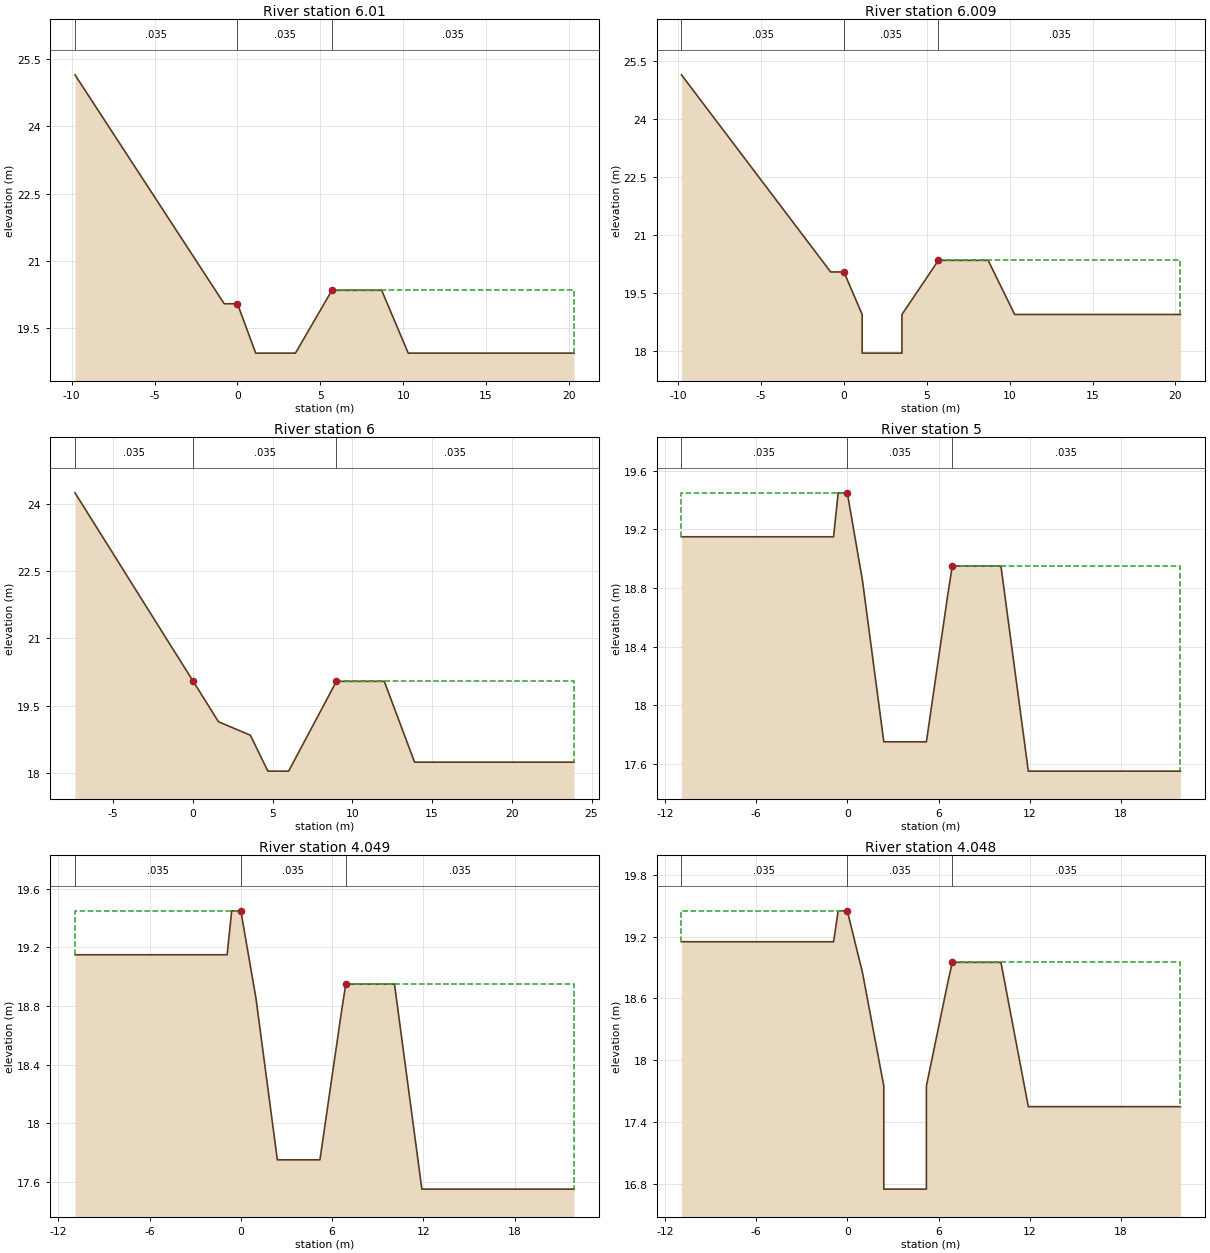
Type RM Length L Ch R = 1 ,6.01    ,1,1,1
#Sta/Elev= 11
    -9.8   25.15    -6.8   23.45    -3.8   21.75     -.8   20.05       0   20.05
     1.1   18.95     3.5   18.95     5.7   20.35     8.7   20.35    10.3   18.95
    20.3   18.95
#Mann= 3 , 0 , 0
    -9.8    .035       0       0    .035       0     5.7    .035       0
#XS Ineff= 2 , 0
               0   20.05     5.7           20.35
Permanent Ineff=
       F       F
Bank Sta=0,5.7
XS Rating Curve= 0
Exp/Cntr=.3,.1

Type RM Length L Ch R = 1 ,6.009   ,9,9,9
#Sta/Elev= 13
    -9.8   25.15    -6.8   23.45    -3.8   21.75     -.8   20.05       0   20.05
     1.1   18.95     1.1   17.95     3.5   17.95     3.5   18.95     5.7   20.35
     8.7   20.35    10.3   18.95    20.3   18.95
#Mann= 3 , 0 , 0
    -9.8    .035       0       0    .035       0     5.7    .035       0
#XS Ineff= 2 , 0
               0   20.05     5.7           20.35
Permanent Ineff=
       F       F
Bank Sta=0,5.7
XS Rating Curve= 0
Exp/Cntr=.3,.1

Type RM Length L Ch R = 1 ,6       ,50,50,50
#Sta/Elev= 12
    -7.4   24.24    -4.4   22.54    -1.4   20.84       0   20.05     1.6   19.14
     3.6   18.84     4.7   18.04       6   18.04       9   20.04      12   20.04
    13.9   18.24    23.9   18.24
#Mann= 3 , 0 , 0
    -7.4    .035       0       0    .035       0       9    .035       0
#XS Ineff= 2 , 0
               0   20.05       9           20.04
Permanent Ineff=
       F       F
Bank Sta=0,9
XS Rating Curve= 0
Exp/Cntr=.3,.1

Type RM Length L Ch R = 1 ,5       ,1,1,1
#Sta/Elev= 12
   -10.9   19.15     -.9   19.15     -.6   19.45       0   19.45       1   18.85
     2.4   17.75     5.2   17.75     6.6   18.75     6.9   18.95    10.1   18.95
    11.9   17.55    21.9   17.55
#Mann= 3 , 0 , 0
   -10.9    .035       0       0    .035       0     6.9    .035       0
#XS Ineff= 2 , 0
               0   19.45     6.9           18.95
Permanent Ineff=
       F       F
Bank Sta=0,6.9
XS Rating Curve= 0
Exp/Cntr=.3,.1

Type RM Length L Ch R = 1 ,4.049   ,1,1,1
#Sta/Elev= 12
   -10.9   19.15     -.9   19.15     -.6   19.45       0   19.45       1   18.85
     2.4   17.75     5.2   17.75     6.6   18.75     6.9   18.95    10.1   18.95
    11.9   17.55    21.9   17.55
#Mann= 3 , 0 , 0
   -10.9    .035       0       0    .035       0     6.9    .035       0
#XS Ineff= 2 , 0
               0   19.45     6.9           18.95
Permanent Ineff=
       F       F
Bank Sta=0,6.9
XS Rating Curve= 0
Exp/Cntr=.3,.1

Type RM Length L Ch R = 1 ,4.048   ,48,48,48
#Sta/Elev= 14
   -10.9   19.15     -.9   19.15     -.6   19.45       0   19.45       1   18.85
     2.4   17.75     2.4   16.75     5.2   16.75     5.2   17.75     6.6   18.75
     6.9   18.95    10.1   18.95    11.9   17.55    21.9   17.55
#Mann= 3 , 0 , 0
   -10.9    .035       0       0    .035       0     6.9    .035       0
#XS Ineff= 2 , 0
               0   19.45     6.9           18.95
Permanent Ineff=
       F       F
Bank Sta=0,6.9
XS Rating Curve= 0
Exp/Cntr=.3,.1