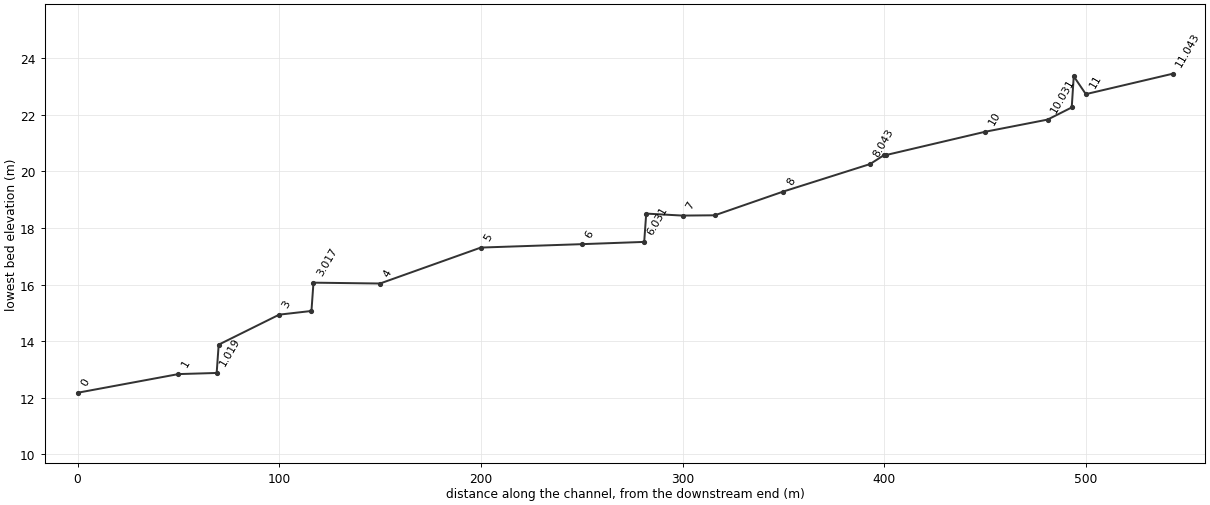
HEC-RAS study nungsin-ch.prj: nungsin-ch

--- nungsin-ch.g01 (geometry) --- (continued)

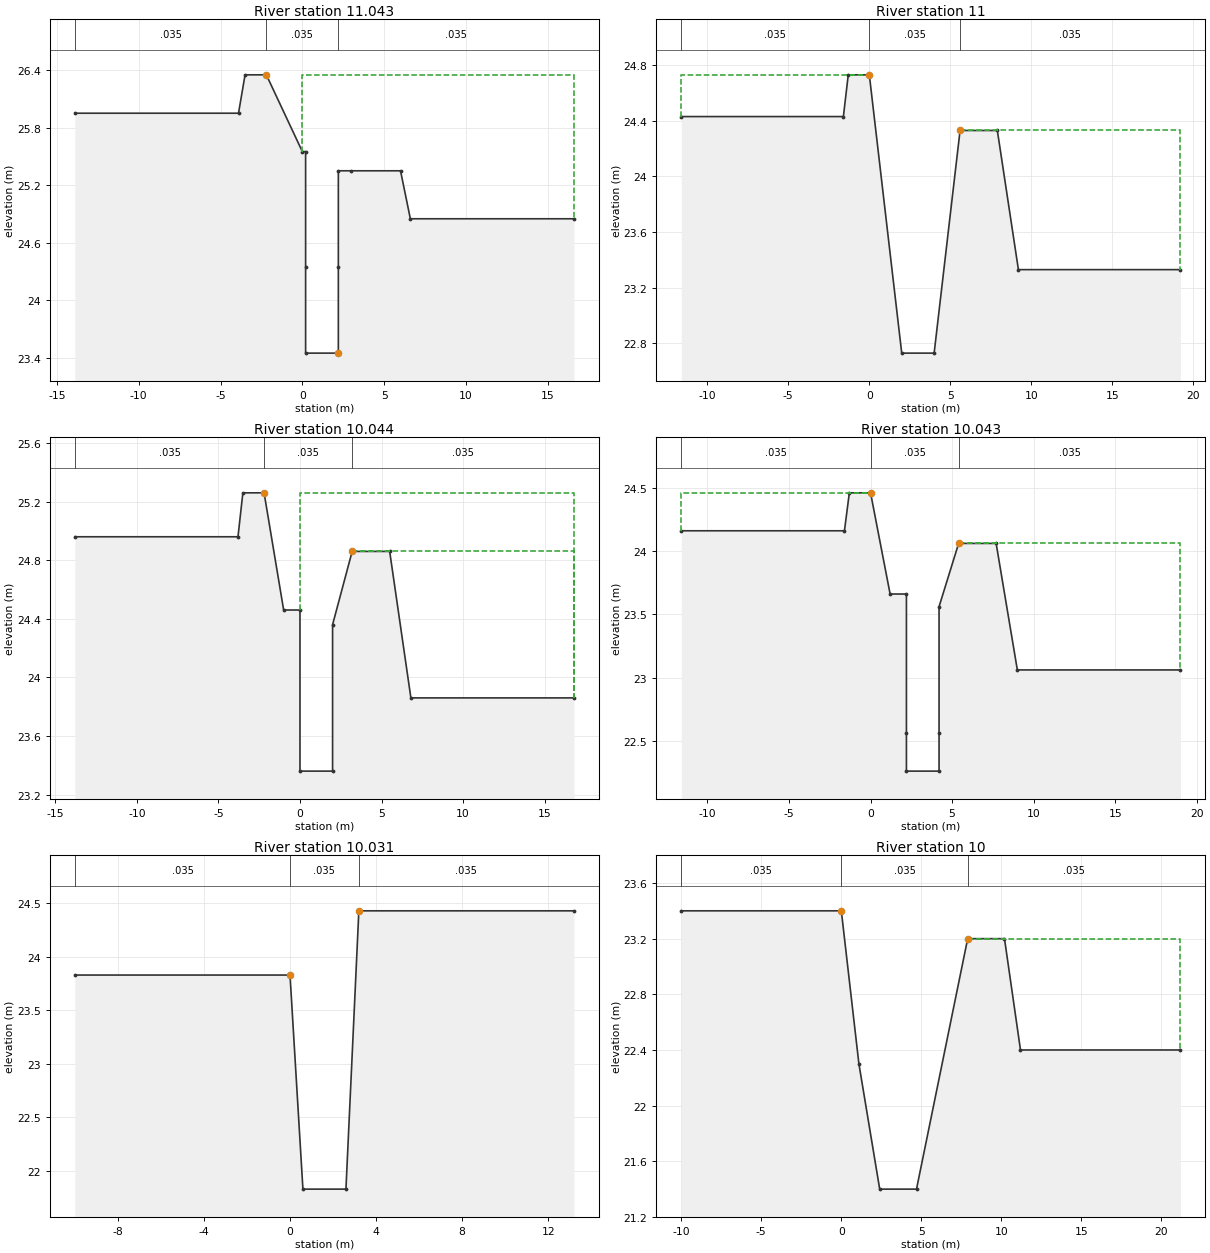
Type RM Length L Ch R = 1 ,11.043  ,43,43,43
#Sta/Elev= 15
   -13.9   25.95    -3.9   25.95    -3.5   26.35    -2.2   26.35       0   25.55
      .2   25.55      .2   24.35      .2   23.45     2.2   23.45     2.2   24.35
     2.2   25.35       3   25.35       6   25.35     6.6   24.85    16.6   24.85
#Mann= 3 , 0 , 0
   -13.9    .035       0    -2.2    .035       0     2.2    .035       0
#XS Ineff= 2 , 0
       0    -2.2   26.35     2.2       0   23.45
Permanent Ineff=
       F       F
Bank Sta=-2.2,2.2
XS Rating Curve= 0
Exp/Cntr=.3,.1

Type RM Length L Ch R = 1 ,11      ,6,6,6
#Sta/Elev= 10
   -11.6   24.43    -1.6   24.43    -1.3   24.73       0   24.73       2   22.73
       4   22.73     5.6   24.33     7.9   24.33     9.2   23.33    19.2   23.33
#Mann= 3 , 0 , 0
   -11.6    .035       0       0    .035       0     5.6    .035       0
#XS Ineff= 2 , 0
               0   24.73     5.6           24.33
Permanent Ineff=
       F       F
Bank Sta=0,5.6
XS Rating Curve= 0
Exp/Cntr=.3,.1

Type RM Length L Ch R = 1 ,10.044  ,1,1,1
#Sta/Elev= 13
   -13.8   24.96    -3.8   24.96    -3.5   25.26    -2.2   25.26      -1   24.46
       0   24.46       0   23.36       2   23.36       2   24.36     3.2   24.86
     5.5   24.86     6.8   23.86    16.8   23.86
#Mann= 3 , 0 , 0
   -13.8    .035       0    -2.2    .035       0     3.2    .035       0
#XS Ineff= 2 , 0
       0    -2.2   25.26     3.2       0   24.86
Permanent Ineff=
       F       F
Bank Sta=-2.2,3.2
XS Rating Curve= 0
Exp/Cntr=.3,.1

Type RM Length L Ch R = 1 ,10.043  ,12,12,12
#Sta/Elev= 15
   -11.6   24.16    -1.6   24.16    -1.3   24.46       0   24.46     1.2   23.66
     2.2   23.66     2.2   22.56     2.2   22.26     4.2   22.26     4.2   22.56
     4.2   23.56     5.4   24.06     7.7   24.06       9   23.06      19   23.06
#Mann= 3 , 0 , 0
   -11.6    .035       0       0    .035       0     5.4    .035       0
#XS Ineff= 2 , 0
               0   24.46     5.4           24.06
Permanent Ineff=
       F       F
Bank Sta=0,5.4
XS Rating Curve= 0
Exp/Cntr=.3,.1

Type RM Length L Ch R = 1 ,10.031  ,31,31,31
#Sta/Elev= 6
     -10   23.83       0   23.83      .6   21.83     2.6   21.83     3.2   24.43
    13.2   24.43
#Mann= 3 , 0 , 0
     -10    .035       0       0    .035       0     3.2    .035       0
#XS Ineff= 2 , 0
               0   23.83     3.2           24.43
Permanent Ineff=
       F       F
Bank Sta=0,3.2
XS Rating Curve= 0
Exp/Cntr=.3,.1

Type RM Length L Ch R = 1 ,10      ,49,49,49
#Sta/Elev= 9
     -10    23.4       0    23.4     1.1    22.3     2.4    21.4     4.7    21.4
     7.9    23.2    10.2    23.2    11.2    22.4    21.2    22.4
#Mann= 3 , 0 , 0
     -10    .035       0       0    .035       0     7.9    .035       0
#XS Ineff= 2 , 0
               0    23.4     7.9            23.2
Permanent Ineff=
       F       F
Bank Sta=0,7.9
XS Rating Curve= 0
Exp/Cntr=.3,.1

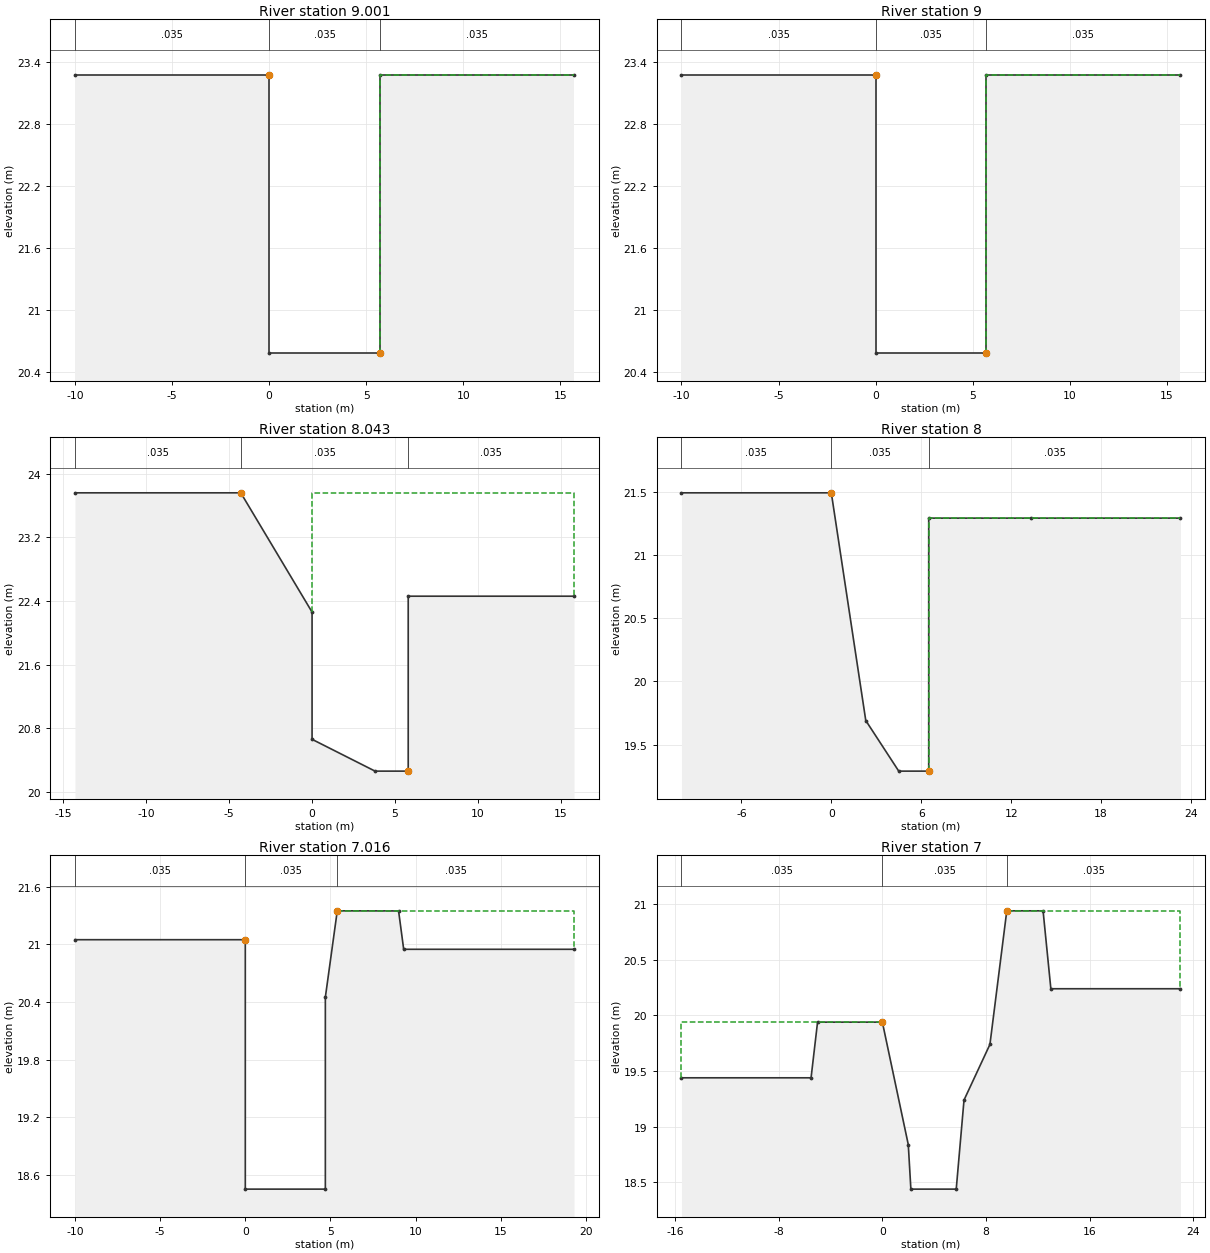
Type RM Length L Ch R = 1 ,9.001   ,1,1,1
#Sta/Elev= 6
     -10   23.28       0   23.28       0   20.58     5.7   20.58     5.7   23.28
    15.7   23.28
#Mann= 3 , 0 , 0
     -10    .035       0       0    .035       0     5.7    .035       0
#XS Ineff= 2 , 0
               0   23.28     5.7           23.28
Permanent Ineff=
       F       F
Bank Sta=0,5.7
XS Rating Curve= 0
Exp/Cntr=.3,.1

Type RM Length L Ch R = 1 ,9       ,7,7,7
#Sta/Elev= 6
     -10   23.28       0   23.28       0   20.58     5.7   20.58     5.7   23.28
    15.7   23.28
#Mann= 3 , 0 , 0
     -10    .035       0       0    .035       0     5.7    .035       0
#XS Ineff= 2 , 0
               0   23.28     5.7           23.28
Permanent Ineff=
       F       F
Bank Sta=0,5.7
XS Rating Curve= 0
Exp/Cntr=.3,.1

Type RM Length L Ch R = 1 ,8.043   ,43,43,43
#Sta/Elev= 8
   -14.3   23.76    -4.3   23.76       0   22.26       0   20.66     3.8   20.26
     5.8   20.26     5.8   22.46    15.8   22.46
#Mann= 3 , 0 , 0
   -14.3    .035       0    -4.3    .035       0     5.8    .035       0
#XS Ineff= 2 , 0
       0    -4.3   23.76     5.8       0   20.26
Permanent Ineff=
       F       F
Bank Sta=-4.3,5.8
XS Rating Curve= 0
Exp/Cntr=.3,.1

Type RM Length L Ch R = 1 ,8       ,34,34,34
#Sta/Elev= 8
     -10   21.49       0   21.49     2.3   19.69     4.5   19.29     6.5   19.29
     6.5   21.29    13.3   21.29    23.3   21.29
#Mann= 3 , 0 , 0
     -10    .035       0       0    .035       0     6.5    .035       0
#XS Ineff= 2 , 0
               0   21.49     6.5           21.29
Permanent Ineff=
       F       F
Bank Sta=0,6.5
XS Rating Curve= 0
Exp/Cntr=.3,.1

Type RM Length L Ch R = 1 ,7.016   ,16,16,16
#Sta/Elev= 9
     -10   21.05       0   21.05       0   18.45     4.7   18.45     4.7   20.45
     5.4  21.351       9   21.35     9.3   20.95    19.3   20.95
#Mann= 3 , 0 , 0
     -10    .035       0       0    .035       0     5.4    .035       0
#XS Ineff= 2 , 0
               0   21.05     5.4          21.351
Permanent Ineff=
       F       F
Bank Sta=0,5.4
XS Rating Curve= 0
Exp/Cntr=.3,.1

Type RM Length L Ch R = 1 ,7       ,18,18,18
#Sta/Elev= 13
   -15.5   19.44    -5.5   19.44      -5   19.94       0   19.94       2   18.84
     2.2   18.44     5.7   18.44     6.3   19.24     8.3   19.74     9.6   20.94
    12.4   20.94      13   20.24      23   20.24
#Mann= 3 , 0 , 0
   -15.5    .035       0       0    .035       0     9.6    .035       0
#XS Ineff= 2 , 0
               0   19.94     9.6           20.94
Permanent Ineff=
       F       F
Bank Sta=0,9.6
XS Rating Curve= 0
Exp/Cntr=.3,.1

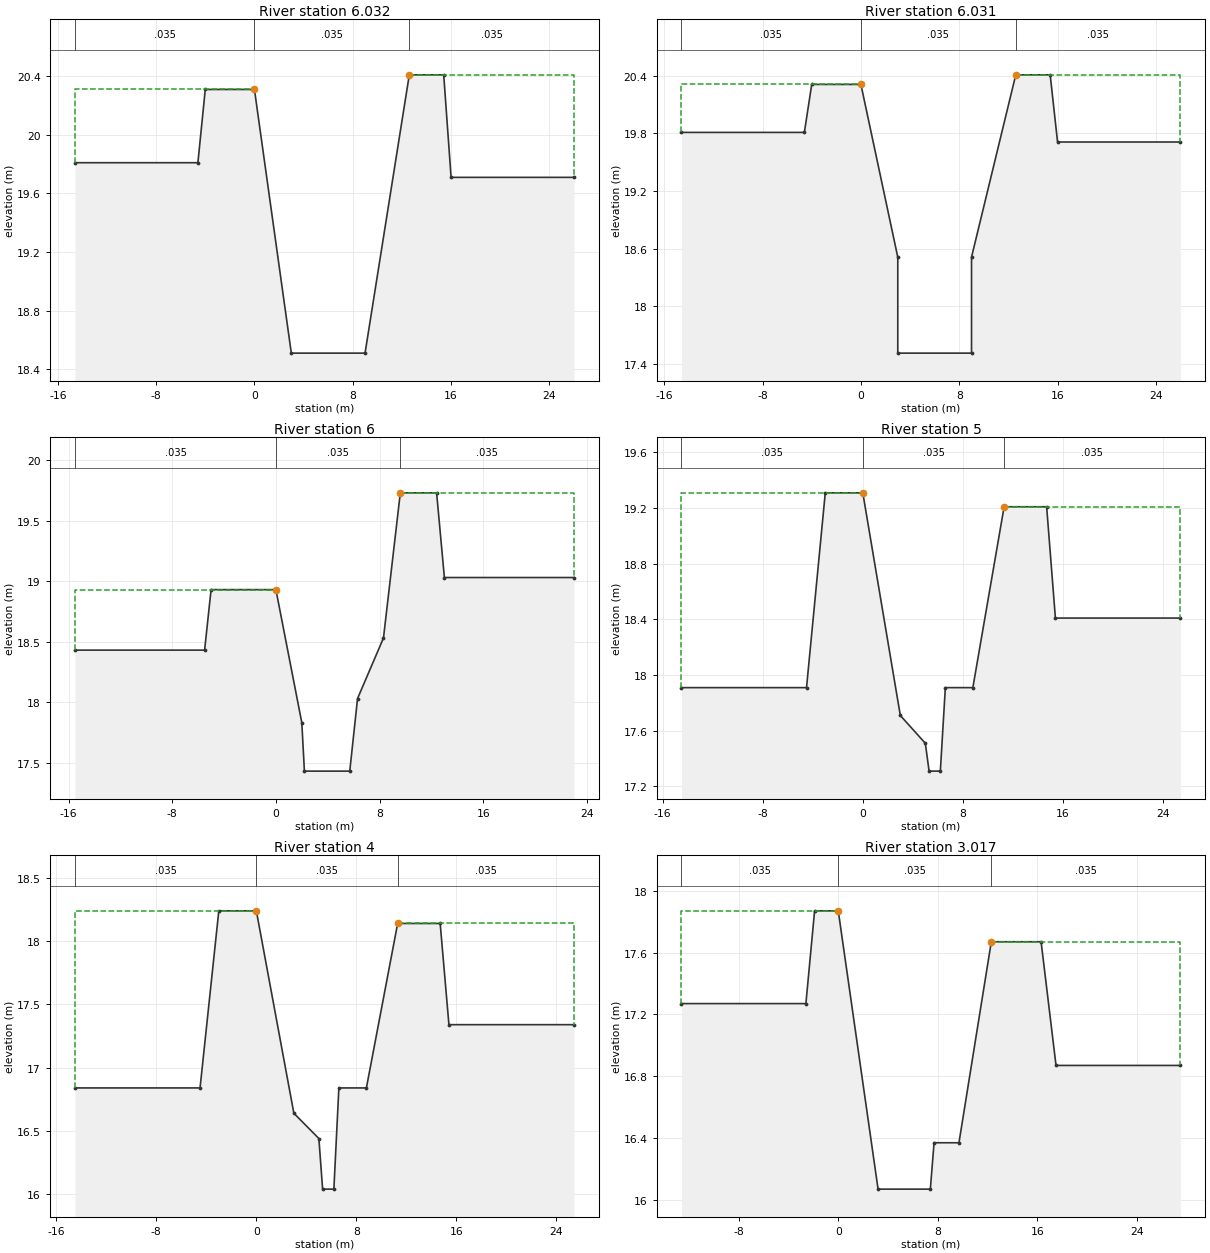
Type RM Length L Ch R = 1 ,6.032   ,1,1,1
#Sta/Elev= 11
   -14.6   19.81    -4.6   19.81      -4   20.31       0   20.31       3   18.51
       9   18.51    12.6   20.41    12.6   20.41    15.4   20.41      16   19.71
      26   19.71
#Mann= 3 , 0 , 0
   -14.6    .035       0       0    .035       0    12.6    .035       0
#XS Ineff= 2 , 0
               0   20.31    12.6           20.41
Permanent Ineff=
       F       F
Bank Sta=0,12.6
XS Rating Curve= 0
Exp/Cntr=.3,.1

Type RM Length L Ch R = 1 ,6.031   ,31,31,31
#Sta/Elev= 12
   -14.6   19.81    -4.6   19.81      -4   20.31       0   20.31       3   18.51
       3   17.51       9   17.51       9   18.51    12.6   20.41    15.4   20.41
      16   19.71      26   19.71
#Mann= 3 , 0 , 0
   -14.6    .035       0       0    .035       0    12.6    .035       0
#XS Ineff= 2 , 0
               0   20.31    12.6           20.41
Permanent Ineff=
       F       F
Bank Sta=0,12.6
XS Rating Curve= 0
Exp/Cntr=.3,.1

Type RM Length L Ch R = 1 ,6       ,50,50,50
#Sta/Elev= 13
   -15.5   18.43    -5.5   18.43      -5   18.93       0   18.93       2   17.83
     2.2   17.43     5.7   17.43     6.3   18.03     8.3   18.53     9.6   19.73
    12.4   19.73      13   19.03      23   19.03
#Mann= 3 , 0 , 0
   -15.5    .035       0       0    .035       0     9.6    .035       0
#XS Ineff= 2 , 0
               0   18.93     9.6           19.73
Permanent Ineff=
       F       F
Bank Sta=0,9.6
XS Rating Curve= 0
Exp/Cntr=.3,.1

Type RM Length L Ch R = 1 ,5       ,50,50,50
#Sta/Elev= 14
   -14.5   17.91    -4.5   17.91      -3   19.31       0   19.31       3   17.71
       5   17.51     5.3   17.31     6.2   17.31     6.6   17.91     8.8   17.91
    11.3   19.21    14.7   19.21    15.4   18.41    25.4   18.41
#Mann= 3 , 0 , 0
   -14.5    .035       0       0    .035       0    11.3    .035       0
#XS Ineff= 2 , 0
               0   19.31    11.3           19.21
Permanent Ineff=
       F       F
Bank Sta=0,11.3
XS Rating Curve= 0
Exp/Cntr=.3,.1

Type RM Length L Ch R = 1 ,4       ,33,33,33
#Sta/Elev= 14
   -14.5   16.84    -4.5   16.84      -3   18.24       0   18.24       3   16.64
       5   16.44     5.3   16.04     6.2   16.04     6.6   16.84     8.8   16.84
    11.3   18.14    14.7   18.14    15.4   17.34    25.4   17.34
#Mann= 3 , 0 , 0
   -14.5    .035       0       0    .035       0    11.3    .035       0
#XS Ineff= 2 , 0
               0   18.24    11.3           18.14
Permanent Ineff=
       F       F
Bank Sta=0,11.3
XS Rating Curve= 0
Exp/Cntr=.3,.1

Type RM Length L Ch R = 1 ,3.017   ,1,1,1
#Sta/Elev= 12
   -12.6   17.27    -2.6   17.27    -1.9   17.87       0   17.87     3.2   16.07
     7.4   16.07     7.7   16.37     9.7   16.37    12.3   17.67    16.3   17.67
    17.5   16.87    27.5   16.87
#Mann= 3 , 0 , 0
   -12.6    .035       0       0    .035       0    12.3    .035       0
#XS Ineff= 2 , 0
               0   17.87    12.3           17.67
Permanent Ineff=
       F       F
Bank Sta=0,12.3
XS Rating Curve= 0
Exp/Cntr=.3,.1

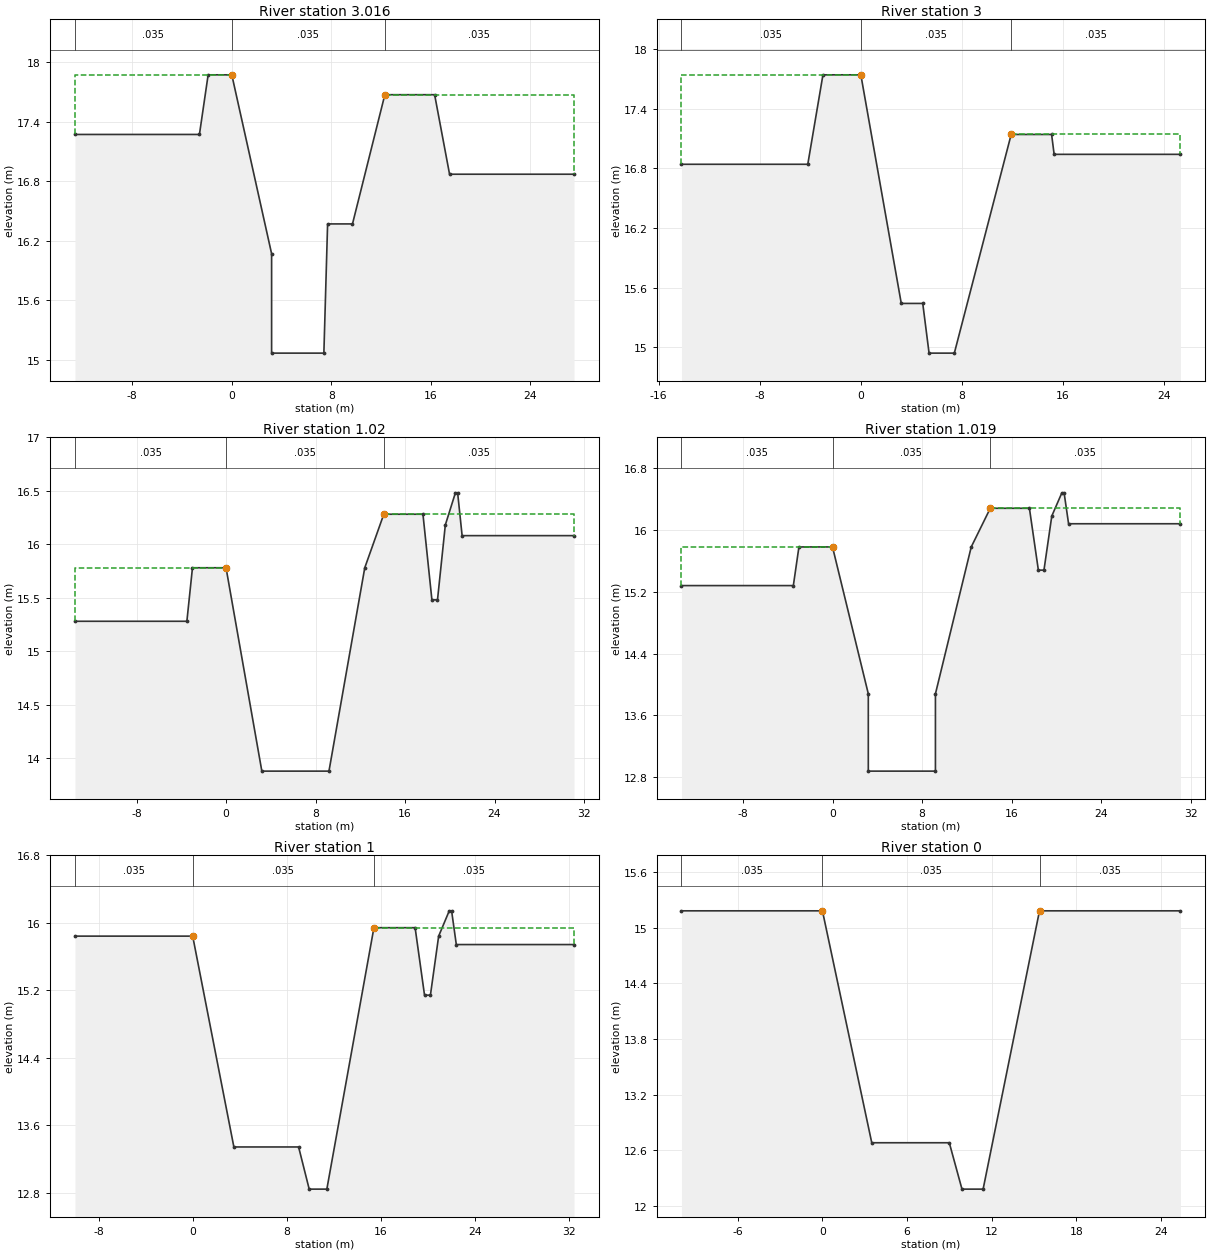
Type RM Length L Ch R = 1 ,3.016   ,16,16,16
#Sta/Elev= 13
   -12.6   17.27    -2.6   17.27    -1.9   17.87       0   17.87     3.2   16.07
     3.2   15.07     7.4   15.07     7.7   16.37     9.7   16.37    12.3   17.67
    16.3   17.67    17.5   16.87    27.5   16.87
#Mann= 3 , 0 , 0
   -12.6    .035       0       0    .035       0    12.3    .035       0
#XS Ineff= 2 , 0
               0   17.87    12.3           17.67
Permanent Ineff=
       F       F
Bank Sta=0,12.3
XS Rating Curve= 0
Exp/Cntr=.3,.1

Type RM Length L Ch R = 1 ,3       ,30,30,30
#Sta/Elev= 12
   -14.2   16.84    -4.2   16.84      -3   17.74       0   17.74     3.2   15.44
     4.9   15.44     5.4   14.94     7.4   14.94    11.9   17.14    15.1   17.14
    15.3   16.94    25.3   16.94
#Mann= 3 , 0 , 0
   -14.2    .035       0       0    .035       0    11.9    .035       0
#XS Ineff= 2 , 0
               0   17.74    11.9           17.14
Permanent Ineff=
       F       F
Bank Sta=0,11.9
XS Rating Curve= 0
Exp/Cntr=.3,.1

Type RM Length L Ch R = 1 ,1.02    ,1,1,1
#Sta/Elev= 16
   -13.5   15.28    -3.5   15.28      -3   15.78       0   15.78     3.2   13.88
     9.2   13.88    12.4   15.78    14.1   16.28    17.6   16.28    18.4   15.48
    18.9   15.48    19.6   16.18    20.5   16.48    20.7   16.48    21.1   16.08
    31.1   16.08
#Mann= 3 , 0 , 0
   -13.5    .035       0       0    .035       0    14.1    .035       0
#XS Ineff= 2 , 0
               0   15.78    14.1           16.28
Permanent Ineff=
       F       F
Bank Sta=0,14.1
XS Rating Curve= 0
Exp/Cntr=.3,.1

Type RM Length L Ch R = 1 ,1.019   ,19,19,19
#Sta/Elev= 18
   -13.5   15.28    -3.5   15.28      -3   15.78       0   15.78     3.2   13.88
     3.2   12.88     9.2   12.88     9.2   13.88    12.4   15.78    14.1   16.28
    17.6   16.28    18.4   15.48    18.9   15.48    19.6   16.18    20.5   16.48
    20.7   16.48    21.1   16.08    31.1   16.08
#Mann= 3 , 0 , 0
   -13.5    .035       0       0    .035       0    14.1    .035       0
#XS Ineff= 2 , 0
               0   15.78    14.1           16.28
Permanent Ineff=
       F       F
Bank Sta=0,14.1
XS Rating Curve= 0
Exp/Cntr=.3,.1

Type RM Length L Ch R = 1 ,1       ,50,50,50
#Sta/Elev= 15
     -10   15.84       0   15.84     3.5   13.34       9   13.34     9.9   12.84
    11.4   12.84    15.4   15.94    18.9   15.94    19.7   15.14    20.2   15.14
    20.9   15.84    21.8   16.14      22   16.14    22.4   15.74    32.4   15.74
#Mann= 3 , 0 , 0
     -10    .035       0       0    .035       0    15.4    .035       0
#XS Ineff= 2 , 0
               0   15.84    15.4           15.94
Permanent Ineff=
       F       F
Bank Sta=0,15.4
XS Rating Curve= 0
Exp/Cntr=.3,.1

Type RM Length L Ch R = 1 ,0       ,0,0,0
#Sta/Elev= 8
     -10   15.18       0   15.18     3.5   12.68       9   12.68     9.9   12.18
    11.4   12.18    15.4   15.18    25.4   15.18
#Mann= 3 , 0 , 0
     -10    .035       0       0    .035       0    15.4    .035       0
#XS Ineff= 2 , 0
               0   15.18    15.4           15.18
Permanent Ineff=
       F       F
Bank Sta=0,15.4
XS Rating Curve= 0
Exp/Cntr=.3,.1

Chan Stop Cuts=-1