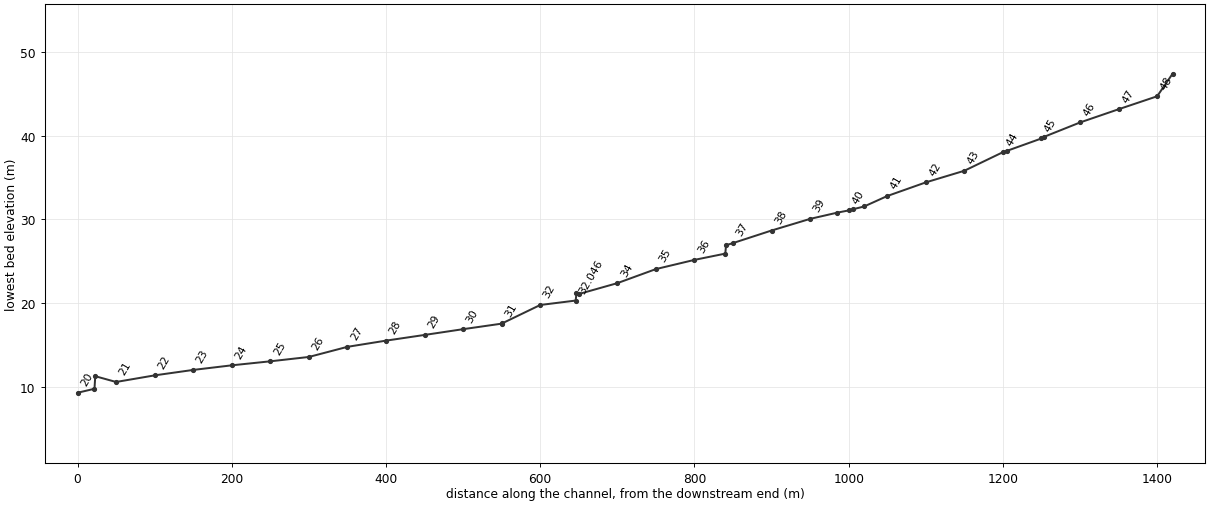
--- wonman-ch.prj (project) ---

Proj Title=wonman-ch
Current Plan=p01
Default Exp/Contr=.3,.1
SI Units
Geom File=g01
Flow File=f01
Plan File=p01
Y Axis Title=Elevation
X Axis Title(PF)=Main Channel Distance
X Axis Title(XS)=Station
BEGIN DESCRIPTION:
           BACK WATER COMPUTATION
      APPLICATION OF HEC-2 BY Samju Construction Engineering
      wonman-ch: 10,20,30,50,80 yr
END DESCRIPTION:
DSS Export Rating Curves= 0
DSS Export Rating Curve Sorted= 0
DSS Export Volume Flow Curves= 0
DXF OffsetX= 0
DXF OffsetY= 0
DXF ScaleX= 1
DXF ScaleY= 10

--- wonman-ch.p01 (plan) ---

Plan Title=Imported Plan 01
Version=Version 3.0.1  Mar 2001
Short Identifier=Imported Pla
Geom File=g01
Flow File=f01
Subcritical Flow
K Sum by GR= 0
Std Step Tol= 0.003
Critical Tol= 0.003
Num of Std Step Trials= 20
Max Error Tol= 0.1
Flow Tol Ratio= 0.001
Split Flow NTrial= 30
Split Flow Tol= 0.02
Split Flow Ratio= 0.02
Log Output Level= 0
Friction Slope Method= 1
Unsteady Friction Slope Method= 2
Parabolic Critical Depth
Global Vel Dist= 0 , 0 , 0
Global Log Level= 0
CheckData=True
Encroach Param=-1 ,0,0, 0
Computation Interval=1HOUR
Output Interval=1HOUR
Run HTab= 0
Run UNet= 0
Run PostProcess= 0
UNET Theta= 1
UNET ZTol= 0.02
UNET ZSATol= 0.1
UNET MxIter= 20
UNET MaxInSteps= 20
UNET DtIC= 0
UNET DtMin= 0
UNET MaxCRTS= 20
UNET WFStab= 2
UNET SFStab= 1
UNET WFX= 1
UNET SFX= 1
UNET Convert EG Bridges=-1
UNET Use Existing IB Tables=-1
Instantaneous Interval=1HOUR
Write IC File= 0
Write Velocity= 0
Write Detailed= 0

--- wonman-ch.f01 (steady flow) ---

Flow Title=Imported Flow 01
Version=Version 3.0.1  Mar 2001
Number of Profiles= 5
Profile Names=PF 1,PF 2,PF 3,PF 4,PF 5
River Rch & RM=RIVER-1,Reach-1         ,48.02
     180     200     220     230     240
Boundary for River Rch & Prof#=RIVER-1,Reach-1         , 1
Up Type= 0
Dn Type= 3
Dn Slope=.0109
Boundary for River Rch & Prof#=RIVER-1,Reach-1         , 2
Up Type= 0
Dn Type= 3
Dn Slope=.0109
Boundary for River Rch & Prof#=RIVER-1,Reach-1         , 3
Up Type= 0
Dn Type= 3
Dn Slope=.0109
Boundary for River Rch & Prof#=RIVER-1,Reach-1         , 4
Up Type= 0
Dn Type= 3
Dn Slope=.0109
Boundary for River Rch & Prof#=RIVER-1,Reach-1         , 5
Up Type= 0
Dn Type= 3
Dn Slope=.0109
DSS Import GetInterval= 0
DSS Import GetPeak= 0
DSS Import FillOption= 0

--- wonman-ch.g01 (geometry) ---

Geom Title=Imported Geom 01
Version=Version 3.0.1  Mar 2001

River Reach=RIVER-1         ,Reach-1
Reach XY= 2
              .5             .95              .5             .05

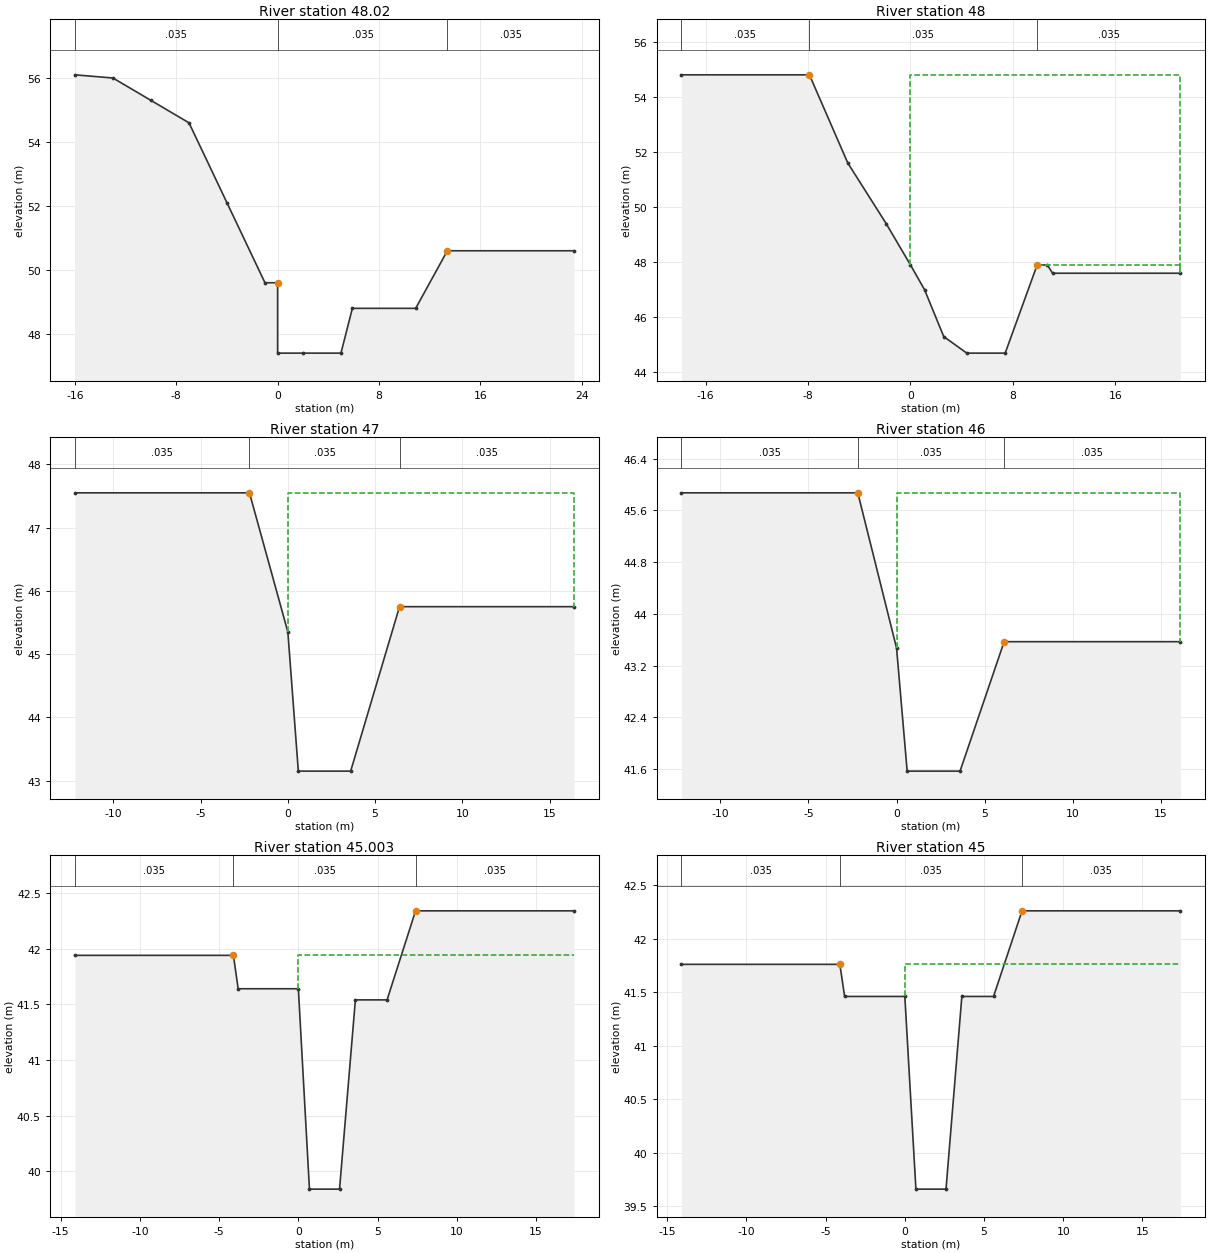
Type RM Length L Ch R = 1 ,48.02   ,20,20,20
#Sta/Elev= 14
     -16   56.09     -13   55.99     -10   55.29      -7   54.59      -4   52.09
      -1   49.59       0   49.59       0   47.39       2   47.39       5   47.39
     5.9   48.79    10.9   48.79    13.4   50.59    23.4   50.59
#Mann= 3 , 0 , 0
     -16    .035       0       0    .035       0    13.4    .035       0
#XS Ineff= 2 , 0
       0       0   49.59    13.4       0   50.59
Permanent Ineff=
       F       F
Bank Sta=0,13.4
XS Rating Curve= 0
Exp/Cntr=.3,.1

Type RM Length L Ch R = 1 ,48      ,50,50,50
#Sta/Elev= 13
   -17.9    54.8    -7.9    54.8    -4.9    51.6    -1.9    49.4       0    47.9
     1.1      47     2.6    45.3     4.4    44.7     7.4    44.7     9.9    47.9
    10.7    47.9    11.1    47.6    21.1    47.6
#Mann= 3 , 0 , 0
   -17.9    .035       0    -7.9    .035       0     9.9    .035       0
#XS Ineff= 2 , 0
       0    -7.9    54.8     9.9       0    47.9
Permanent Ineff=
       F       F
Bank Sta=-7.9,9.9
XS Rating Curve= 0
Exp/Cntr=.3,.1

Type RM Length L Ch R = 1 ,47      ,50,50,50
#Sta/Elev= 7
   -12.2   47.55    -2.2   47.55       0   45.35      .6   43.15     3.6   43.15
     6.4   45.75    16.4   45.75
#Mann= 3 , 0 , 0
   -12.2    .035       0    -2.2    .035       0     6.4    .035       0
#XS Ineff= 2 , 0
       0    -2.2   47.55     6.4       0   45.75
Permanent Ineff=
       F       F
Bank Sta=-2.2,6.4
XS Rating Curve= 0
Exp/Cntr=.3,.1

Type RM Length L Ch R = 1 ,46      ,47,47,47
#Sta/Elev= 7
   -12.2   45.87    -2.2   45.87       0   43.47      .6   41.57     3.6   41.57
     6.1   43.57    16.1   43.57
#Mann= 3 , 0 , 0
   -12.2    .035       0    -2.2    .035       0     6.1    .035       0
#XS Ineff= 2 , 0
       0    -2.2   45.87     6.1       0   43.57
Permanent Ineff=
       F       F
Bank Sta=-2.2,6.1
XS Rating Curve= 0
Exp/Cntr=.3,.1

Type RM Length L Ch R = 1 ,45.003  ,3,3,3
#Sta/Elev= 10
   -14.1   41.94    -4.1   41.94    -3.8   41.64       0   41.64      .7   39.84
     2.6   39.84     3.6   41.54     5.6   41.54     7.4   42.34    17.4   42.34
#Mann= 3 , 0 , 0
   -14.1    .035       0    -4.1    .035       0     7.4    .035       0
#XS Ineff= 2 , 0
       0    -4.1   41.94     7.4       0   42.34
Permanent Ineff=
       F       F
Bank Sta=-4.1,7.4
XS Rating Curve= 0
Exp/Cntr=.3,.1

Type RM Length L Ch R = 1 ,45      ,45,45,45
#Sta/Elev= 10
   -14.1   41.76    -4.1   41.76    -3.8   41.46       0   41.46      .7   39.66
     2.6   39.66     3.6   41.46     5.6   41.46     7.4   42.26    17.4   42.26
#Mann= 3 , 0 , 0
   -14.1    .035       0    -4.1    .035       0     7.4    .035       0
#XS Ineff= 2 , 0
       0    -4.1   41.76     7.4       0   42.26
Permanent Ineff=
       F       F
Bank Sta=-4.1,7.4
XS Rating Curve= 0
Exp/Cntr=.3,.1

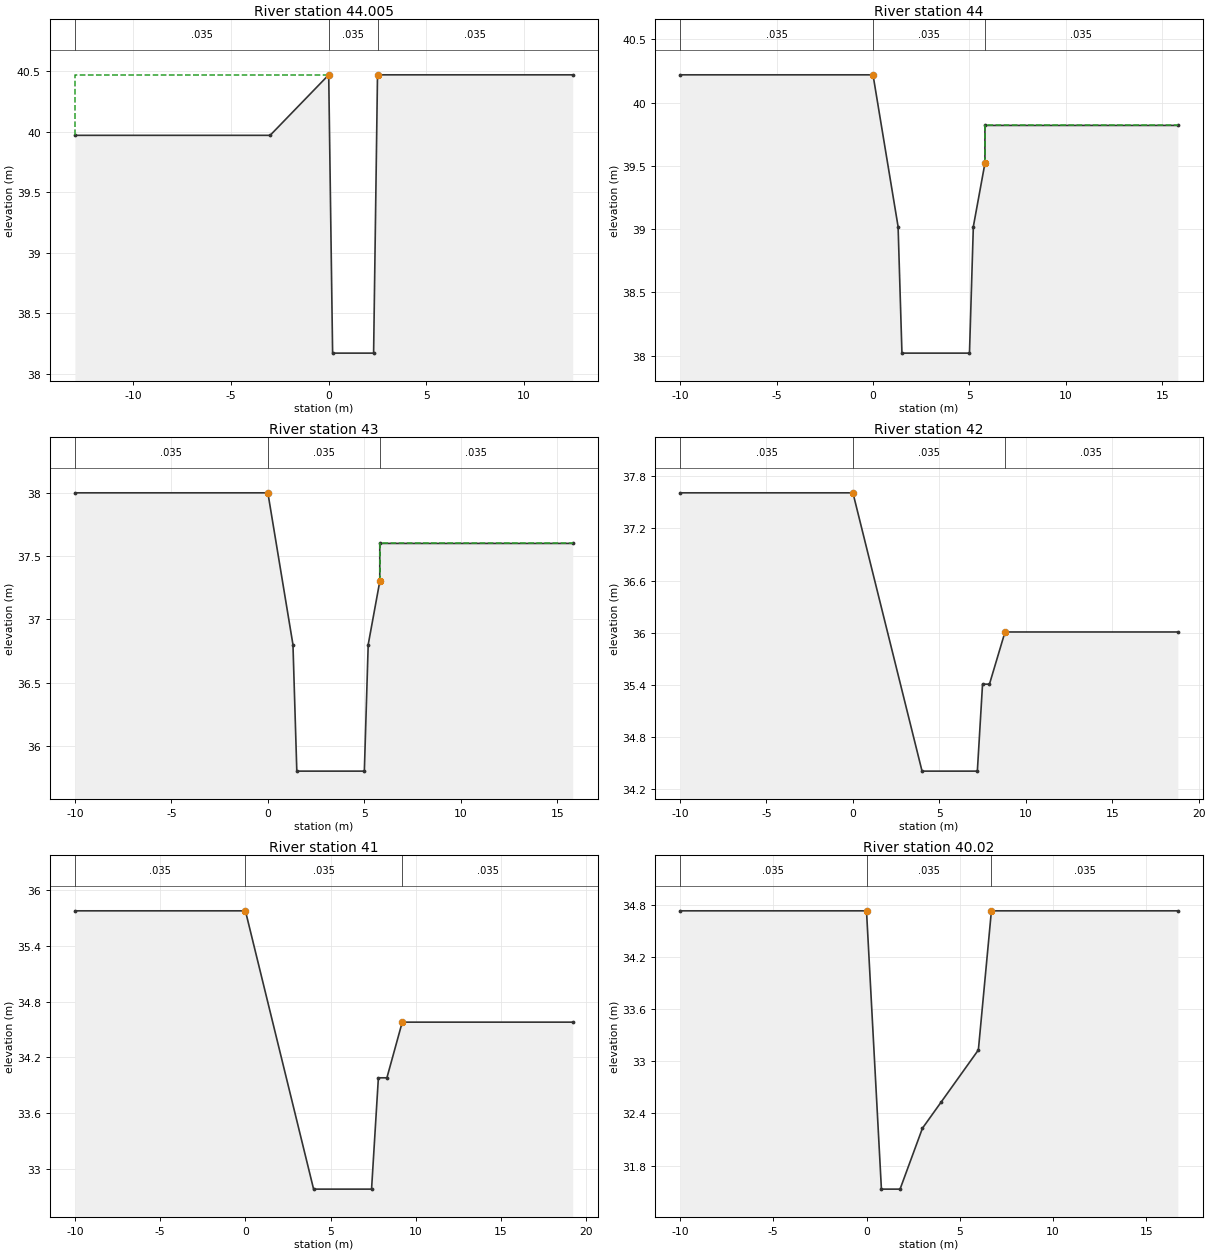
Type RM Length L Ch R = 1 ,44.005  ,5,5,5
#Sta/Elev= 7
     -13   39.97      -3   39.97       0   40.47      .2   38.17     2.3   38.17
     2.5   40.47    12.5   40.47
#Mann= 3 , 0 , 0
     -13    .035       0       0    .035       0     2.5    .035       0
#XS Ineff= 2 , 0
               0   40.47     2.5           40.47
Permanent Ineff=
       F       F
Bank Sta=0,2.5
XS Rating Curve= 0
Exp/Cntr=.3,.1

Type RM Length L Ch R = 1 ,44      ,50,50,50
#Sta/Elev= 9
     -10   40.22       0   40.22     1.3   39.02     1.5   38.02       5   38.02
     5.2   39.02     5.8   39.52     5.8   39.82    15.8   39.82
#Mann= 3 , 0 , 0
     -10    .035       0       0    .035       0     5.8    .035       0
#XS Ineff= 2 , 0
               0   40.22     5.8           39.82
Permanent Ineff=
       F       F
Bank Sta=0,5.8
XS Rating Curve= 0
Exp/Cntr=.3,.1

Type RM Length L Ch R = 1 ,43      ,50,50,50
#Sta/Elev= 9
     -10      38       0      38     1.3    36.8     1.5    35.8       5    35.8
     5.2    36.8     5.8    37.3     5.8    37.6    15.8    37.6
#Mann= 3 , 0 , 0
     -10    .035       0       0    .035       0     5.8    .035       0
#XS Ineff= 2 , 0
               0      38     5.8            37.6
Permanent Ineff=
       F       F
Bank Sta=0,5.8
XS Rating Curve= 0
Exp/Cntr=.3,.1

Type RM Length L Ch R = 1 ,42      ,50,50,50
#Sta/Elev= 8
     -10   37.61       0   37.61       4   34.41     7.2   34.41     7.5   35.41
     7.9   35.41     8.8   36.01    18.8   36.01
#Mann= 3 , 0 , 0
     -10    .035       0       0    .035       0     8.8    .035       0
#XS Ineff= 2 , 0
               0   37.61     8.8           36.01
Permanent Ineff=
       F       F
Bank Sta=0,8.8
XS Rating Curve= 0
Exp/Cntr=.3,.1

Type RM Length L Ch R = 1 ,41      ,30,30,30
#Sta/Elev= 8
     -10   35.78       0   35.78       4   32.78     7.4   32.78     7.8   33.98
     8.3   33.98     9.2   34.58    19.2   34.58
#Mann= 3 , 0 , 0
     -10    .035       0       0    .035       0     9.2    .035       0
#XS Ineff= 2 , 0
               0   35.78     9.2           34.58
Permanent Ineff=
       F       F
Bank Sta=0,9.2
XS Rating Curve= 0
Exp/Cntr=.3,.1

Type RM Length L Ch R = 1 ,40.02   ,14,14,14
#Sta/Elev= 9
     -10   34.73       0   34.73      .8   31.53     1.8   31.53       3   32.23
       4   32.53       6   33.13     6.7   34.73    16.7   34.73
#Mann= 3 , 0 , 0
     -10    .035       0       0    .035       0     6.7    .035       0
#XS Ineff= 2 , 0
               0   34.73     6.7           34.73
Permanent Ineff=
       F       F
Bank Sta=0,6.7
XS Rating Curve= 0
Exp/Cntr=.3,.1

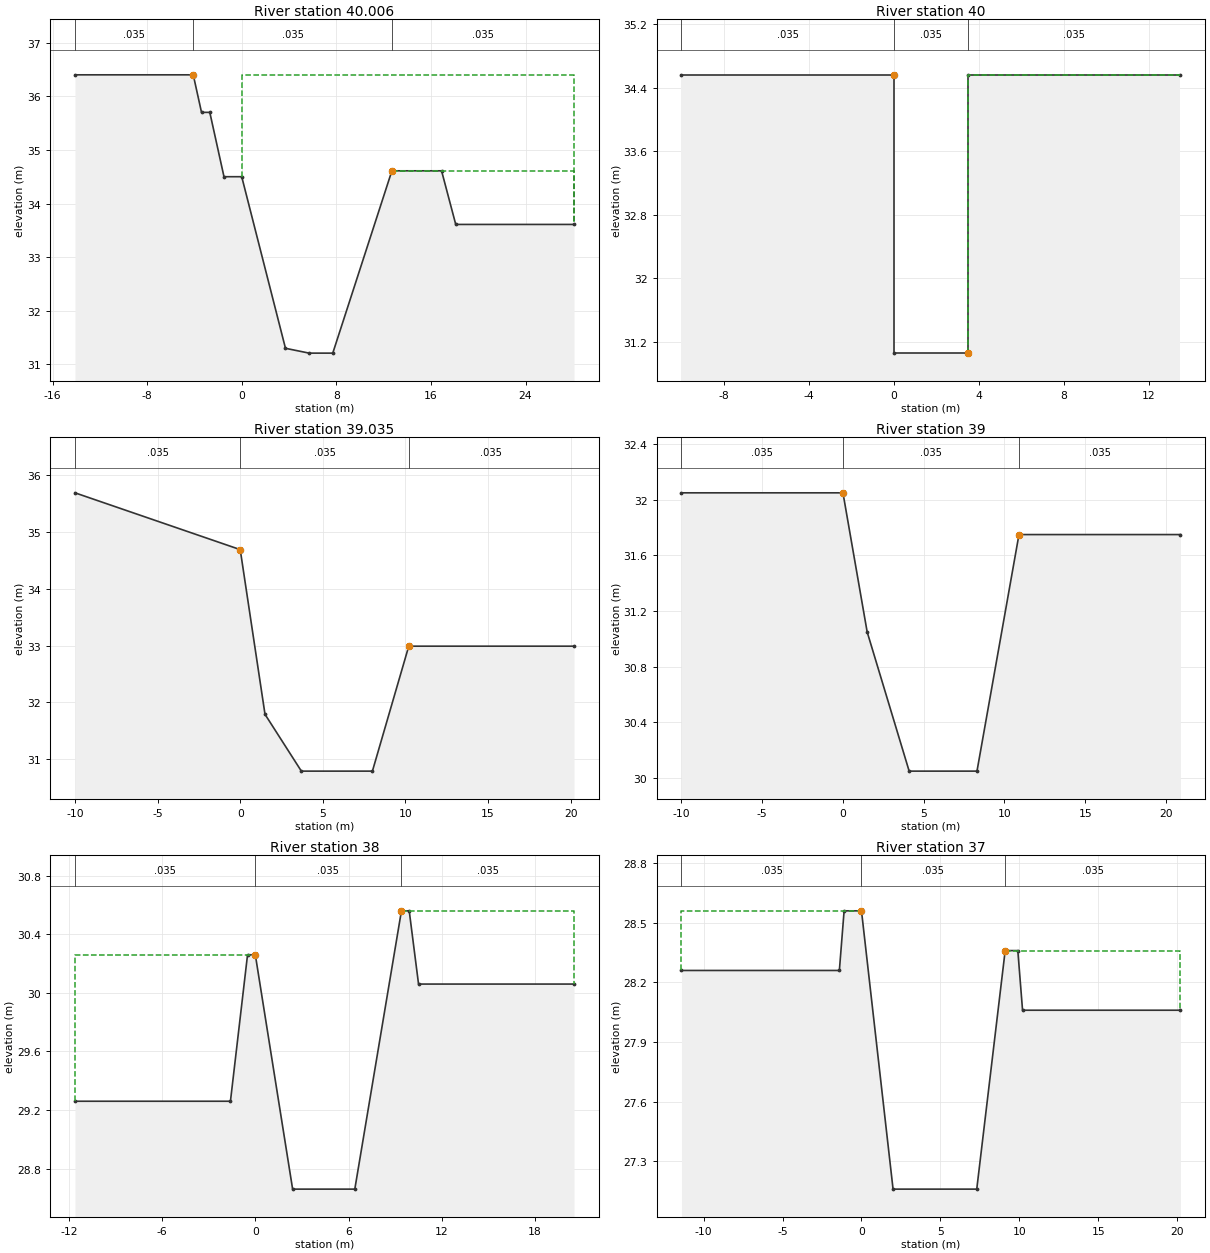
Type RM Length L Ch R = 1 ,40.006  ,6,6,6
#Sta/Elev= 13
   -14.1    36.4    -4.1    36.4    -3.4    35.7    -2.7    35.7    -1.5    34.5
       0    34.5     3.7    31.3     5.7   31.21     7.7   31.21    12.7   34.61
    16.9   34.61    18.1   33.61    28.1   33.61
#Mann= 3 , 0 , 0
   -14.1    .035       0    -4.1    .035       0    12.7    .035       0
#XS Ineff= 2 , 0
       0    -4.1    36.4    12.7       0   34.61
Permanent Ineff=
       F       F
Bank Sta=-4.1,12.7
XS Rating Curve= 0
Exp/Cntr=.3,.1

Type RM Length L Ch R = 1 ,40      ,15,15,15
#Sta/Elev= 6
     -10   34.56       0   34.56       0   31.06     3.5   31.06     3.5   34.56
    13.5   34.56
#Mann= 3 , 0 , 0
     -10    .035       0       0    .035       0     3.5    .035       0
#XS Ineff= 2 , 0
               0   34.56     3.5           34.56
Permanent Ineff=
       F       F
Bank Sta=0,3.5
XS Rating Curve= 0
Exp/Cntr=.3,.1

Type RM Length L Ch R = 1 ,39.035  ,35,35,35
#Sta/Elev= 7
     -10   35.69       0   34.69     1.5   31.79     3.7   30.79       8   30.79
    10.2   32.99    20.2   32.99
#Mann= 3 , 0 , 0
     -10    .035       0       0    .035       0    10.2    .035       0
#XS Ineff= 2 , 0
               0   34.69    10.2           32.99
Permanent Ineff=
       F       F
Bank Sta=0,10.2
XS Rating Curve= 0
Exp/Cntr=.3,.1

Type RM Length L Ch R = 1 ,39      ,50,50,50
#Sta/Elev= 7
     -10   32.05       0   32.05     1.5   31.05     4.1   30.05     8.3   30.05
    10.9   31.75    20.9   31.75
#Mann= 3 , 0 , 0
     -10    .035       0       0    .035       0    10.9    .035       0
#XS Ineff= 2 , 0
               0   32.05    10.9           31.75
Permanent Ineff=
       F       F
Bank Sta=0,10.9
XS Rating Curve= 0
Exp/Cntr=.3,.1

Type RM Length L Ch R = 1 ,38      ,50,50,50
#Sta/Elev= 10
   -11.6   29.26    -1.6   29.26     -.5   30.26       0   30.26     2.4   28.66
     6.4   28.66     9.4   30.56     9.9   30.56    10.5   30.06    20.5   30.06
#Mann= 3 , 0 , 0
   -11.6    .035       0       0    .035       0     9.4    .035       0
#XS Ineff= 2 , 0
               0   30.26     9.4           30.56
Permanent Ineff=
       F       F
Bank Sta=0,9.4
XS Rating Curve= 0
Exp/Cntr=.3,.1

Type RM Length L Ch R = 1 ,37      ,9,9,9
#Sta/Elev= 10
   -11.4   28.26    -1.4   28.26    -1.1   28.56       0   28.56       2   27.16
     7.3   27.16     9.1   28.36     9.9   28.36    10.2   28.06    20.2   28.06
#Mann= 3 , 0 , 0
   -11.4    .035       0       0    .035       0     9.1    .035       0
#XS Ineff= 2 , 0
               0   28.56     9.1           28.36
Permanent Ineff=
       F       F
Bank Sta=0,9.1
XS Rating Curve= 0
Exp/Cntr=.3,.1

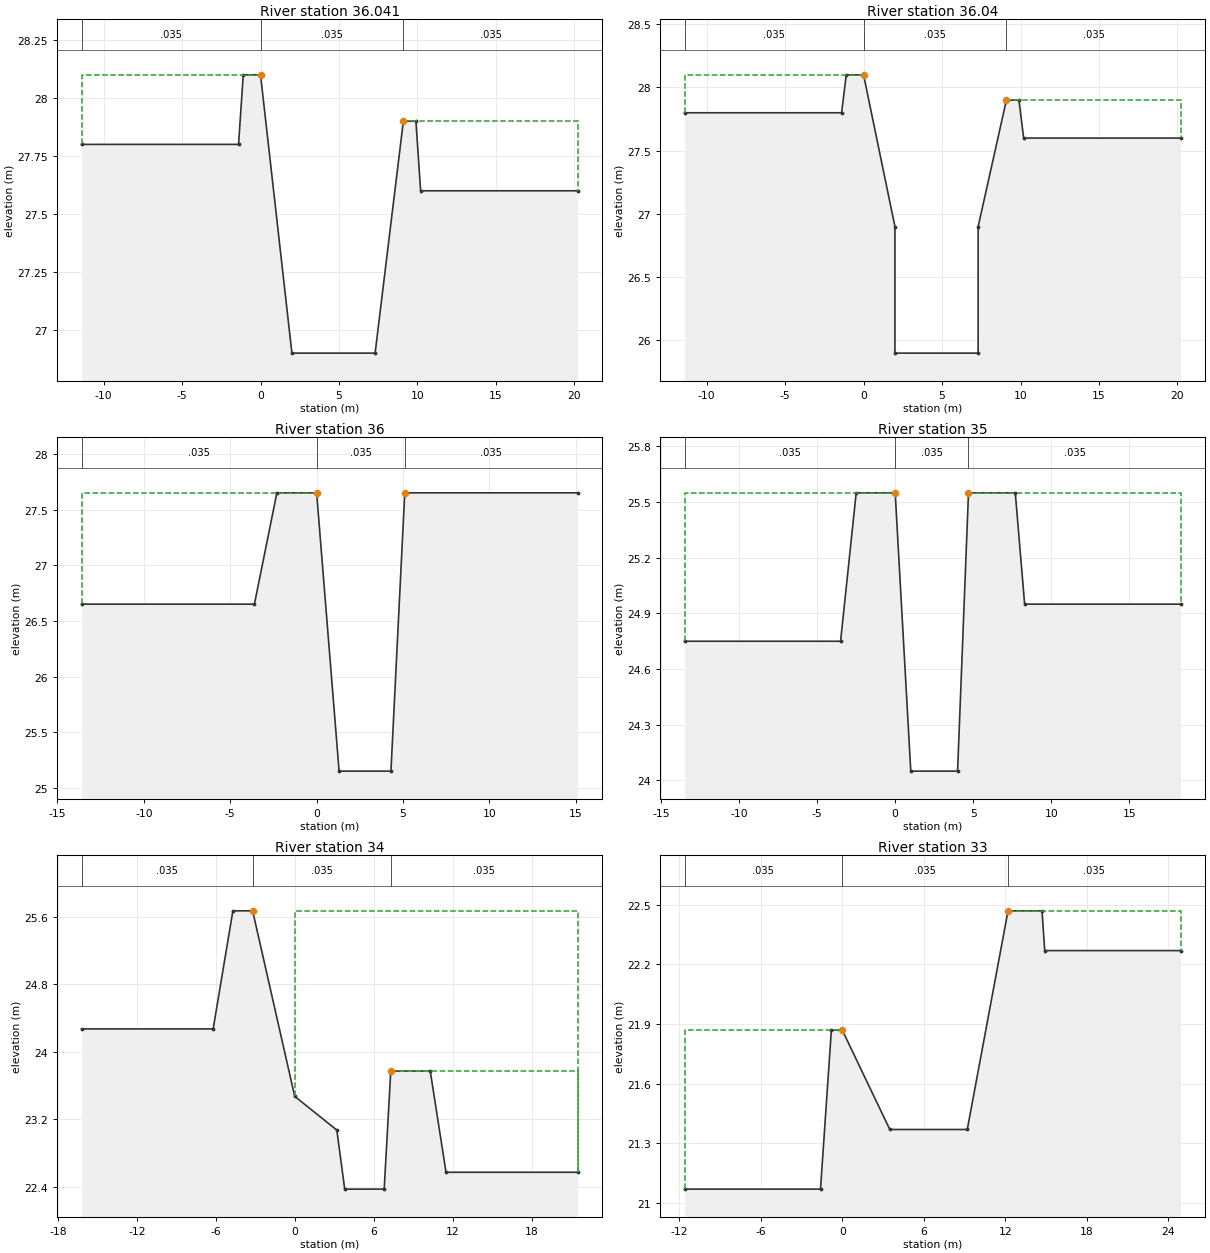
Type RM Length L Ch R = 1 ,36.041  ,1,1,1
#Sta/Elev= 10
   -11.4    27.8    -1.4    27.8    -1.1    28.1       0    28.1       2    26.9
     7.3    26.9     9.1    27.9     9.9    27.9    10.2    27.6    20.2    27.6
#Mann= 3 , 0 , 0
   -11.4    .035       0       0    .035       0     9.1    .035       0
#XS Ineff= 2 , 0
               0    28.1     9.1            27.9
Permanent Ineff=
       F       F
Bank Sta=0,9.1
XS Rating Curve= 0
Exp/Cntr=.3,.1

Type RM Length L Ch R = 1 ,36.04   ,40,40,40
#Sta/Elev= 12
   -11.4    27.8    -1.4    27.8    -1.1    28.1       0    28.1       2    26.9
       2    25.9     7.3    25.9     7.3    26.9     9.1    27.9     9.9    27.9
    10.2    27.6    20.2    27.6
#Mann= 3 , 0 , 0
   -11.4    .035       0       0    .035       0     9.1    .035       0
#XS Ineff= 2 , 0
               0    28.1     9.1            27.9
Permanent Ineff=
       F       F
Bank Sta=0,9.1
XS Rating Curve= 0
Exp/Cntr=.3,.1

Type RM Length L Ch R = 1 ,36      ,50,50,50
#Sta/Elev= 8
   -13.6   26.65    -3.6   26.65    -2.3   27.65       0   27.65     1.3   25.15
     4.3   25.15     5.1   27.65    15.1   27.65
#Mann= 3 , 0 , 0
   -13.6    .035       0       0    .035       0     5.1    .035       0
#XS Ineff= 2 , 0
               0   27.65     5.1           27.65
Permanent Ineff=
       F       F
Bank Sta=0,5.1
XS Rating Curve= 0
Exp/Cntr=.3,.1

Type RM Length L Ch R = 1 ,35      ,50,50,50
#Sta/Elev= 10
   -13.5   24.75    -3.5   24.75    -2.5   25.55       0   25.55       1   24.05
       4   24.05     4.7   25.55     7.7   25.55     8.3   24.95    18.3   24.95
#Mann= 3 , 0 , 0
   -13.5    .035       0       0    .035       0     4.7    .035       0
#XS Ineff= 2 , 0
               0   25.55     4.7           25.55
Permanent Ineff=
       F       F
Bank Sta=0,4.7
XS Rating Curve= 0
Exp/Cntr=.3,.1

Type RM Length L Ch R = 1 ,34      ,50,50,50
#Sta/Elev= 12
   -16.2   24.27    -6.2   24.27    -4.7   25.67    -3.2   25.67       0   23.47
     3.2   23.07     3.8   22.37     6.8   22.37     7.3   23.77    10.3   23.77
    11.5   22.57    21.5   22.57
#Mann= 3 , 0 , 0
   -16.2    .035       0    -3.2    .035       0     7.3    .035       0
#XS Ineff= 2 , 0
       0    -3.2   25.67     7.3       0   23.77
Permanent Ineff=
       F       F
Bank Sta=-3.2,7.3
XS Rating Curve= 0
Exp/Cntr=.3,.1

Type RM Length L Ch R = 1 ,33      ,3,3,3
#Sta/Elev= 10
   -11.6   21.07    -1.6   21.07     -.8   21.87       0   21.87     3.5   21.37
     9.2   21.37    12.2   22.47    14.7   22.47    14.9   22.27    24.9   22.27
#Mann= 3 , 0 , 0
   -11.6    .035       0       0    .035       0    12.2    .035       0
#XS Ineff= 2 , 0
               0   21.87    12.2           22.47
Permanent Ineff=
       F       F
Bank Sta=0,12.2
XS Rating Curve= 0
Exp/Cntr=.3,.1

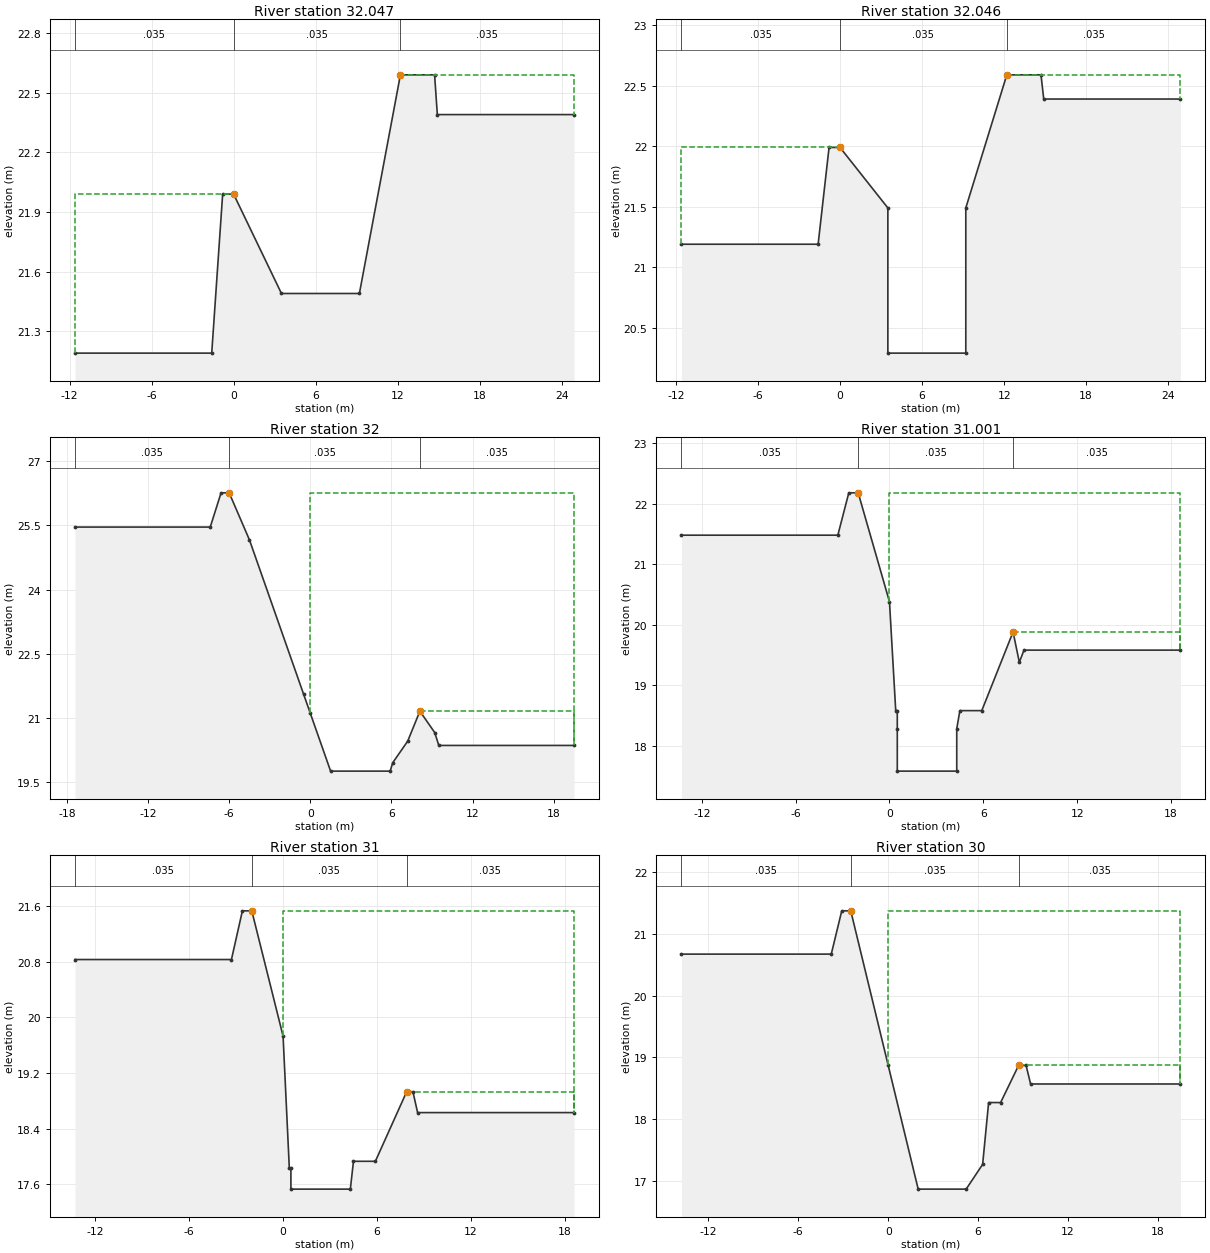
Type RM Length L Ch R = 1 ,32.047  ,1,1,1
#Sta/Elev= 10
   -11.6   21.19    -1.6   21.19     -.8   21.99       0   21.99     3.5   21.49
     9.2   21.49    12.2   22.59    14.7   22.59    14.9   22.39    24.9   22.39
#Mann= 3 , 0 , 0
   -11.6    .035       0       0    .035       0    12.2    .035       0
#XS Ineff= 2 , 0
               0   21.99    12.2           22.59
Permanent Ineff=
       F       F
Bank Sta=0,12.2
XS Rating Curve= 0
Exp/Cntr=.3,.1

Type RM Length L Ch R = 1 ,32.046  ,46,46,46
#Sta/Elev= 12
   -11.6   21.19    -1.6   21.19     -.8   21.99       0   21.99     3.5   21.49
     3.5   20.29     9.2   20.29     9.2   21.49    12.2   22.59    14.7   22.59
    14.9   22.39    24.9   22.39
#Mann= 3 , 0 , 0
   -11.6    .035       0       0    .035       0    12.2    .035       0
#XS Ineff= 2 , 0
               0   21.99    12.2           22.59
Permanent Ineff=
       F       F
Bank Sta=0,12.2
XS Rating Curve= 0
Exp/Cntr=.3,.1

Type RM Length L Ch R = 1 ,32      ,49,49,49
#Sta/Elev= 15
   -17.4   25.46    -7.4   25.46    -6.6   26.26      -6   26.26    -4.5   25.16
     -.5   21.56       0   21.11     1.5   19.76     5.9   19.76     6.1   19.96
     7.2   20.46     8.1   21.16     9.2   20.66     9.5   20.36    19.5   20.36
#Mann= 3 , 0 , 0
   -17.4    .035       0      -6    .035       0     8.1    .035       0
#XS Ineff= 2 , 0
       0      -6   26.26     8.1       0   21.16
Permanent Ineff=
       F       F
Bank Sta=-6,8.1
XS Rating Curve= 0
Exp/Cntr=.3,.1

Type RM Length L Ch R = 1 ,31.001  ,1,1,1
#Sta/Elev= 17
   -13.3   21.48    -3.3   21.48    -2.6   22.18      -2   22.18       0   20.38
      .4   18.58      .5   18.58      .5   18.28      .5   17.58     4.3   17.58
     4.3   18.28     4.5   18.58     5.9   18.58     7.9   19.88     8.3   19.38
     8.6   19.58    18.6   19.58
#Mann= 3 , 0 , 0
   -13.3    .035       0      -2    .035       0     7.9    .035       0
#XS Ineff= 2 , 0
       0      -2   22.18     7.9       0   19.88
Permanent Ineff=
       F       F
Bank Sta=-2,7.9
XS Rating Curve= 0
Exp/Cntr=.3,.1

Type RM Length L Ch R = 1 ,31      ,50,50,50
#Sta/Elev= 15
   -13.3   20.83    -3.3   20.83    -2.6   21.53      -2   21.53       0   19.73
      .4   17.83      .5   17.83      .5   17.53     4.3   17.53     4.5   17.93
     5.9   17.93     7.9   18.93     8.3   18.93     8.6   18.63    18.6   18.63
#Mann= 3 , 0 , 0
   -13.3    .035       0      -2    .035       0     7.9    .035       0
#XS Ineff= 2 , 0
       0      -2   21.53     7.9       0   18.93
Permanent Ineff=
       F       F
Bank Sta=-2,7.9
XS Rating Curve= 0
Exp/Cntr=.3,.1

Type RM Length L Ch R = 1 ,30      ,50,50,50
#Sta/Elev= 14
   -13.8   20.67    -3.8   20.67    -3.1   21.37    -2.5   21.37       0   18.87
       2   16.87     5.2   16.87     6.3   17.27     6.7   18.27     7.5   18.27
     8.7   18.87     9.2   18.87     9.5   18.57    19.5   18.57
#Mann= 3 , 0 , 0
   -13.8    .035       0    -2.5    .035       0     8.7    .035       0
#XS Ineff= 2 , 0
       0    -2.5   21.37     8.7       0   18.87
Permanent Ineff=
       F       F
Bank Sta=-2.5,8.7
XS Rating Curve= 0
Exp/Cntr=.3,.1

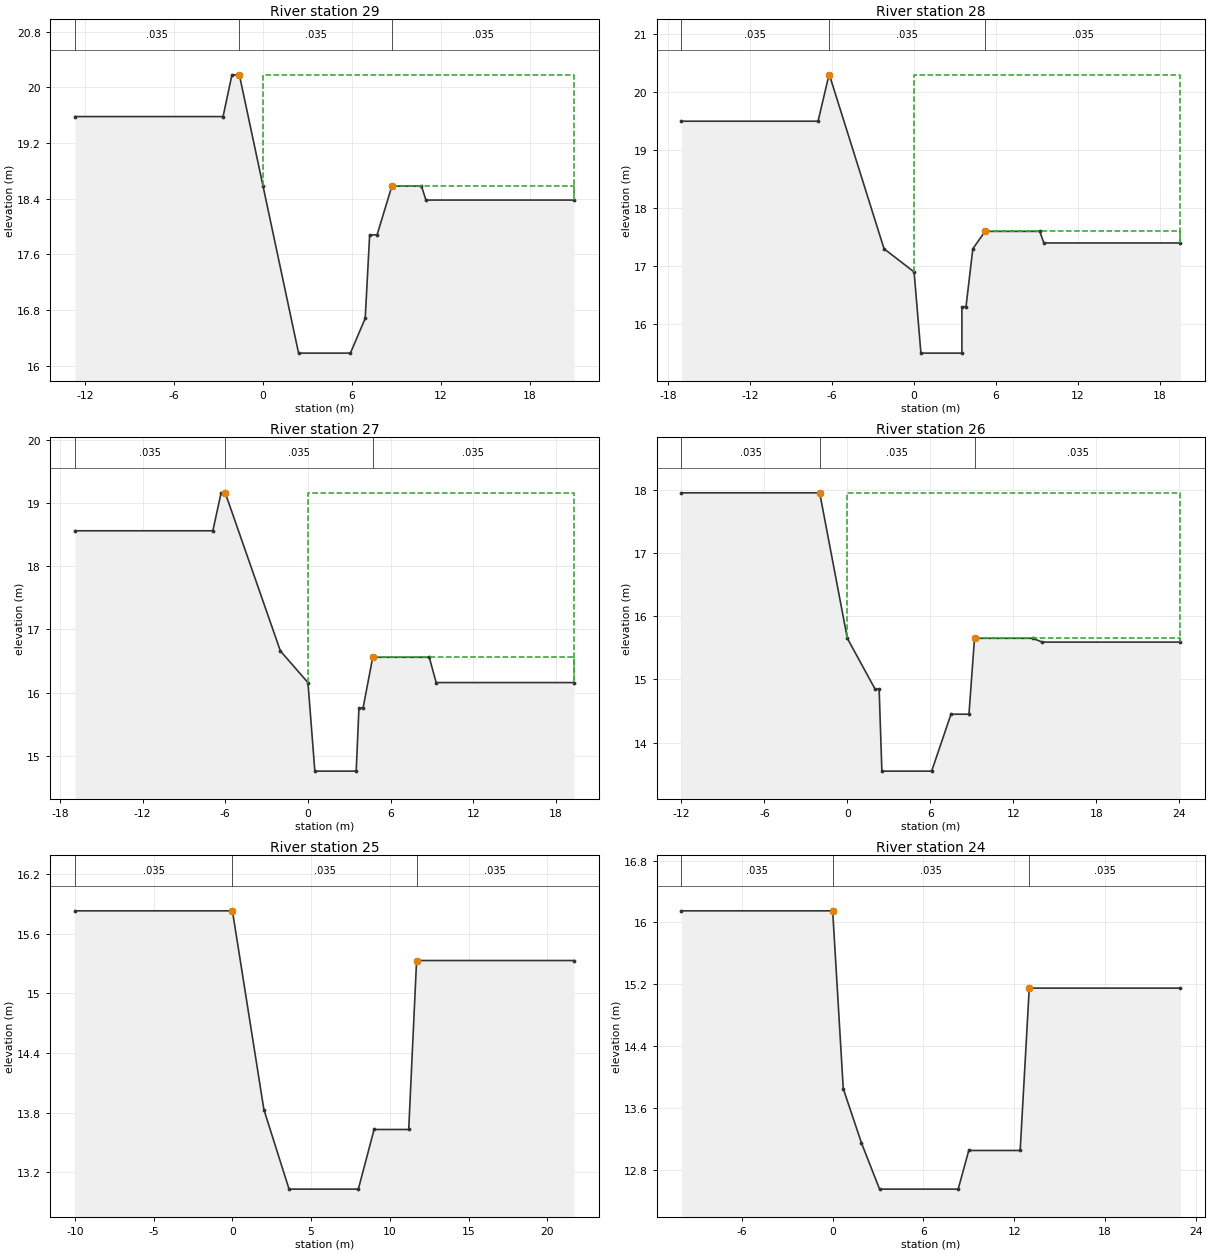
Type RM Length L Ch R = 1 ,29      ,50,50,50
#Sta/Elev= 14
   -12.7   19.58    -2.7   19.58    -2.1   20.18    -1.6   20.18       0   18.58
     2.4   16.18     5.9   16.18     6.9   16.68     7.2   17.88     7.7   17.88
     8.7   18.58    10.7   18.58      11   18.38      21   18.38
#Mann= 3 , 0 , 0
   -12.7    .035       0    -1.6    .035       0     8.7    .035       0
#XS Ineff= 2 , 0
       0    -1.6   20.18     8.7       0   18.58
Permanent Ineff=
       F       F
Bank Sta=-1.6,8.7
XS Rating Curve= 0
Exp/Cntr=.3,.1

Type RM Length L Ch R = 1 ,28      ,50,50,50
#Sta/Elev= 15
  -17.03    19.5   -7.03    19.5   -6.23    20.3    -6.2    20.3    -2.2    17.3
       0    16.9      .5    15.5     3.5    15.5     3.5    16.3     3.8    16.3
     4.3    17.3     5.2    17.6     9.2    17.6     9.5    17.4    19.5    17.4
#Mann= 3 , 0 , 0
  -17.03    .035       0    -6.2    .035       0     5.2    .035       0
#XS Ineff= 2 , 0
       0    -6.2    20.3     5.2       0    17.6
Permanent Ineff=
       F       F
Bank Sta=-6.2,5.2
XS Rating Curve= 0
Exp/Cntr=.3,.1

Type RM Length L Ch R = 1 ,27      ,50,50,50
#Sta/Elev= 14
   -16.9   18.56    -6.9   18.56    -6.3   19.16      -6   19.16      -2   16.66
       0   16.16      .5   14.76     3.5   14.76     3.7   15.76       4   15.76
     4.7   16.56     8.8   16.56     9.3   16.16    19.3   16.16
#Mann= 3 , 0 , 0
   -16.9    .035       0      -6    .035       0     4.7    .035       0
#XS Ineff= 2 , 0
       0      -6   19.16     4.7       0   16.56
Permanent Ineff=
       F       F
Bank Sta=-6,4.7
XS Rating Curve= 0
Exp/Cntr=.3,.1

Type RM Length L Ch R = 1 ,26      ,50,50,50
#Sta/Elev= 13
     -12   17.95      -2   17.95       0   15.65       2   14.85     2.3   14.85
     2.5   13.55     6.1   13.55     7.5   14.45     8.8   14.45     9.2   15.65
    13.4   15.65    14.1   15.59    24.1   15.59
#Mann= 3 , 0 , 0
     -12    .035       0      -2    .035       0     9.2    .035       0
#XS Ineff= 2 , 0
       0      -2   17.95     9.2       0   15.65
Permanent Ineff=
       F       F
Bank Sta=-2,9.2
XS Rating Curve= 0
Exp/Cntr=.3,.1

Type RM Length L Ch R = 1 ,25      ,50,50,50
#Sta/Elev= 9
     -10   15.83       0   15.83       2   13.83     3.6   13.03       8   13.03
       9   13.63    11.2   13.63    11.7   15.33    21.7   15.33
#Mann= 3 , 0 , 0
     -10    .035       0       0    .035       0    11.7    .035       0
#XS Ineff= 2 , 0
               0   15.83    11.7           15.33
Permanent Ineff=
       F       F
Bank Sta=0,11.7
XS Rating Curve= 0
Exp/Cntr=.3,.1

Type RM Length L Ch R = 1 ,24      ,50,50,50
#Sta/Elev= 10
     -10   16.15       0   16.15      .7   13.85     1.9   13.15     3.1   12.55
     8.3   12.55       9   13.05    12.4   13.05      13   15.15      23   15.15
#Mann= 3 , 0 , 0
     -10    .035       0       0    .035       0      13    .035       0
#XS Ineff= 2 , 0
               0   16.15      13           15.15
Permanent Ineff=
       F       F
Bank Sta=0,13
XS Rating Curve= 0
Exp/Cntr=.3,.1

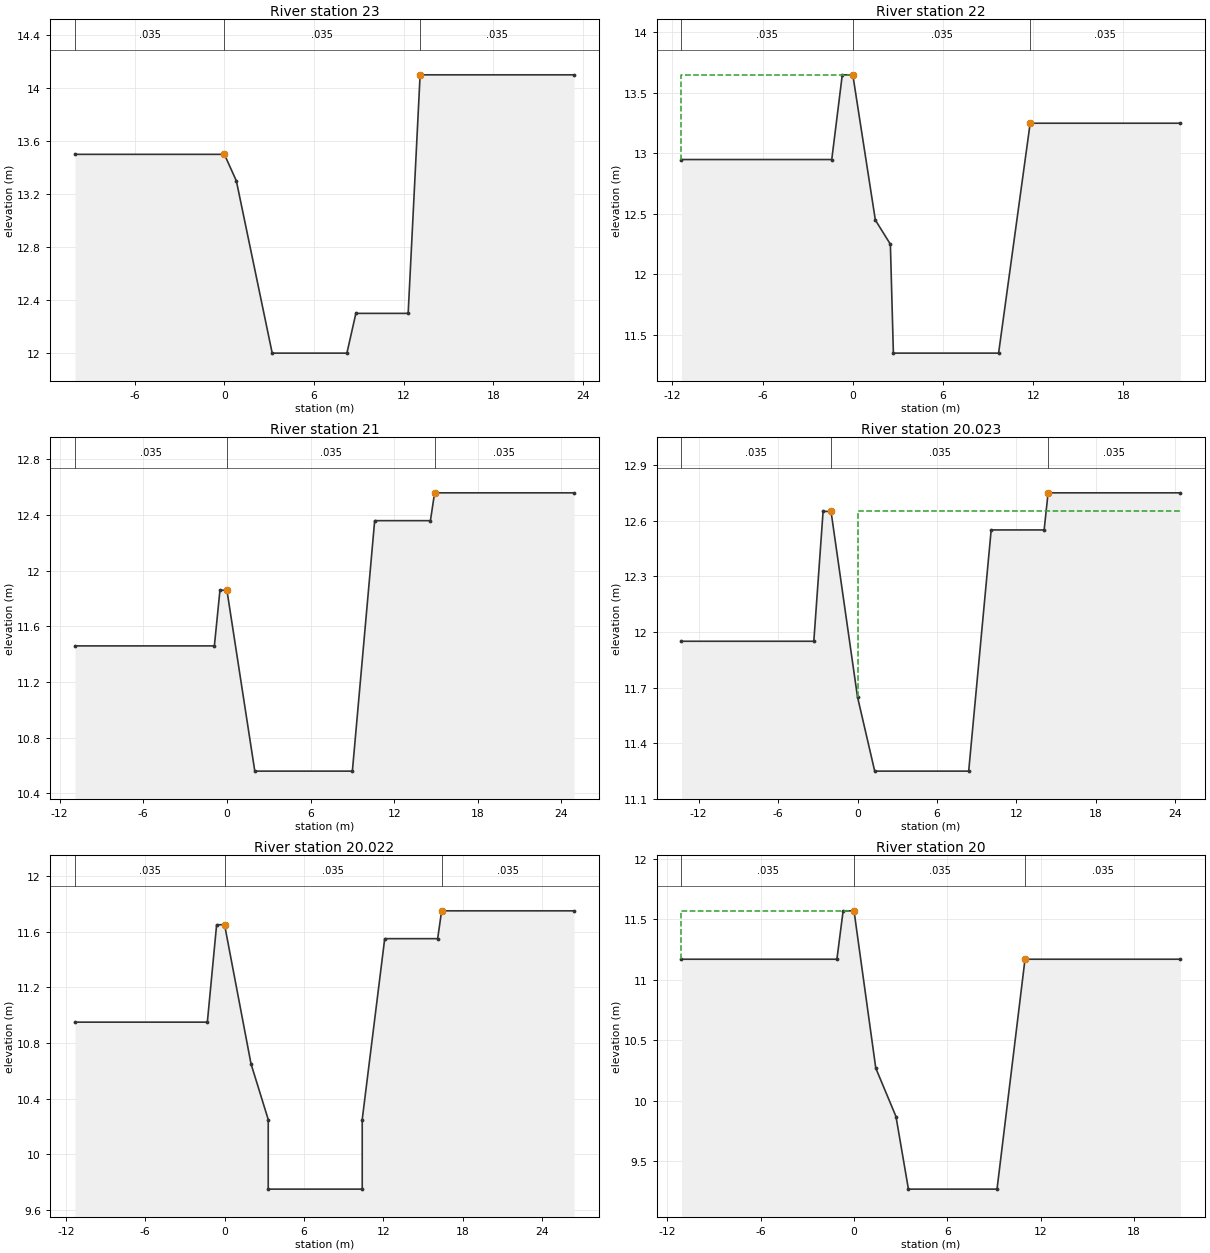
Type RM Length L Ch R = 1 ,23      ,50,50,50
#Sta/Elev= 9
     -10    13.5       0    13.5      .8    13.3     3.2      12     8.2      12
     8.8    12.3    12.3    12.3    13.1    14.1    23.4    14.1
#Mann= 3 , 0 , 0
     -10    .035       0       0    .035       0    13.1    .035       0
#XS Ineff= 2 , 0
               0    13.5    13.1            14.1
Permanent Ineff=
       F       F
Bank Sta=0,13.1
XS Rating Curve= 0
Exp/Cntr=.3,.1

Type RM Length L Ch R = 1 ,22      ,50,50,50
#Sta/Elev= 10
   -11.4   12.95    -1.4   12.95     -.7   13.65       0   13.65     1.5   12.45
     2.5   12.25     2.7   11.35     9.7   11.35    11.8   13.25    21.8   13.25
#Mann= 3 , 0 , 0
   -11.4    .035       0       0    .035       0    11.8    .035       0
#XS Ineff= 2 , 0
               0   13.65    11.8           13.25
Permanent Ineff=
       F       F
Bank Sta=0,11.8
XS Rating Curve= 0
Exp/Cntr=.3,.1

Type RM Length L Ch R = 1 ,21      ,27,27,27
#Sta/Elev= 10
   -10.9   11.46     -.9   11.46     -.5   11.86       0   11.86       2   10.56
       9   10.56    10.6   12.36    14.6   12.36    14.9   12.56    24.9   12.56
#Mann= 3 , 0 , 0
   -10.9    .035       0       0    .035       0    14.9    .035       0
#XS Ineff= 2 , 0
       0       0   11.86    14.9       0   12.56
Permanent Ineff=
       F       F
Bank Sta=0,14.9
XS Rating Curve= 0
Exp/Cntr=.3,.1

Type RM Length L Ch R = 1 ,20.023  ,1,1,1
#Sta/Elev= 11
   -13.3   11.95    -3.3   11.95    -2.6   12.65      -2   12.65       0   11.65
     1.3   11.25     8.4   11.25    10.1   12.55    14.1   12.55    14.4   12.75
    24.4   12.75
#Mann= 3 , 0 , 0
   -13.3    .035       0      -2    .035       0    14.4    .035       0
#XS Ineff= 2 , 0
       0      -2   12.65    14.4       0   12.75
Permanent Ineff=
       F       F
Bank Sta=-2,14.4
XS Rating Curve= 0
Exp/Cntr=.3,.1

Type RM Length L Ch R = 1 ,20.022  ,22,22,22
#Sta/Elev= 13
   -11.3   10.95    -1.3   10.95     -.6   11.65       0   11.65       2   10.65
     3.3   10.25     3.3    9.75    10.4    9.75    10.4   10.25    12.1   11.55
    16.1   11.55    16.4   11.75    26.4   11.75
#Mann= 3 , 0 , 0
   -11.3    .035       0       0    .035       0    16.4    .035       0
#XS Ineff= 2 , 0
       0       0   11.65    16.4       0   11.75
Permanent Ineff=
       F       F
Bank Sta=0,16.4
XS Rating Curve= 0
Exp/Cntr=.3,.1

Type RM Length L Ch R = 1 ,20      ,38,38,38
#Sta/Elev= 10
   -11.1   11.17    -1.1   11.17     -.7   11.57       0   11.57     1.4   10.27
     2.7    9.87     3.5    9.27     9.2    9.27      11   11.17      21   11.17
#Mann= 3 , 0 , 0
   -11.1    .035       0       0    .035       0      11    .035       0
#XS Ineff= 2 , 0
               0   11.57      11           11.17
Permanent Ineff=
       F       F
Bank Sta=0,11
XS Rating Curve= 0
Exp/Cntr=.3,.1