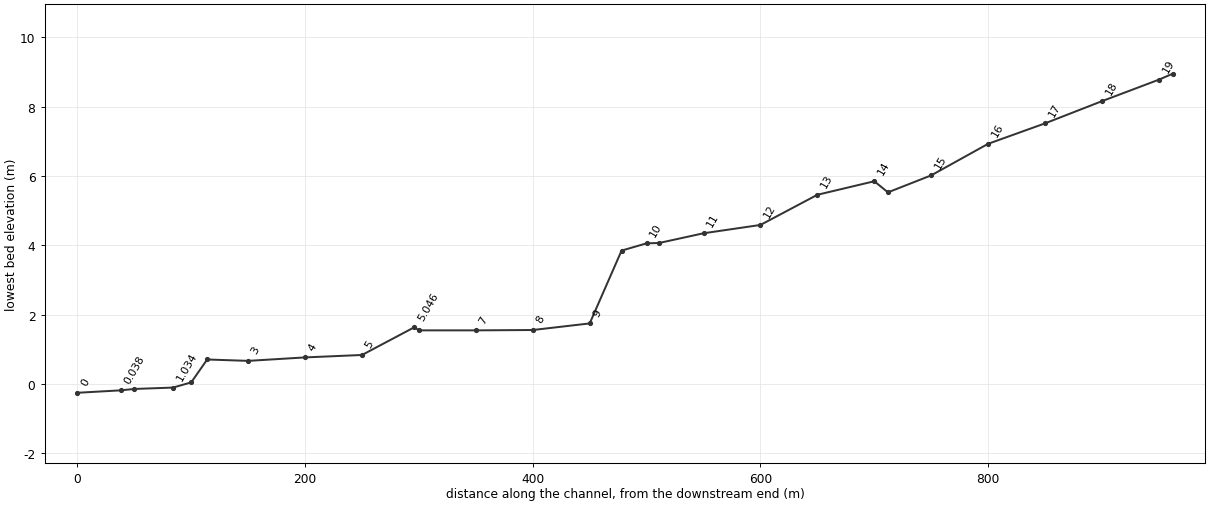
HEC-RAS study wonman-ch.prj: wonman-ch

--- wonman-ch.g01 (geometry) --- (continued)

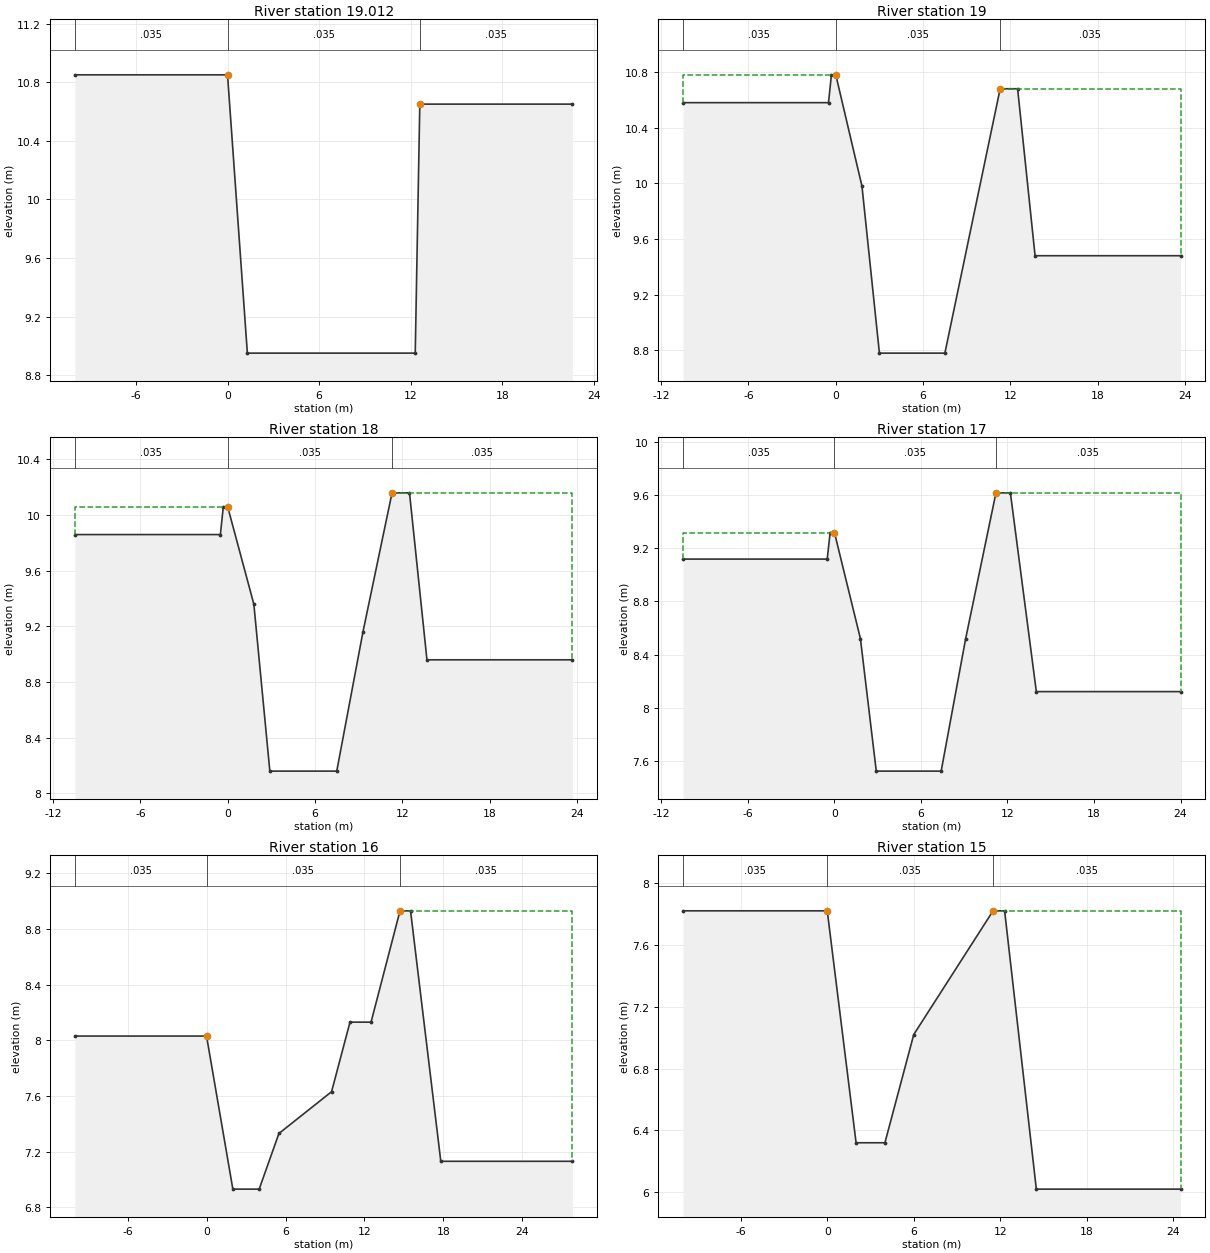
Type RM Length L Ch R = 1 ,19.012  ,12,12,12
#Sta/Elev= 6
     -10   10.85       0   10.85     1.3    8.95    12.3    8.95    12.6   10.65
    22.6   10.65
#Mann= 3 , 0 , 0
     -10    .035       0       0    .035       0    12.6    .035       0
#XS Ineff= 2 , 0
               0   10.85    12.6           10.65
Permanent Ineff=
       F       F
Bank Sta=0,12.6
XS Rating Curve= 0
Exp/Cntr=.3,.1

Type RM Length L Ch R = 1 ,19      ,50,50,50
#Sta/Elev= 11
   -10.5   10.58     -.5   10.58     -.3   10.78       0   10.78     1.8    9.98
       3    8.78     7.5    8.78    11.3   10.68    12.5   10.68    13.7    9.48
    23.7    9.48
#Mann= 3 , 0 , 0
   -10.5    .035       0       0    .035       0    11.3    .035       0
#XS Ineff= 2 , 0
               0   10.78    11.3           10.68
Permanent Ineff=
       F       F
Bank Sta=0,11.3
XS Rating Curve= 0
Exp/Cntr=.3,.1

Type RM Length L Ch R = 1 ,18      ,50,50,50
#Sta/Elev= 12
   -10.5    9.86     -.5    9.86     -.3   10.06       0   10.06     1.8    9.36
     2.9    8.16     7.5    8.16     9.3    9.16    11.3   10.16    12.5   10.16
    13.7    8.96    23.7    8.96
#Mann= 3 , 0 , 0
   -10.5    .035       0       0    .035       0    11.3    .035       0
#XS Ineff= 2 , 0
               0   10.06    11.3           10.16
Permanent Ineff=
       F       F
Bank Sta=0,11.3
XS Rating Curve= 0
Exp/Cntr=.3,.1

Type RM Length L Ch R = 1 ,17      ,50,50,50
#Sta/Elev= 13
   -10.5    9.12     -.5    9.12     -.3    9.32       0    9.32       0    9.32
     1.8    8.52     2.9    7.52     7.4    7.52     9.1    8.52    11.2    9.62
    12.2    9.62      14    8.12      24    8.12
#Mann= 3 , 0 , 0
   -10.5    .035       0       0    .035       0    11.2    .035       0
#XS Ineff= 2 , 0
               0    9.32    11.2            9.62
Permanent Ineff=
       F       F
Bank Sta=0,11.2
XS Rating Curve= 0
Exp/Cntr=.3,.1

Type RM Length L Ch R = 1 ,16      ,50,50,50
#Sta/Elev= 12
     -10    8.03       0    8.03       2    6.93       4    6.93     5.5    7.33
     9.5    7.63    10.9    8.13    12.5    8.13    14.7    8.93    15.5    8.93
    17.8    7.13    27.8    7.13
#Mann= 3 , 0 , 0
     -10    .035       0       0    .035       0    14.7    .035       0
#XS Ineff= 2 , 0
               0    8.03    14.7            8.93
Permanent Ineff=
       F       F
Bank Sta=0,14.7
XS Rating Curve= 0
Exp/Cntr=.3,.1

Type RM Length L Ch R = 1 ,15      ,38,38,38
#Sta/Elev= 9
     -10    7.82       0    7.82       2    6.32       4    6.32       6    7.02
    11.5    7.82    12.3    7.82    14.5    6.02    24.5    6.02
#Mann= 3 , 0 , 0
     -10    .035       0       0    .035       0    11.5    .035       0
#XS Ineff= 2 , 0
               0    7.82    11.5            7.82
Permanent Ineff=
       F       F
Bank Sta=0,11.5
XS Rating Curve= 0
Exp/Cntr=.3,.1

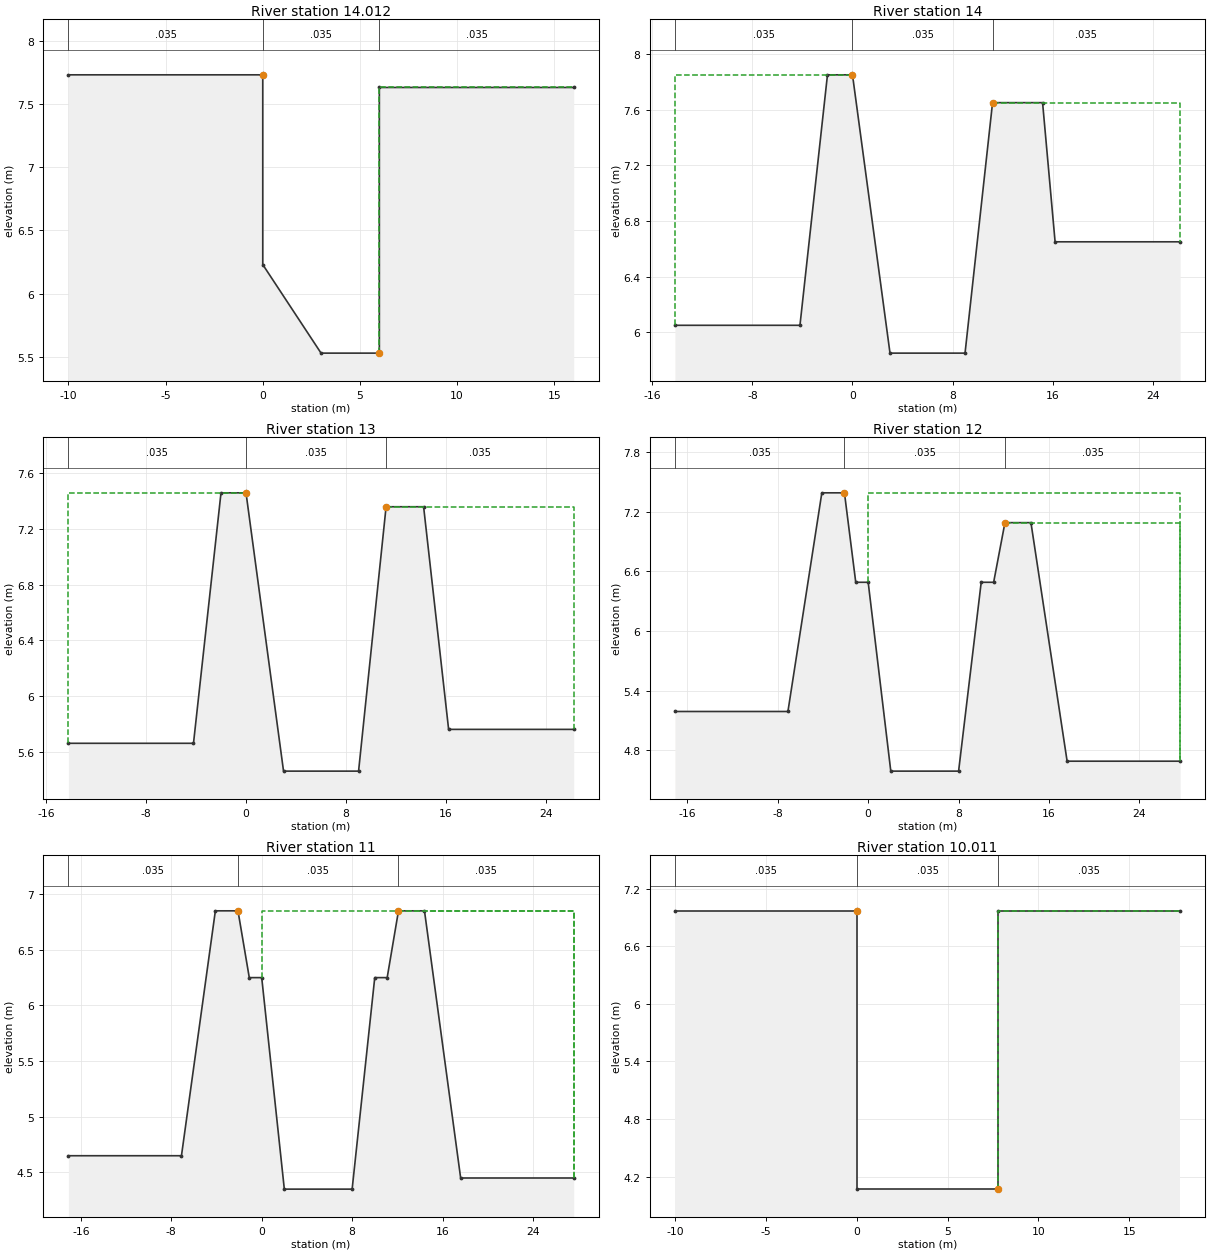
Type RM Length L Ch R = 1 ,14.012  ,12,12,12
#Sta/Elev= 7
     -10    7.73       0    7.73       0    6.23       3    5.53       6    5.53
       6    7.63      16    7.63
#Mann= 3 , 0 , 0
     -10    .035       0       0    .035       0       6    .035       0
#XS Ineff= 2 , 0
               0    7.73       6            7.63
Permanent Ineff=
       F       F
Bank Sta=0,6
XS Rating Curve= 0
Exp/Cntr=.3,.1

Type RM Length L Ch R = 1 ,14      ,50,50,50
#Sta/Elev= 10
   -14.2    6.05    -4.2    6.05      -2    7.85       0    7.85       3    5.85
       9    5.85    11.2    7.65    15.2    7.65    16.2    6.65    26.2    6.65
#Mann= 3 , 0 , 0
   -14.2    .035       0       0    .035       0    11.2    .035       0
#XS Ineff= 2 , 0
               0    7.85    11.2            7.65
Permanent Ineff=
       F       F
Bank Sta=0,11.2
XS Rating Curve= 0
Exp/Cntr=.3,.1

Type RM Length L Ch R = 1 ,13      ,50,50,50
#Sta/Elev= 10
   -14.2    5.66    -4.2    5.66      -2    7.46       0    7.46       3    5.46
       9    5.46    11.2    7.36    14.2    7.36    16.2    5.76    26.2    5.76
#Mann= 3 , 0 , 0
   -14.2    .035       0       0    .035       0    11.2    .035       0
#XS Ineff= 2 , 0
               0    7.46    11.2            7.36
Permanent Ineff=
       F       F
Bank Sta=0,11.2
XS Rating Curve= 0
Exp/Cntr=.3,.1

Type RM Length L Ch R = 1 ,12      ,50,50,50
#Sta/Elev= 14
   -17.1    5.19    -7.1    5.19    -4.1    7.39    -2.1    7.39    -1.1    6.49
       0    6.49       2    4.59       8    4.59      10    6.49    11.1    6.49
    12.1    7.09    14.4    7.09    17.6    4.69    27.6    4.69
#Mann= 3 , 0 , 0
   -17.1    .035       0    -2.1    .035       0    12.1    .035       0
#XS Ineff= 2 , 0
       0    -2.1    7.39    12.1       0    7.09
Permanent Ineff=
       F       F
Bank Sta=-2.1,12.1
XS Rating Curve= 0
Exp/Cntr=.3,.1

Type RM Length L Ch R = 1 ,11      ,39,39,39
#Sta/Elev= 14
   -17.1    4.65    -7.1    4.65    -4.1    6.85    -2.1    6.85    -1.1    6.25
       0    6.25       2    4.35       8    4.35      10    6.25    11.1    6.25
    12.1    6.85    14.4    6.85    17.6    4.45    27.6    4.45
#Mann= 3 , 0 , 0
   -17.1    .035       0    -2.1    .035       0    12.1    .035       0
#XS Ineff= 2 , 0
       0    -2.1    6.85    12.1       0    6.85
Permanent Ineff=
       F       F
Bank Sta=-2.1,12.1
XS Rating Curve= 0
Exp/Cntr=.3,.1

Type RM Length L Ch R = 1 ,10.011  ,11,11,11
#Sta/Elev= 6
     -10    6.97       0    6.97       0    4.07     7.8    4.07     7.8    6.97
    17.8    6.97
#Mann= 3 , 0 , 0
     -10    .035       0       0    .035       0     7.8    .035       0
#XS Ineff= 2 , 0
               0    6.97     7.8            6.97
Permanent Ineff=
       F       F
Bank Sta=0,7.8
XS Rating Curve= 0
Exp/Cntr=.3,.1

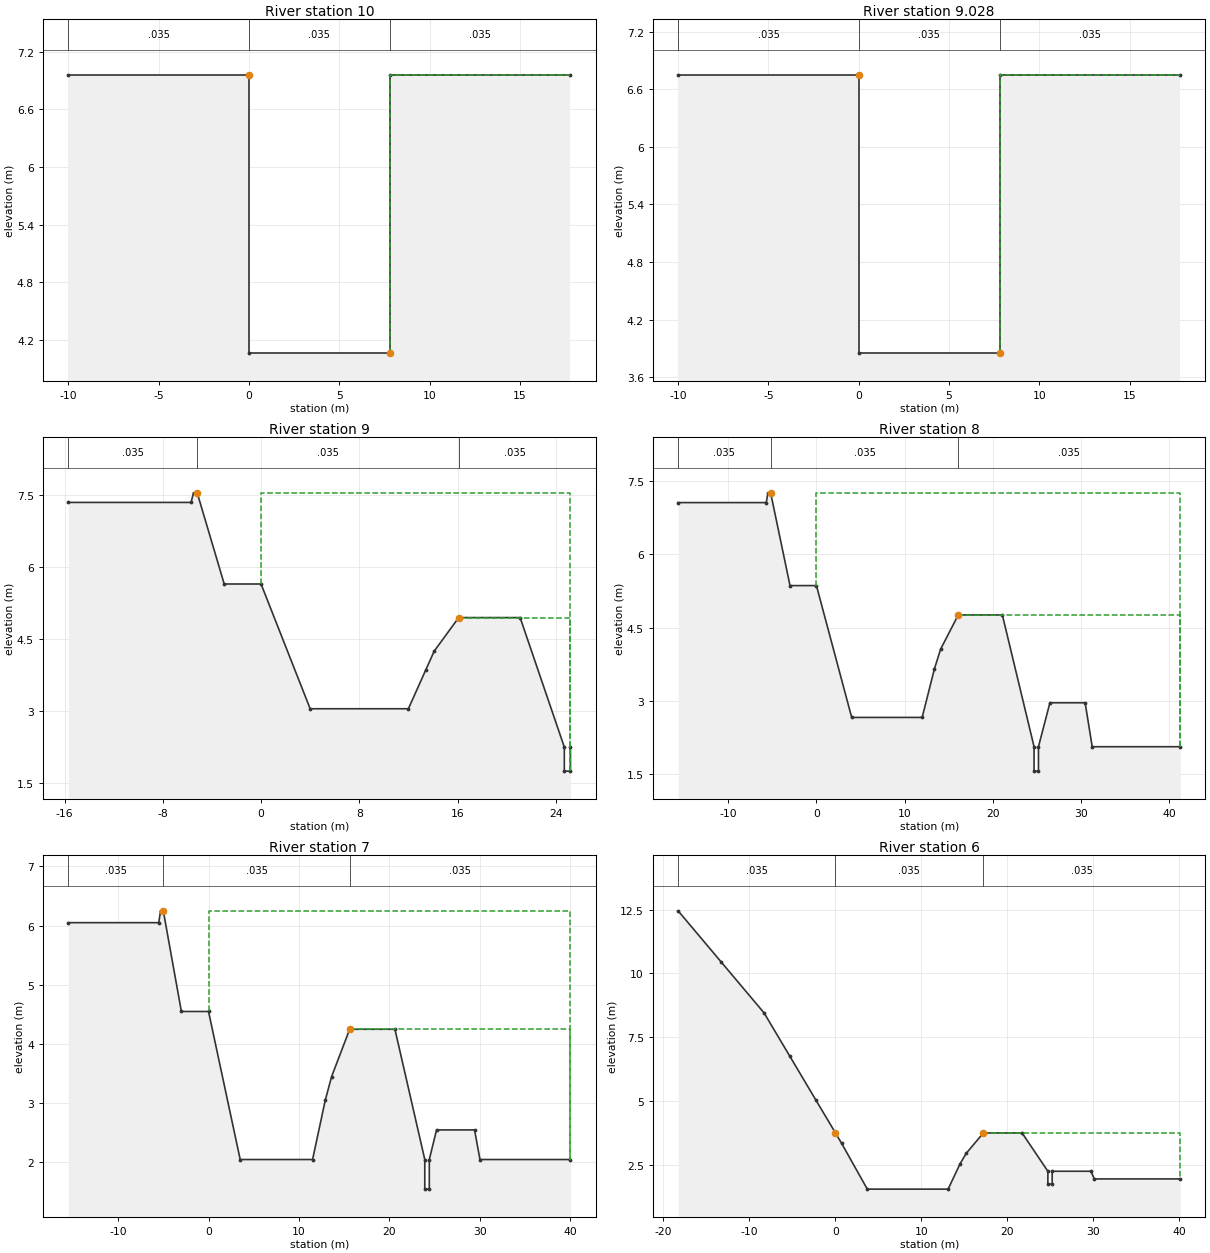
Type RM Length L Ch R = 1 ,10      ,22,22,22
#Sta/Elev= 6
     -10    6.96       0    6.96       0    4.06     7.8    4.06     7.8    6.96
    17.8    6.96
#Mann= 3 , 0 , 0
     -10    .035       0       0    .035       0     7.8    .035       0
#XS Ineff= 2 , 0
               0    6.96     7.8            6.96
Permanent Ineff=
       F       F
Bank Sta=0,7.8
XS Rating Curve= 0
Exp/Cntr=.3,.1

Type RM Length L Ch R = 1 ,9.028   ,28,28,28
#Sta/Elev= 6
     -10    6.75       0    6.75       0    3.85     7.8    3.85     7.8    6.75
    17.8    6.75
#Mann= 3 , 0 , 0
     -10    .035       0       0    .035       0     7.8    .035       0
#XS Ineff= 2 , 0
               0    6.75     7.8            6.75
Permanent Ineff=
       F       F
Bank Sta=0,7.8
XS Rating Curve= 0
Exp/Cntr=.3,.1

Type RM Length L Ch R = 1 ,9       ,50,50,50
#Sta/Elev= 16
   -15.7    7.35    -5.7    7.35    -5.5    7.55    -5.2    7.55      -3    5.65
       0    5.65       4    3.05      12    3.05    13.4    3.85    14.1    4.25
    16.1    4.95    21.1    4.95    24.7    2.25    24.7    1.75    25.2    1.75
    25.2    2.25
#Mann= 3 , 0 , 0
   -15.7    .035       0    -5.2    .035       0    16.1    .035       0
#XS Ineff= 2 , 0
       0    -5.2    7.55    16.1       0    4.95
Permanent Ineff=
       F       F
Bank Sta=-5.2,16.1
XS Rating Curve= 0
Exp/Cntr=.3,.1

Type RM Length L Ch R = 1 ,8       ,50,50,50
#Sta/Elev= 20
   -15.7    7.06    -5.7    7.06    -5.5    7.26    -5.2    7.26      -3    5.36
       0    5.36       4    2.66      12    2.66    13.4    3.66    14.1    4.06
    16.1    4.76    21.1    4.76    24.7    2.06    24.7    1.56    25.2    1.56
    25.2    2.06    26.5    2.96    30.5    2.96    31.3    2.06    41.3    2.06
#Mann= 3 , 0 , 0
   -15.7    .035       0    -5.2    .035       0    16.1    .035       0
#XS Ineff= 2 , 0
       0    -5.2    7.26    16.1       0    4.76
Permanent Ineff=
       F       F
Bank Sta=-5.2,16.1
XS Rating Curve= 0
Exp/Cntr=.3,.1

Type RM Length L Ch R = 1 ,7       ,50,50,50
#Sta/Elev= 20
   -15.5    6.05    -5.5    6.05    -5.3    6.25      -5    6.25      -3    4.55
       0    4.55     3.5    2.05    11.5    2.05    12.9    3.05    13.6    3.45
    15.6    4.25    20.6    4.25    23.9    2.05    23.9    1.55    24.4    1.55
    24.4    2.05    25.2    2.55    29.4    2.55      30    2.05      40    2.05
#Mann= 3 , 0 , 0
   -15.5    .035       0      -5    .035       0    15.6    .035       0
#XS Ineff= 2 , 0
       0      -5    6.25    15.6       0    4.25
Permanent Ineff=
       F       F
Bank Sta=-5,15.6
XS Rating Curve= 0
Exp/Cntr=.3,.1

Type RM Length L Ch R = 1 ,6       ,4,4,4
#Sta/Elev= 20
   -18.3   12.45   -13.3   10.45    -8.3    8.45    -5.3    6.75    -2.3    5.05
       0    3.75      .7    3.35     3.7    1.55    13.1    1.55    14.5    2.55
    15.2    2.95    17.2    3.75    21.7    3.75    24.7    2.25    24.7    1.75
    25.2    1.75    25.2    2.25    29.7    2.25    30.1    1.95    40.1    1.95
#Mann= 3 , 0 , 0
   -18.3    .035       0       0    .035       0    17.2    .035       0
#XS Ineff= 2 , 0
               0    3.75    17.2            3.75
Permanent Ineff=
       F       F
Bank Sta=0,17.2
XS Rating Curve= 0
Exp/Cntr=.3,.1

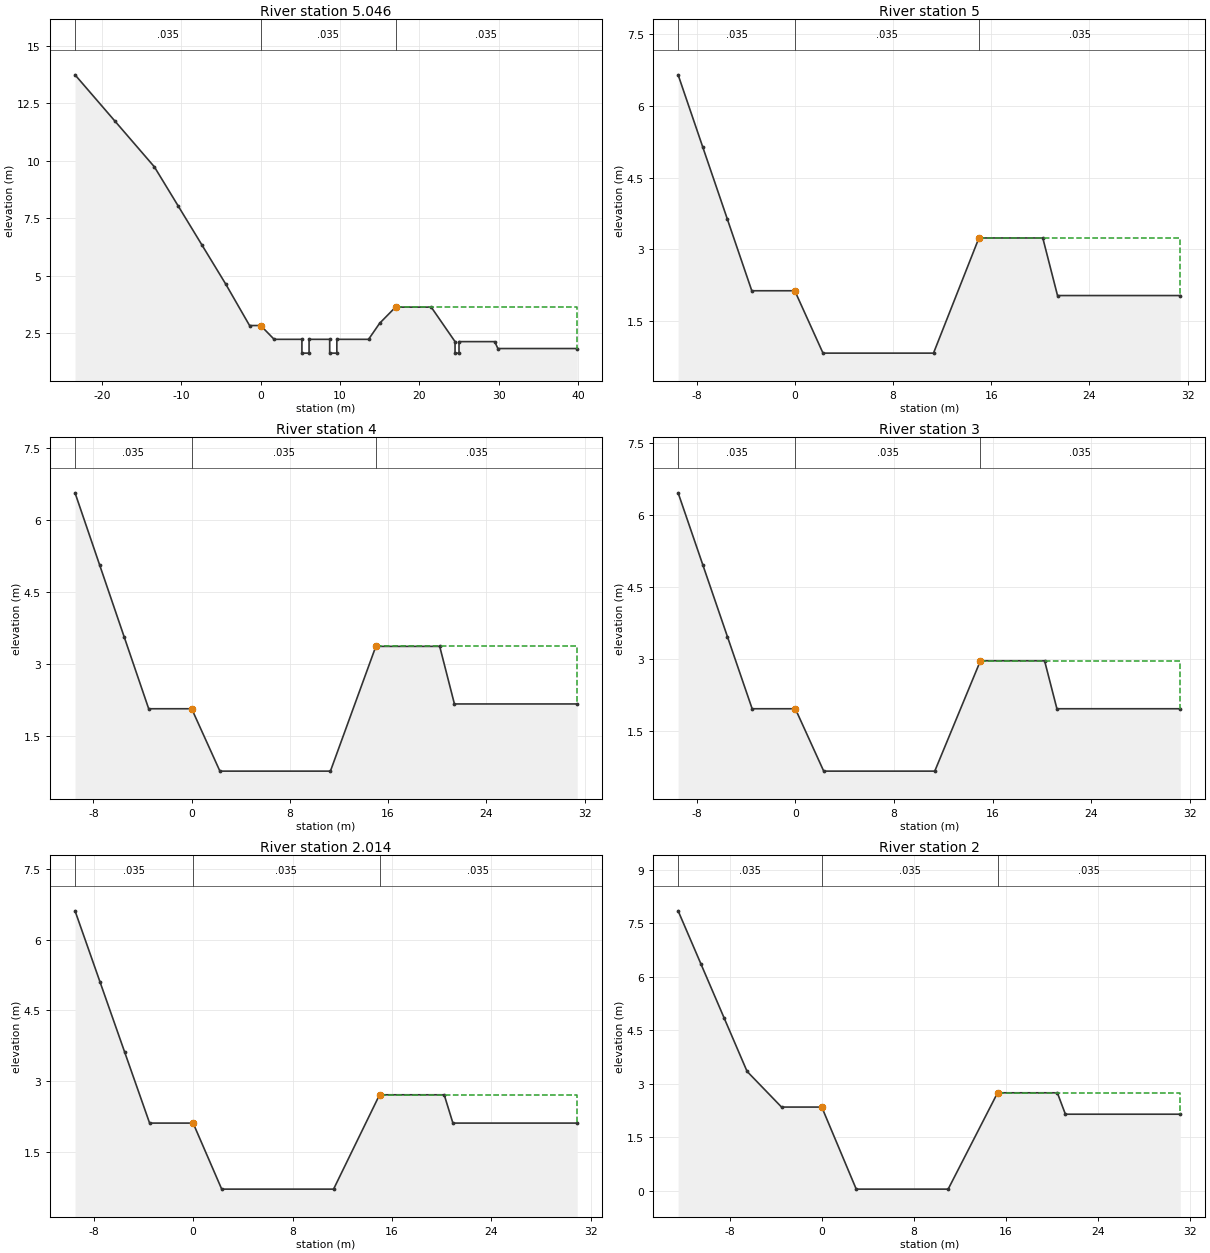
Type RM Length L Ch R = 1 ,5.046   ,46,46,46
#Sta/Elev= 28
   -23.4   13.74   -18.4   11.74   -13.4    9.74   -10.4    8.04    -7.4    6.34
    -4.4    4.64    -1.4    2.84       0    2.84     1.7    2.24     5.2    2.24
     5.2    1.64     6.1    1.64     6.1    2.24     8.7    2.24     8.7    1.64
     9.6    1.64     9.6    2.24    13.6    2.24      15    2.94      17    3.64
    21.5    3.64    24.5    2.14    24.5    1.64      25    1.64      25    2.14
    29.5    2.14    29.9    1.84    39.9    1.84
#Mann= 3 , 0 , 0
   -23.4    .035       0       0    .035       0      17    .035       0
#XS Ineff= 2 , 0
               0    2.84      17            3.64
Permanent Ineff=
       F       F
Bank Sta=0,17
XS Rating Curve= 0
Exp/Cntr=.3,.1

Type RM Length L Ch R = 1 ,5       ,50,50,50
#Sta/Elev= 11
    -9.5    6.64    -7.5    5.14    -5.5    3.64    -3.5    2.14       0    2.14
     2.3     .84    11.3     .84      15    3.24    20.2    3.24    21.4    2.04
    31.4    2.04
#Mann= 3 , 0 , 0
    -9.5    .035       0       0    .035       0      15    .035       0
#XS Ineff= 2 , 0
               0    2.14      15            3.24
Permanent Ineff=
       F       F
Bank Sta=0,15
XS Rating Curve= 0
Exp/Cntr=.3,.1

Type RM Length L Ch R = 1 ,4       ,50,50,50
#Sta/Elev= 11
    -9.5    6.57    -7.5    5.07    -5.5    3.57    -3.5    2.07       0    2.07
     2.3     .77    11.3     .77      15    3.37    20.2    3.37    21.4    2.17
    31.4    2.17
#Mann= 3 , 0 , 0
    -9.5    .035       0       0    .035       0      15    .035       0
#XS Ineff= 2 , 0
               0    2.07      15            3.37
Permanent Ineff=
       F       F
Bank Sta=0,15
XS Rating Curve= 0
Exp/Cntr=.3,.1

Type RM Length L Ch R = 1 ,3       ,36,36,36
#Sta/Elev= 11
    -9.5    6.47    -7.5    4.97    -5.5    3.47    -3.5    1.97       0    1.97
     2.3     .67    11.3     .67      15    2.97    20.2    2.97    21.2    1.97
    31.2    1.97
#Mann= 3 , 0 , 0
    -9.5    .035       0       0    .035       0      15    .035       0
#XS Ineff= 2 , 0
               0    1.97      15            2.97
Permanent Ineff=
       F       F
Bank Sta=0,15
XS Rating Curve= 0
Exp/Cntr=.3,.1

Type RM Length L Ch R = 1 ,2.014   ,14,14,14
#Sta/Elev= 11
    -9.5    6.61    -7.5    5.11    -5.5    3.61    -3.5    2.11       0    2.11
     2.3     .71    11.3     .71      15    2.71    20.2    2.71    20.9    2.11
    30.9    2.11
#Mann= 3 , 0 , 0
    -9.5    .035       0       0    .035       0      15    .035       0
#XS Ineff= 2 , 0
               0    2.11      15            2.71
Permanent Ineff=
       F       F
Bank Sta=0,15
XS Rating Curve= 0
Exp/Cntr=.3,.1

Type RM Length L Ch R = 1 ,2       ,16,16,16
#Sta/Elev= 12
   -12.5    7.85   -10.5    6.35    -8.5    4.85    -6.5    3.35    -3.5    2.35
       0    2.35       3     .05      11     .05    15.3    2.75    20.5    2.75
    21.2    2.15    31.2    2.15
#Mann= 3 , 0 , 0
   -12.5    .035       0       0    .035       0    15.3    .035       0
#XS Ineff= 2 , 0
               0    2.35    15.3            2.75
Permanent Ineff=
       F       F
Bank Sta=0,15.3
XS Rating Curve= 0
Exp/Cntr=.3,.1

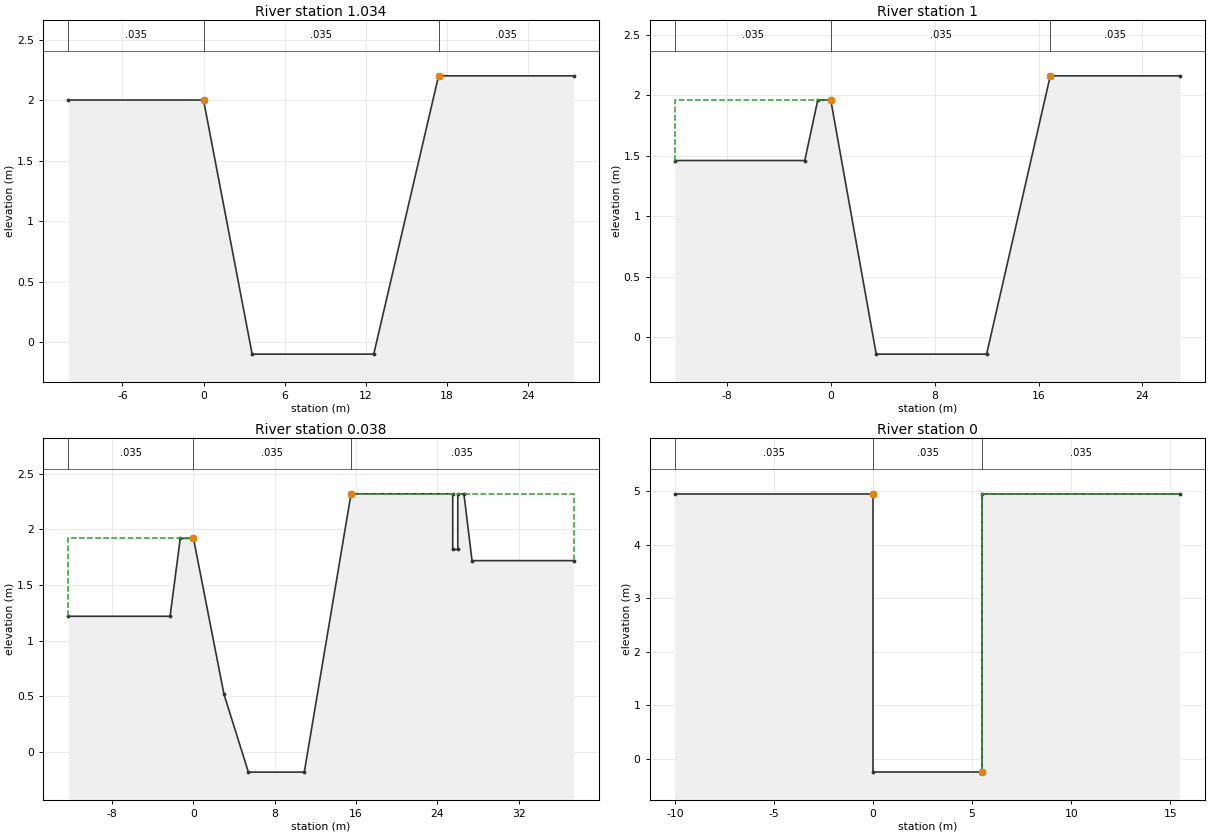
Type RM Length L Ch R = 1 ,1.034   ,34,34,34
#Sta/Elev= 6
     -10       2       0       2     3.6     -.1    12.6     -.1    17.4     2.2
    27.4     2.2
#Mann= 3 , 0 , 0
     -10    .035       0       0    .035       0    17.4    .035       0
#XS Ineff= 2 , 0
               0       2    17.4             2.2
Permanent Ineff=
       F       F
Bank Sta=0,17.4
XS Rating Curve= 0
Exp/Cntr=.3,.1

Type RM Length L Ch R = 1 ,1       ,12,12,12
#Sta/Elev= 8
     -12    1.46      -2    1.46      -1    1.96       0    1.96     3.5    -.14
      12    -.14    16.9    2.16    26.9    2.16
#Mann= 3 , 0 , 0
     -12    .035       0       0    .035       0    16.9    .035       0
#XS Ineff= 2 , 0
               0    1.96    16.9            2.16
Permanent Ineff=
       F       F
Bank Sta=0,16.9
XS Rating Curve= 0
Exp/Cntr=.3,.1

Type RM Length L Ch R = 1 ,0.038   ,38,38,38
#Sta/Elev= 15
   -12.3    1.22    -2.3    1.22    -1.3    1.92       0    1.92       3     .52
     5.4    -.18    10.9    -.18    15.5    2.32    25.5    2.32    25.5    1.82
      26    1.82      26    2.32    26.6    2.32    27.4    1.72    37.4    1.72
#Mann= 3 , 0 , 0
   -12.3    .035       0       0    .035       0    15.5    .035       0
#XS Ineff= 2 , 0
               0    1.92    15.5            2.32
Permanent Ineff=
       F       F
Bank Sta=0,15.5
XS Rating Curve= 0
Exp/Cntr=.3,.1

Type RM Length L Ch R = 1 ,0       ,0,0,0
#Sta/Elev= 6
     -10    4.95       0    4.95       0    -.25     5.5    -.25     5.5    4.95
    15.5    4.95
#Mann= 3 , 0 , 0
     -10    .035       0       0    .035       0     5.5    .035       0
#XS Ineff= 2 , 0
               0    4.95     5.5            4.95
Permanent Ineff=
       F       F
Bank Sta=0,5.5
XS Rating Curve= 0
Exp/Cntr=.3,.1

Chan Stop Cuts=-1