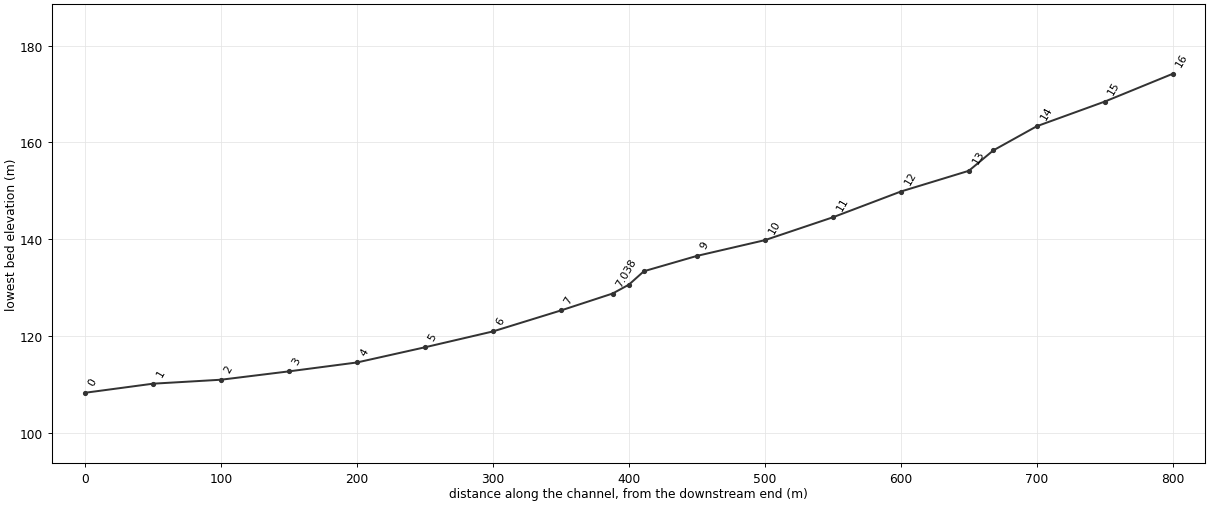
--- chungeun-ch.prj (project) ---

Proj Title=chungeun-ch
Current Plan=p01
Default Exp/Contr=.3,.1
SI Units
Geom File=g01
Flow File=f01
Plan File=p01
Y Axis Title=Elevation
X Axis Title(PF)=Main Channel Distance
X Axis Title(XS)=Station
BEGIN DESCRIPTION:
           BACK WATER COMPUTATION
      APPLICATION OF HEC-2 BY Samju Construction Engineering
      chungeun-ch: 10,20,30,50,80 yr
END DESCRIPTION:
DSS Export Rating Curves= 0
DSS Export Rating Curve Sorted= 0
DSS Export Volume Flow Curves= 0
DXF OffsetX= 0
DXF OffsetY= 0
DXF ScaleX= 1
DXF ScaleY= 10

--- chungeun-ch.p01 (plan) ---

Plan Title=Imported Plan 01
Version=Version 3.0.1  Mar 2001
Short Identifier=Imported Pla
Geom File=g01
Flow File=f01
Subcritical Flow
K Sum by GR= 0
Std Step Tol= 0.003
Critical Tol= 0.003
Num of Std Step Trials= 20
Max Error Tol= 0.1
Flow Tol Ratio= 0.001
Split Flow NTrial= 30
Split Flow Tol= 0.02
Split Flow Ratio= 0.02
Log Output Level= 0
Friction Slope Method= 1
Unsteady Friction Slope Method= 2
Parabolic Critical Depth
Global Vel Dist= 0 , 0 , 0
Global Log Level= 0
CheckData=True
Encroach Param=-1 ,0,0, 0
Computation Interval=1HOUR
Output Interval=1HOUR
Run HTab= 0
Run UNet= 0
Run PostProcess= 0
UNET Theta= 1
UNET ZTol= 0.02
UNET ZSATol= 0.1
UNET MxIter= 20
UNET MaxInSteps= 20
UNET DtIC= 0
UNET DtMin= 0
UNET MaxCRTS= 20
UNET WFStab= 2
UNET SFStab= 1
UNET WFX= 1
UNET SFX= 1
UNET Convert EG Bridges=-1
UNET Use Existing IB Tables=-1
Instantaneous Interval=1HOUR
Write IC File= 0
Write Velocity= 0
Write Detailed= 0

--- chungeun-ch.f01 (steady flow) ---

Flow Title=Imported Flow 01
Version=Version 3.0.1  Mar 2001
Number of Profiles= 5
Profile Names=PF 1,PF 2,PF 3,PF 4,PF 5
River Rch & RM=RIVER-1,Reach-1         ,16
     180     200     220     230     240
Boundary for River Rch & Prof#=RIVER-1,Reach-1         , 1
Up Type= 0
Dn Type= 3
Dn Slope=.0109
Boundary for River Rch & Prof#=RIVER-1,Reach-1         , 2
Up Type= 0
Dn Type= 3
Dn Slope=.0109
Boundary for River Rch & Prof#=RIVER-1,Reach-1         , 3
Up Type= 0
Dn Type= 3
Dn Slope=.0109
Boundary for River Rch & Prof#=RIVER-1,Reach-1         , 4
Up Type= 0
Dn Type= 3
Dn Slope=.0109
Boundary for River Rch & Prof#=RIVER-1,Reach-1         , 5
Up Type= 0
Dn Type= 3
Dn Slope=.0109
DSS Import GetInterval= 0
DSS Import GetPeak= 0
DSS Import FillOption= 0

--- chungeun-ch.g01 (geometry) ---

Geom Title=Imported Geom 01
Version=Version 3.0.1  Mar 2001

River Reach=RIVER-1         ,Reach-1
Reach XY= 2
              .5             .95              .5             .05

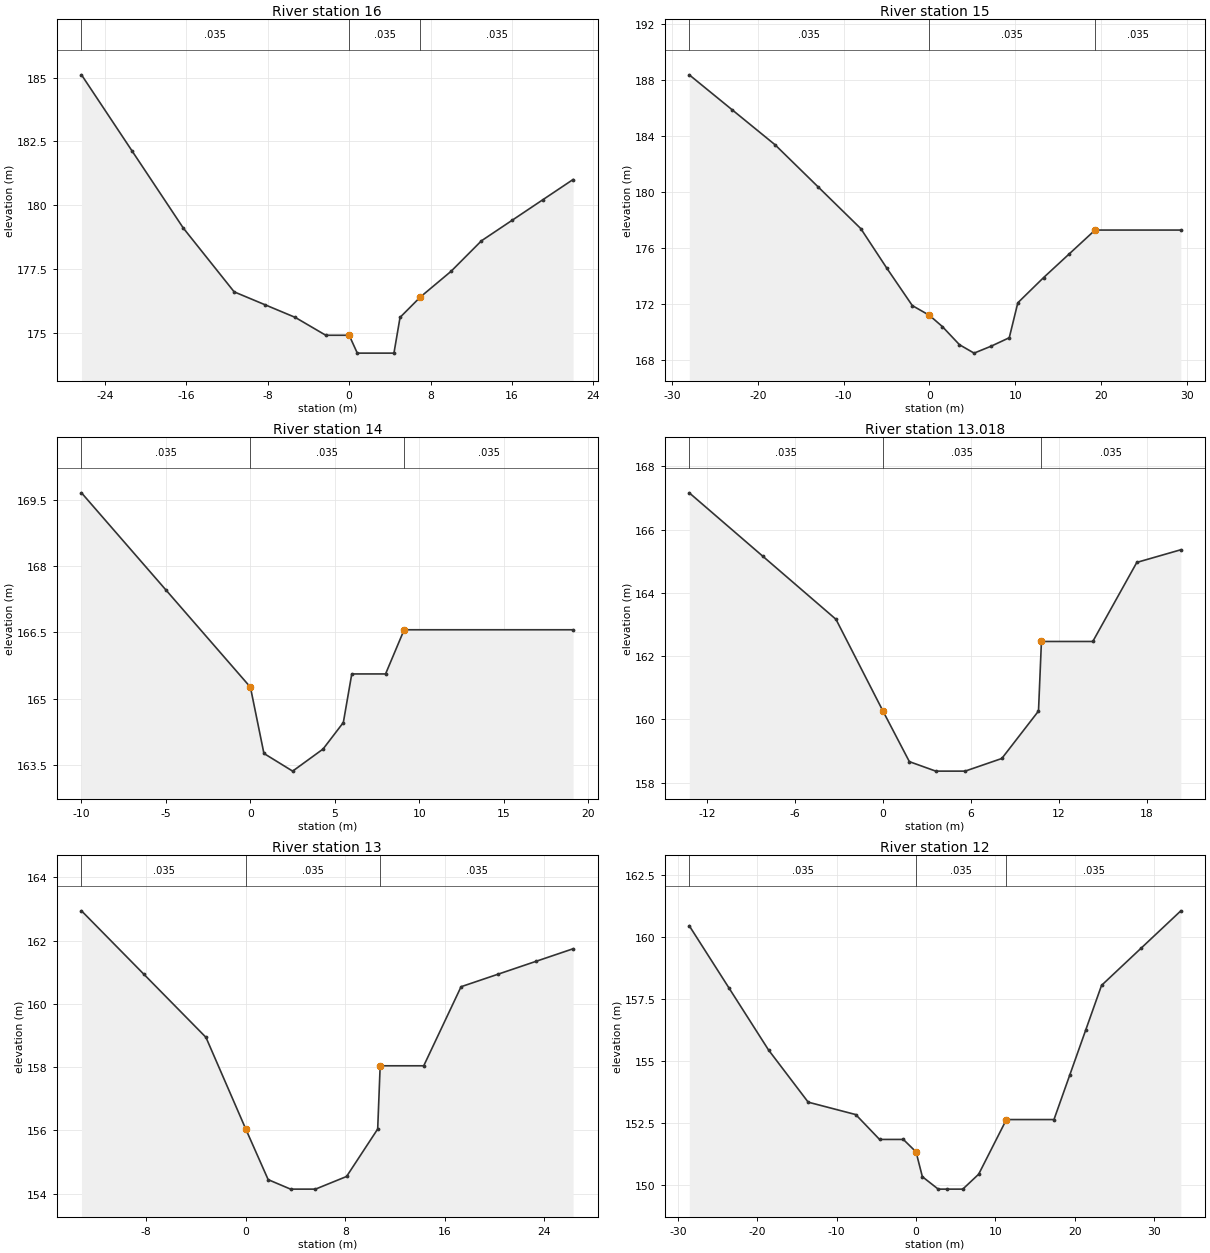
Type RM Length L Ch R = 1 ,16      ,50,50,50
#Sta/Elev= 17
   -26.3  185.11   -21.3  182.11   -16.3  179.11   -11.3  176.61    -8.3  176.11
    -5.3  175.61    -2.3  174.91       0  174.91      .8  174.21     4.4  174.21
       5  175.61       7  176.41      10  177.41      13  178.61      16  179.41
      19  180.21      22  181.01
#Mann= 3 , 0 , 0
   -26.3    .035       0       0    .035       0       7    .035       0
#XS Ineff= 2 , 0
               0  174.91       7          176.41
Permanent Ineff=
       F       F
Bank Sta=0,7
XS Rating Curve= 0
Exp/Cntr=.3,.1

Type RM Length L Ch R = 1 ,15      ,50,50,50
#Sta/Elev= 18
     -28  188.36     -23  185.86     -18  183.36     -13  180.36      -8  177.36
      -5  174.56      -2  171.86       0  171.16     1.5  170.36     3.5  169.06
     5.2  168.46     7.2  168.96     9.3  169.56    10.3  172.06    13.3  173.86
    16.3  175.56    19.3  177.26    29.3  177.26
#Mann= 3 , 0 , 0
     -28    .035       0       0    .035       0    19.3    .035       0
#XS Ineff= 2 , 0
       0       0  171.16    19.3       0  177.26
Permanent Ineff=
       F       F
Bank Sta=0,19.3
XS Rating Curve= 0
Exp/Cntr=.3,.1

Type RM Length L Ch R = 1 ,14      ,32,32,32
#Sta/Elev= 11
     -10  169.66      -5  167.46       0  165.26      .8  163.76     2.5  163.36
     4.3  163.86     5.5  164.46       6  165.56       8  165.56     9.1  166.56
    19.1  166.56
#Mann= 3 , 0 , 0
     -10    .035       0       0    .035       0     9.1    .035       0
#XS Ineff= 2 , 0
       0       0  165.26     9.1       0  166.56
Permanent Ineff=
       F       F
Bank Sta=0,9.1
XS Rating Curve= 0
Exp/Cntr=.3,.1

Type RM Length L Ch R = 1 ,13.018  ,18,18,18
#Sta/Elev= 13
   -13.2  167.16    -8.2  165.16    -3.2  163.16       0  160.26     1.8  158.66
     3.6  158.36     5.6  158.36     8.1  158.76    10.6  160.26    10.8  162.46
    14.3  162.46    17.3  164.96    20.3  165.36
#Mann= 3 , 0 , 0
   -13.2    .035       0       0    .035       0    10.8    .035       0
#XS Ineff= 2 , 0
               0  160.26    10.8          162.46
Permanent Ineff=
       F       F
Bank Sta=0,10.8
XS Rating Curve= 0
Exp/Cntr=.3,.1

Type RM Length L Ch R = 1 ,13      ,50,50,50
#Sta/Elev= 15
   -13.2  162.94    -8.2  160.94    -3.2  158.94       0  156.04     1.8  154.44
     3.6  154.14     5.6  154.14     8.1  154.54    10.6  156.04    10.8  158.04
    14.3  158.04    17.3  160.54    20.3  160.94    23.3  161.34    26.3  161.74
#Mann= 3 , 0 , 0
   -13.2    .035       0       0    .035       0    10.8    .035       0
#XS Ineff= 2 , 0
               0  156.04    10.8          158.04
Permanent Ineff=
       F       F
Bank Sta=0,10.8
XS Rating Curve= 0
Exp/Cntr=.3,.1

Type RM Length L Ch R = 1 ,12      ,50,50,50
#Sta/Elev= 20
   -28.6  160.45   -23.6  157.95   -18.6  155.45   -13.6  153.35    -7.6  152.85
    -4.6  151.85    -1.6  151.85       0  151.35      .8  150.35     2.8  149.85
     3.9  149.85     5.9  149.85     7.9  150.45    11.4  152.65    17.4  152.65
    19.4  154.45    21.4  156.25    23.4  158.05    28.4  159.55    33.4  161.05
#Mann= 3 , 0 , 0
   -28.6    .035       0       0    .035       0    11.4    .035       0
#XS Ineff= 2 , 0
               0  151.35    11.4          152.65
Permanent Ineff=
       F       F
Bank Sta=0,11.4
XS Rating Curve= 0
Exp/Cntr=.3,.1

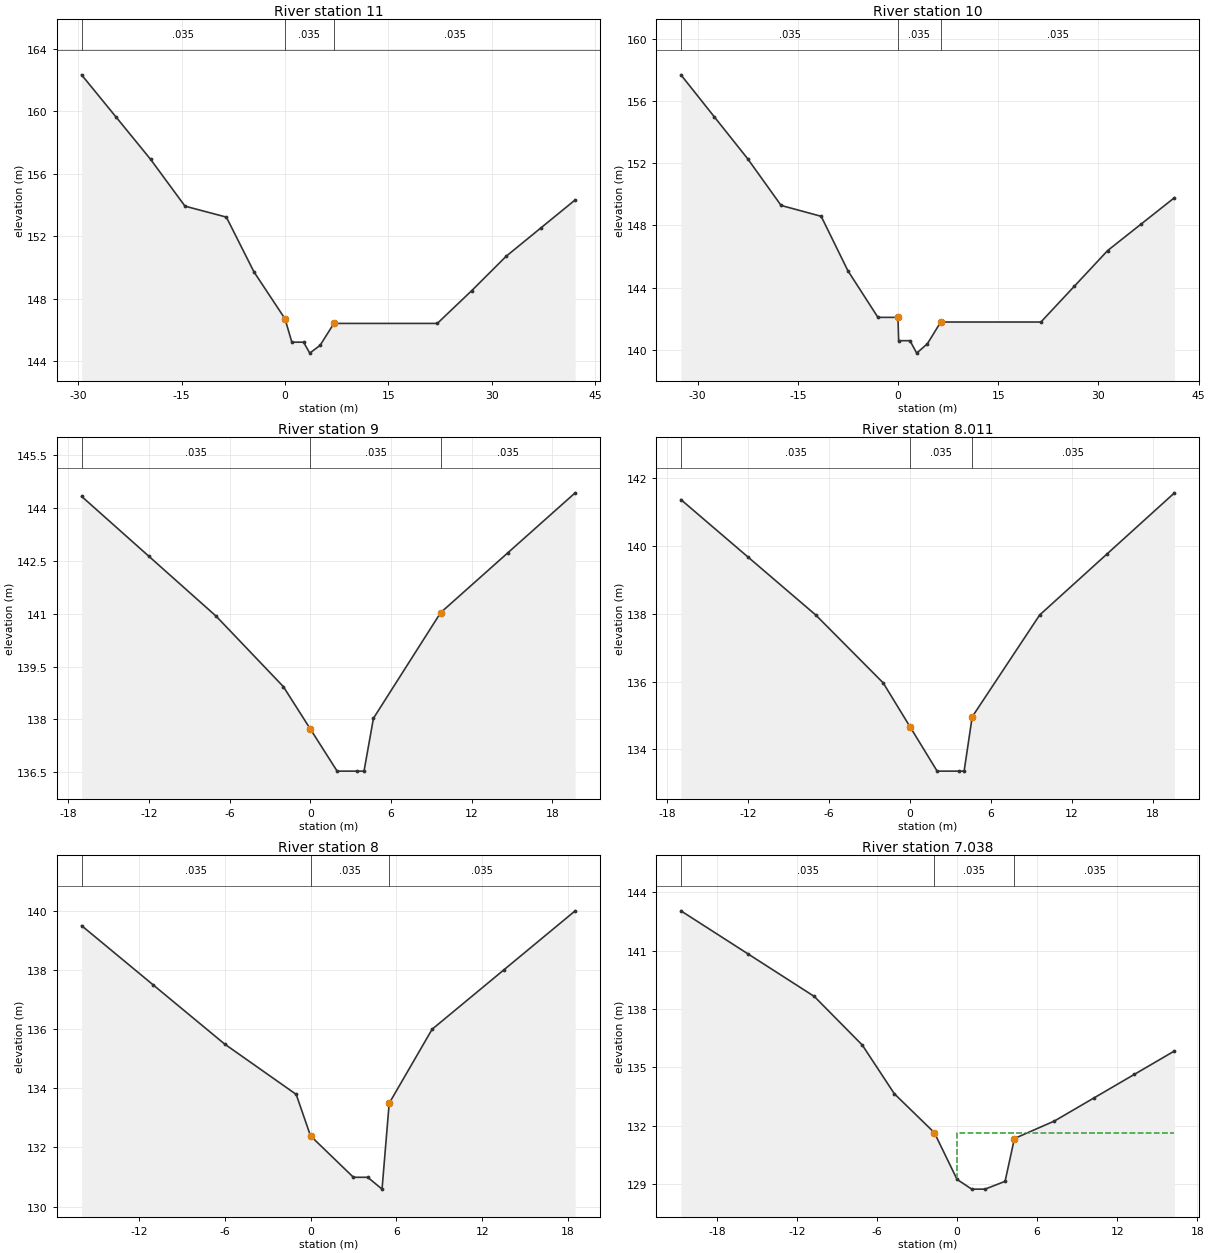
Type RM Length L Ch R = 1 ,11      ,50,50,50
#Sta/Elev= 17
   -29.5  162.32   -24.5  159.62   -19.5  156.92   -14.5  153.92    -8.5  153.22
    -4.5  149.72       0  146.72       1  145.22     2.7  145.22     3.6  144.52
     5.1  145.02     7.1  146.42    22.1  146.42    27.1  148.52    32.1  150.72
    37.1  152.52    42.1  154.32
#Mann= 3 , 0 , 0
   -29.5    .035       0       0    .035       0     7.1    .035       0
#XS Ineff= 2 , 0
               0  146.72     7.1          146.42
Permanent Ineff=
       F       F
Bank Sta=0,7.1
XS Rating Curve= 0
Exp/Cntr=.3,.1

Type RM Length L Ch R = 1 ,10      ,50,50,50
#Sta/Elev= 18
   -32.5  157.69   -27.5  154.99   -22.5  152.29   -17.5  149.29   -11.5  148.59
    -7.5  145.09      -3  142.09       0  142.09      .1  140.59     1.8  140.59
     2.8  139.79     4.4  140.39     6.4  141.79    21.4  141.79    26.4  144.09
    31.4  146.39    36.4  148.09    41.4  149.79
#Mann= 3 , 0 , 0
   -32.5    .035       0       0    .035       0     6.4    .035       0
#XS Ineff= 2 , 0
               0  142.09     6.4          141.79
Permanent Ineff=
       F       F
Bank Sta=0,6.4
XS Rating Curve= 0
Exp/Cntr=.3,.1

Type RM Length L Ch R = 1 ,9       ,39,39,39
#Sta/Elev= 12
     -17  144.33     -12  142.63      -7  140.93      -2  138.93       0  137.73
       2  136.53     3.5  136.53       4  136.53     4.7  138.03     9.7  141.03
    14.7  142.73    19.7  144.43
#Mann= 3 , 0 , 0
     -17    .035       0       0    .035       0     9.7    .035       0
#XS Ineff= 2 , 0
               0  137.73     9.7          141.03
Permanent Ineff=
       F       F
Bank Sta=0,9.7
XS Rating Curve= 0
Exp/Cntr=.3,.1

Type RM Length L Ch R = 1 ,8.011   ,11,11,11
#Sta/Elev= 12
     -17  141.36     -12  139.66      -7  137.96      -2  135.96       0  134.66
       2  133.36     3.6  133.36       4  133.36     4.6  134.96     9.6  137.96
    14.6  139.76    19.6  141.56
#Mann= 3 , 0 , 0
     -17    .035       0       0    .035       0     4.6    .035       0
#XS Ineff= 2 , 0
               0  134.66     4.6          134.96
Permanent Ineff=
       F       F
Bank Sta=0,4.6
XS Rating Curve= 0
Exp/Cntr=.3,.1

Type RM Length L Ch R = 1 ,8       ,12,12,12
#Sta/Elev= 12
     -16  139.49     -11  137.49      -6  135.49      -1  133.79       0  132.39
       3  130.99       4  130.99       5  130.59     5.5  133.49     8.5  135.99
    13.5  137.99    18.5  139.99
#Mann= 3 , 0 , 0
     -16    .035       0       0    .035       0     5.5    .035       0
#XS Ineff= 2 , 0
               0  132.39     5.5          133.49
Permanent Ineff=
       F       F
Bank Sta=0,5.5
XS Rating Curve= 0
Exp/Cntr=.3,.1

Type RM Length L Ch R = 1 ,7.038   ,38,38,38
#Sta/Elev= 15
   -20.7  143.05   -15.7  140.85   -10.7  138.65    -7.1  136.15    -4.7  133.65
    -1.7  131.65       0  129.25     1.1  128.75     2.1  128.75     3.6  129.15
     4.3  131.35     7.3  132.25    10.3  133.45    13.3  134.65    16.3  135.85
#Mann= 3 , 0 , 0
   -20.7    .035       0    -1.7    .035       0     4.3    .035       0
#XS Ineff= 2 , 0
       0    -1.7  131.65     4.3       0  131.35
Permanent Ineff=
       F       F
Bank Sta=-1.7,4.3
XS Rating Curve= 0
Exp/Cntr=.3,.1

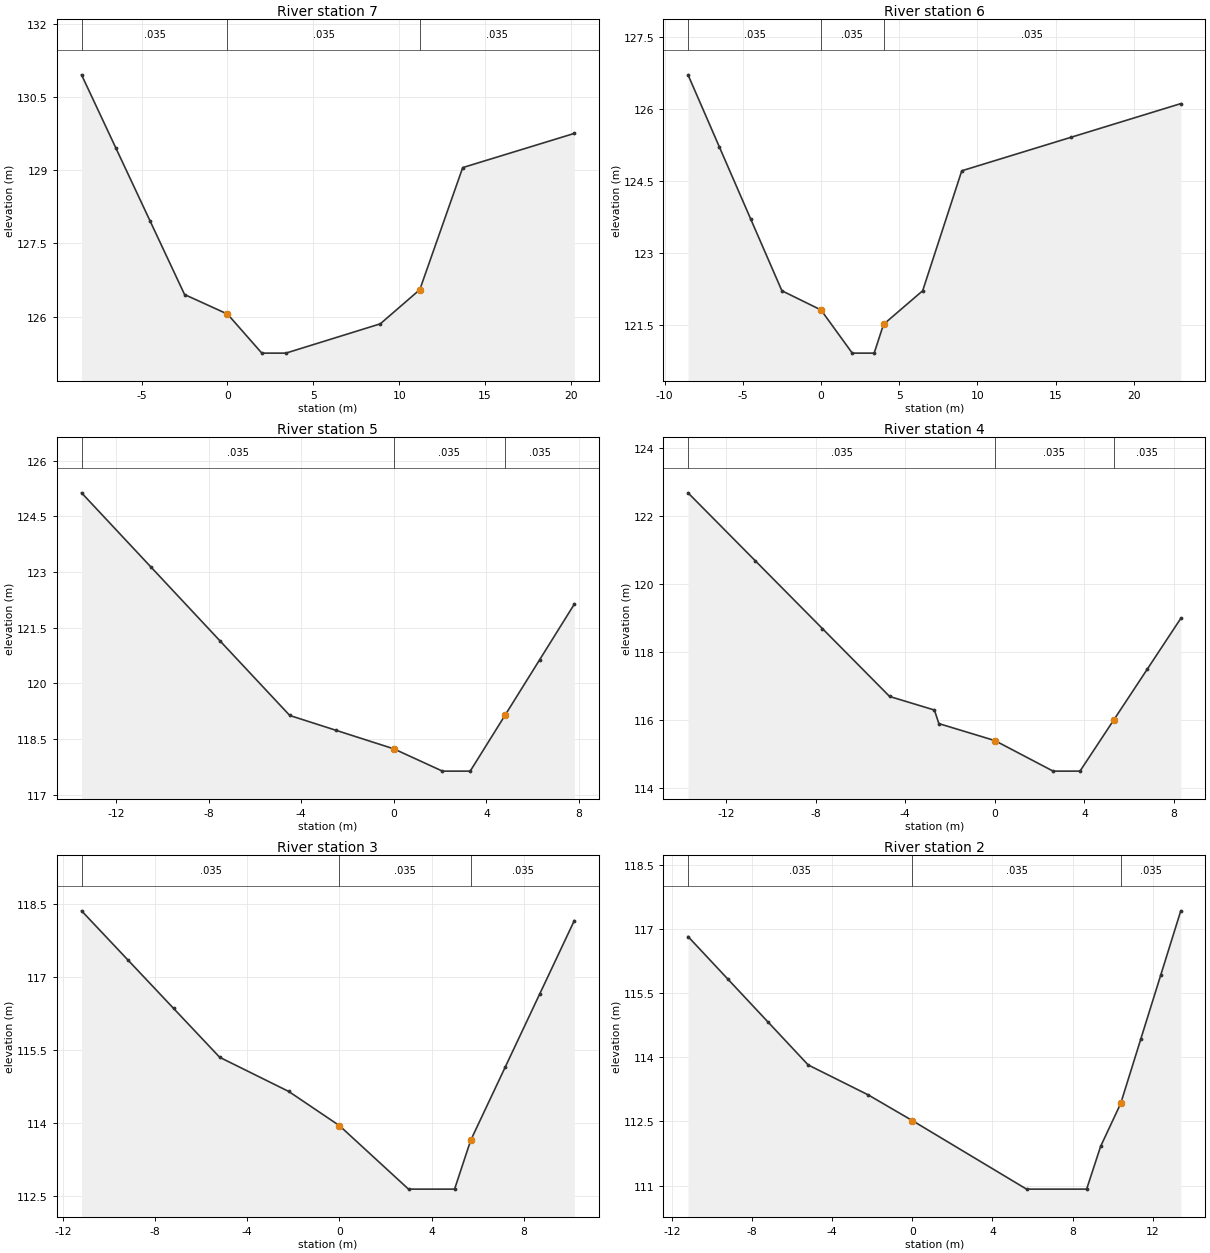
Type RM Length L Ch R = 1 ,7       ,50,50,50
#Sta/Elev= 11
    -8.5  130.95    -6.5  129.45    -4.5  127.95    -2.5  126.45       0  126.05
       2  125.25     3.4  125.25     8.9  125.85    11.2  126.55    13.7  129.05
    20.2  129.75
#Mann= 3 , 0 , 0
    -8.5    .035       0       0    .035       0    11.2    .035       0
#XS Ineff= 2 , 0
               0  126.05    11.2          126.55
Permanent Ineff=
       F       F
Bank Sta=0,11.2
XS Rating Curve= 0
Exp/Cntr=.3,.1

Type RM Length L Ch R = 1 ,6       ,50,50,50
#Sta/Elev= 12
    -8.5  126.71    -6.5  125.21    -4.5  123.71    -2.5  122.21       0  121.81
       2  120.91     3.4  120.91       4  121.51     6.5  122.21       9  124.71
      16  125.41      23  126.11
#Mann= 3 , 0 , 0
    -8.5    .035       0       0    .035       0       4    .035       0
#XS Ineff= 2 , 0
               0  121.81       4          121.51
Permanent Ineff=
       F       F
Bank Sta=0,4
XS Rating Curve= 0
Exp/Cntr=.3,.1

Type RM Length L Ch R = 1 ,5       ,50,50,50
#Sta/Elev= 11
   -13.5  125.13   -10.5  123.13    -7.5  121.13    -4.5  119.13    -2.5  118.73
       0  118.23     2.1  117.63     3.3  117.63     4.8  119.13     6.3  120.63
     7.8  122.13
#Mann= 3 , 0 , 0
   -13.5    .035       0       0    .035       0     4.8    .035       0
#XS Ineff= 2 , 0
               0  118.23     4.8          119.13
Permanent Ineff=
       F       F
Bank Sta=0,4.8
XS Rating Curve= 0
Exp/Cntr=.3,.1

Type RM Length L Ch R = 1 ,4       ,50,50,50
#Sta/Elev= 12
   -13.7  122.69   -10.7  120.69    -7.7  118.69    -4.7  116.69    -2.7  116.29
    -2.5  115.89       0  115.39     2.6  114.49     3.8  114.49     5.3  115.99
     6.8  117.49     8.3  118.99
#Mann= 3 , 0 , 0
   -13.7    .035       0       0    .035       0     5.3    .035       0
#XS Ineff= 2 , 0
               0  115.39     5.3          115.99
Permanent Ineff=
       F       F
Bank Sta=0,5.3
XS Rating Curve= 0
Exp/Cntr=.3,.1

Type RM Length L Ch R = 1 ,3       ,50,50,50
#Sta/Elev= 12
   -11.2  118.35    -9.2  117.35    -7.2  116.35    -5.2  115.35    -2.2  114.65
       0  113.95       3  112.65       5  112.65     5.7  113.65     7.2  115.15
     8.7  116.65    10.2  118.15
#Mann= 3 , 0 , 0
   -11.2    .035       0       0    .035       0     5.7    .035       0
#XS Ineff= 2 , 0
               0  113.95     5.7          113.65
Permanent Ineff=
       F       F
Bank Sta=0,5.7
XS Rating Curve= 0
Exp/Cntr=.3,.1

Type RM Length L Ch R = 1 ,2       ,50,50,50
#Sta/Elev= 13
   -11.2  116.82    -9.2  115.82    -7.2  114.82    -5.2  113.82    -2.2  113.12
       0  112.52     5.7  110.92     8.7  110.92     9.4  111.92    10.4  112.92
    11.4  114.42    12.4  115.92    13.4  117.42
#Mann= 3 , 0 , 0
   -11.2    .035       0       0    .035       0    10.4    .035       0
#XS Ineff= 2 , 0
               0  112.52    10.4          112.92
Permanent Ineff=
       F       F
Bank Sta=0,10.4
XS Rating Curve= 0
Exp/Cntr=.3,.1

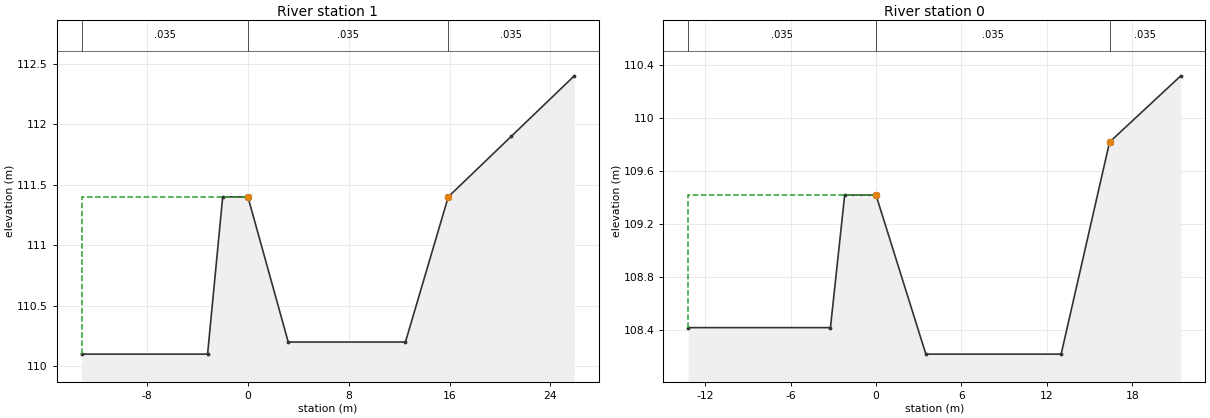
Type RM Length L Ch R = 1 ,1       ,50,50,50
#Sta/Elev= 9
   -13.2   110.1    -3.2   110.1      -2   111.4       0   111.4     3.2   110.2
    12.5   110.2    15.9   111.4    20.9   111.9    25.9   112.4
#Mann= 3 , 0 , 0
   -13.2    .035       0       0    .035       0    15.9    .035       0
#XS Ineff= 2 , 0
               0   111.4    15.9           111.4
Permanent Ineff=
       F       F
Bank Sta=0,15.9
XS Rating Curve= 0
Exp/Cntr=.3,.1

Type RM Length L Ch R = 1 ,0       ,0,0,0
#Sta/Elev= 8
   -13.2  108.42    -3.2  108.42    -2.2  109.42       0  109.42     3.5  108.22
      13  108.22    16.4  109.82    21.4  110.32
#Mann= 3 , 0 , 0
   -13.2    .035       0       0    .035       0    16.4    .035       0
#XS Ineff= 2 , 0
               0  109.42    16.4          109.82
Permanent Ineff=
       F       F
Bank Sta=0,16.4
XS Rating Curve= 0
Exp/Cntr=.3,.1

Chan Stop Cuts=-1