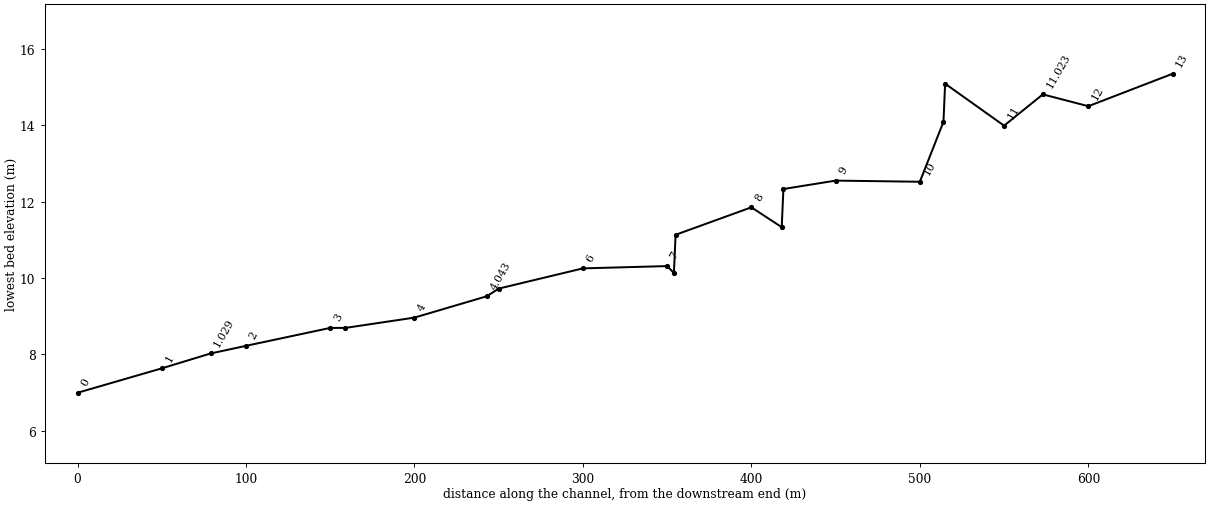
HEC-RAS study tonggol-ch.prj: tonggol-ch

--- tonggol-ch.g01 (geometry) --- (continued)

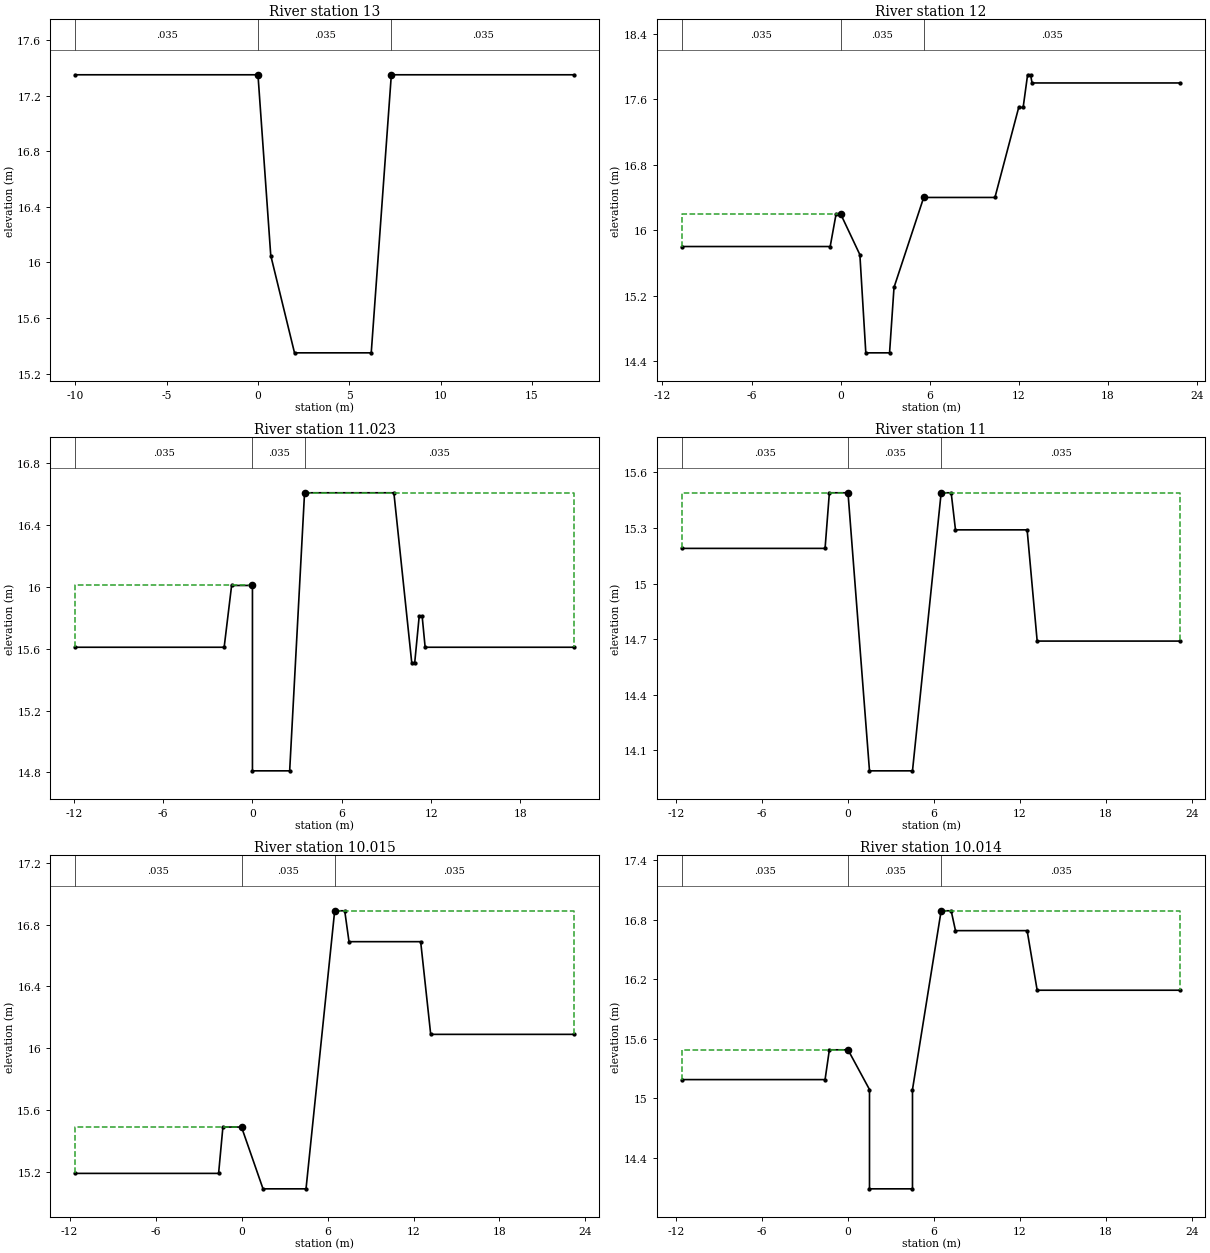
Type RM Length L Ch R = 1 ,13      ,50,50,50
#Sta/Elev= 7
     -10   17.35       0   17.35      .7   16.05       2   15.35     6.2   15.35
     7.3   17.35    17.3   17.35
#Mann= 3 , 0 , 0
     -10    .035       0       0    .035       0     7.3    .035       0
#XS Ineff= 2 , 0
               0   17.35     7.3           17.35
Permanent Ineff=
       F       F
Bank Sta=0,7.3
XS Rating Curve= 0
Exp/Cntr=.3,.1

Type RM Length L Ch R = 1 ,12      ,27,27,27
#Sta/Elev= 16
   -10.7    15.8     -.7    15.8     -.3    16.2       0    16.2     1.3    15.7
     1.7    14.5     3.3    14.5     3.6    15.3     5.6    16.4    10.4    16.4
      12    17.5    12.3    17.5    12.6    17.9    12.8    17.9    12.9    17.8
    22.9    17.8
#Mann= 3 , 0 , 0
   -10.7    .035       0       0    .035       0     5.6    .035       0
#XS Ineff= 2 , 0
               0    16.2     5.6            16.4
Permanent Ineff=
       F       F
Bank Sta=0,5.6
XS Rating Curve= 0
Exp/Cntr=.3,.1

Type RM Length L Ch R = 1 ,11.023  ,23,23,23
#Sta/Elev= 14
   -11.9   15.61    -1.9   15.61    -1.4   16.01       0   16.01       0   14.81
     2.5   14.81     3.5   16.61     9.5   16.61    10.7   15.51    10.9   15.51
    11.2   15.81    11.4   15.81    11.6   15.61    21.6   15.61
#Mann= 3 , 0 , 0
   -11.9    .035       0       0    .035       0     3.5    .035       0
#XS Ineff= 2 , 0
               0   16.01     3.5           16.61
Permanent Ineff=
       F       F
Bank Sta=0,3.5
XS Rating Curve= 0
Exp/Cntr=.3,.1

Type RM Length L Ch R = 1 ,11      ,35,35,35
#Sta/Elev= 12
   -11.6   15.19    -1.6   15.19    -1.3   15.49       0   15.49     1.5   13.99
     4.5   13.99     6.5   15.49     7.2   15.49     7.5   15.29    12.5   15.29
    13.2   14.69    23.2   14.69
#Mann= 3 , 0 , 0
   -11.6    .035       0       0    .035       0     6.5    .035       0
#XS Ineff= 2 , 0
               0   15.49     6.5           15.49
Permanent Ineff=
       F       F
Bank Sta=0,6.5
XS Rating Curve= 0
Exp/Cntr=.3,.1

Type RM Length L Ch R = 1 ,10.015  ,1,1,1
#Sta/Elev= 12
   -11.6   15.19    -1.6   15.19    -1.3   15.49       0   15.49     1.5   15.09
     4.5   15.09     6.5   16.89     7.2   16.89     7.5   16.69    12.5   16.69
    13.2   16.09    23.2   16.09
#Mann= 3 , 0 , 0
   -11.6    .035       0       0    .035       0     6.5    .035       0
#XS Ineff= 2 , 0
               0   15.49     6.5           16.89
Permanent Ineff=
       F       F
Bank Sta=0,6.5
XS Rating Curve= 0
Exp/Cntr=.3,.1

Type RM Length L Ch R = 1 ,10.014  ,14,14,14
#Sta/Elev= 14
   -11.6   15.19    -1.6   15.19    -1.3   15.49       0   15.49     1.5   15.09
     1.5   14.09     4.5   14.09     4.5   15.09     6.5   16.89     7.2   16.89
     7.5   16.69    12.5   16.69    13.2   16.09    23.2   16.09
#Mann= 3 , 0 , 0
   -11.6    .035       0       0    .035       0     6.5    .035       0
#XS Ineff= 2 , 0
               0   15.49     6.5           16.89
Permanent Ineff=
       F       F
Bank Sta=0,6.5
XS Rating Curve= 0
Exp/Cntr=.3,.1

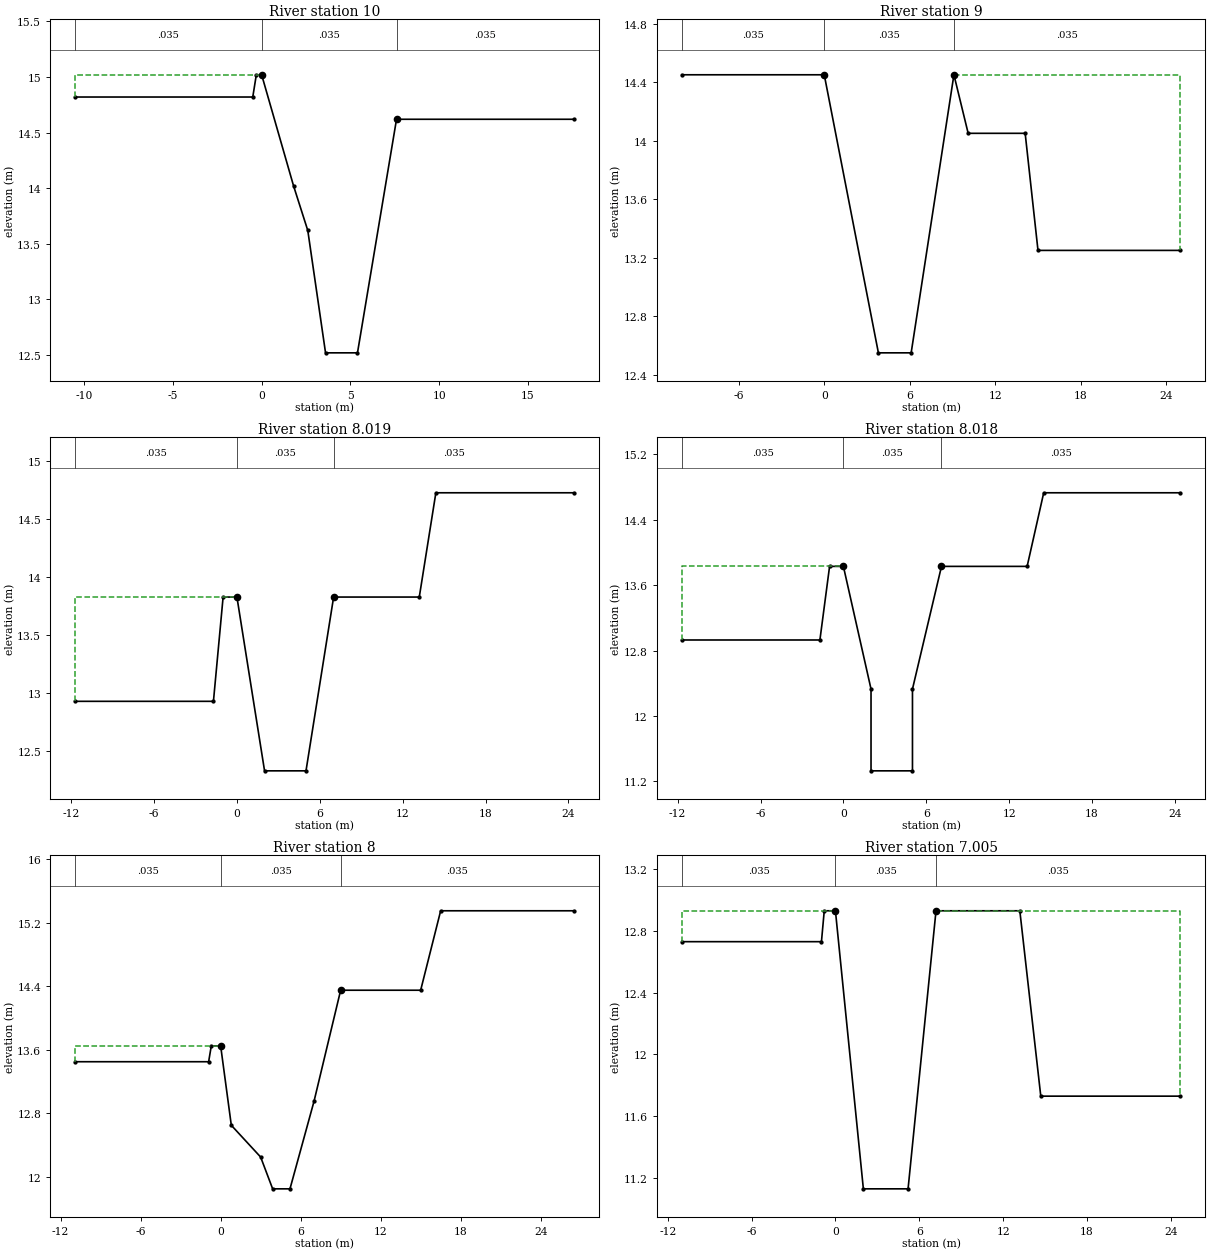
Type RM Length L Ch R = 1 ,10      ,50,50,50
#Sta/Elev= 10
   -10.5   14.82     -.5   14.82     -.3   15.02       0   15.02     1.8   14.02
     2.6   13.62     3.6   12.52     5.4   12.52     7.6   14.62    17.6   14.62
#Mann= 3 , 0 , 0
   -10.5    .035       0       0    .035       0     7.6    .035       0
#XS Ineff= 2 , 0
               0   15.02     7.6           14.62
Permanent Ineff=
       F       F
Bank Sta=0,7.6
XS Rating Curve= 0
Exp/Cntr=.3,.1

Type RM Length L Ch R = 1 ,9       ,31,31,31
#Sta/Elev= 9
     -10   14.45       0   14.45     3.8   12.55     6.1   12.55     9.1   14.45
    10.1   14.05    14.1   14.05      15   13.25      25   13.25
#Mann= 3 , 0 , 0
     -10    .035       0       0    .035       0     9.1    .035       0
#XS Ineff= 2 , 0
               0   14.45     9.1           14.45
Permanent Ineff=
       F       F
Bank Sta=0,9.1
XS Rating Curve= 0
Exp/Cntr=.3,.1

Type RM Length L Ch R = 1 ,8.019   ,1,1,1
#Sta/Elev= 10
   -11.7   12.93    -1.7   12.93      -1   13.83       0   13.83       2   12.33
       5   12.33       7   13.83    13.2   13.83    14.4   14.73    24.4   14.73
#Mann= 3 , 0 , 0
   -11.7    .035       0       0    .035       0       7    .035       0
#XS Ineff= 2 , 0
               0   13.83       7           13.83
Permanent Ineff=
       F       F
Bank Sta=0,7
XS Rating Curve= 0
Exp/Cntr=.3,.1

Type RM Length L Ch R = 1 ,8.018   ,18,18,18
#Sta/Elev= 12
   -11.7   12.93    -1.7   12.93      -1   13.83       0   13.83       2   12.33
       2   11.33       5   11.33       5   12.33     7.1   13.83    13.3   13.83
    14.5   14.73    24.4   14.73
#Mann= 3 , 0 , 0
   -11.7    .035       0       0    .035       0     7.1    .035       0
#XS Ineff= 2 , 0
               0   13.83     7.1           13.83
Permanent Ineff=
       F       F
Bank Sta=0,7.1
XS Rating Curve= 0
Exp/Cntr=.3,.1

Type RM Length L Ch R = 1 ,8       ,45,45,45
#Sta/Elev= 13
   -10.9   13.45     -.9   13.45     -.7   13.65       0   13.65      .8   12.65
       3   12.25     3.9   11.85     5.2   11.85       7   12.95       9   14.35
      15   14.35    16.5   15.35    26.5   15.35
#Mann= 3 , 0 , 0
   -10.9    .035       0       0    .035       0       9    .035       0
#XS Ineff= 2 , 0
               0   13.65       9           14.35
Permanent Ineff=
       F       F
Bank Sta=0,9
XS Rating Curve= 0
Exp/Cntr=.3,.1

Type RM Length L Ch R = 1 ,7.005   ,1,1,1
#Sta/Elev= 10
     -11   12.73      -1   12.73     -.8   12.93       0   12.93       2   11.13
     5.2   11.13     7.2   12.93    13.2   12.93    14.7   11.73    24.7   11.73
#Mann= 3 , 0 , 0
     -11    .035       0       0    .035       0     7.2    .035       0
#XS Ineff= 2 , 0
               0   12.93     7.2           12.93
Permanent Ineff=
       F       F
Bank Sta=0,7.2
XS Rating Curve= 0
Exp/Cntr=.3,.1

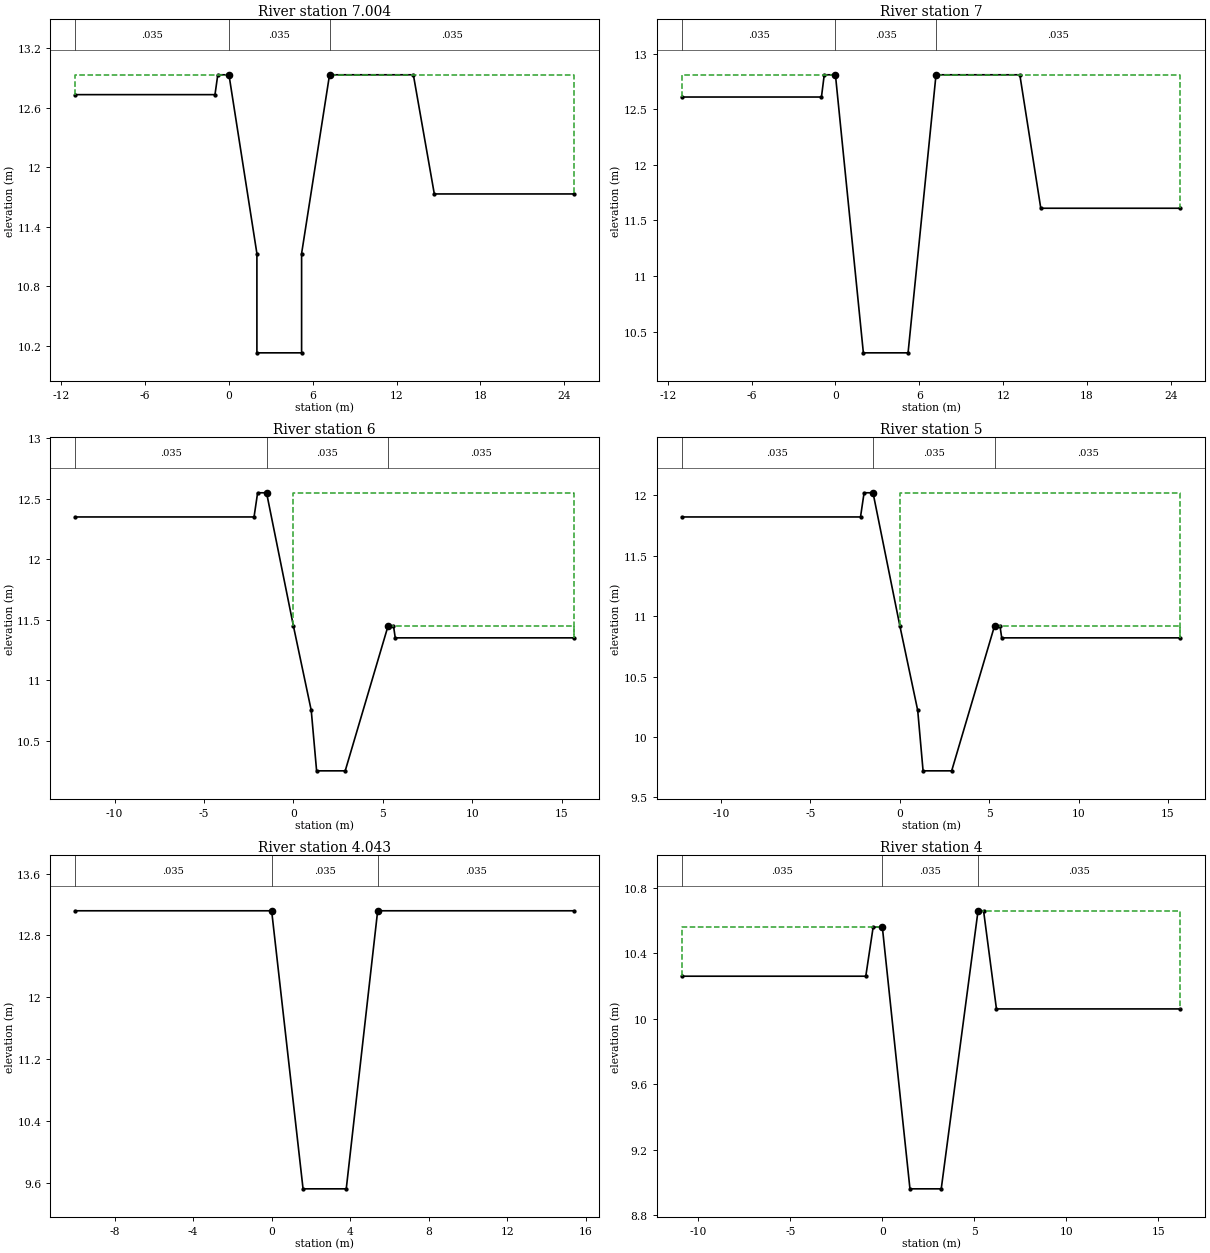
Type RM Length L Ch R = 1 ,7.004   ,4,4,4
#Sta/Elev= 12
     -11   12.73      -1   12.73     -.8   12.93       0   12.93       2   11.13
       2   10.13     5.2   10.13     5.2   11.13     7.2   12.93    13.2   12.93
    14.7   11.73    24.7   11.73
#Mann= 3 , 0 , 0
     -11    .035       0       0    .035       0     7.2    .035       0
#XS Ineff= 2 , 0
               0   12.93     7.2           12.93
Permanent Ineff=
       F       F
Bank Sta=0,7.2
XS Rating Curve= 0
Exp/Cntr=.3,.1

Type RM Length L Ch R = 1 ,7       ,50,50,50
#Sta/Elev= 10
     -11   12.61      -1   12.61     -.8   12.81       0   12.81       2   10.31
     5.2   10.31     7.2   12.81    13.2   12.81    14.7   11.61    24.7   11.61
#Mann= 3 , 0 , 0
     -11    .035       0       0    .035       0     7.2    .035       0
#XS Ineff= 2 , 0
               0   12.81     7.2           12.81
Permanent Ineff=
       F       F
Bank Sta=0,7.2
XS Rating Curve= 0
Exp/Cntr=.3,.1

Type RM Length L Ch R = 1 ,6       ,50,50,50
#Sta/Elev= 12
   -12.2   12.35    -2.2   12.35      -2   12.55    -1.5   12.55       0   11.45
       1   10.75     1.3   10.25     2.9   10.25     5.3   11.45     5.6   11.45
     5.7   11.35    15.7   11.35
#Mann= 3 , 0 , 0
   -12.2    .035       0    -1.5    .035       0     5.3    .035       0
#XS Ineff= 2 , 0
       0    -1.5   12.55     5.3       0   11.45
Permanent Ineff=
       F       F
Bank Sta=-1.5,5.3
XS Rating Curve= 0
Exp/Cntr=.3,.1

Type RM Length L Ch R = 1 ,5       ,7,7,7
#Sta/Elev= 12
   -12.2   11.82    -2.2   11.82      -2   12.02    -1.5   12.02       0   10.92
       1   10.22     1.3    9.72     2.9    9.72     5.3   10.92     5.6   10.92
     5.7   10.82    15.7   10.82
#Mann= 3 , 0 , 0
   -12.2    .035       0    -1.5    .035       0     5.3    .035       0
#XS Ineff= 2 , 0
       0    -1.5   12.02     5.3       0   10.92
Permanent Ineff=
       F       F
Bank Sta=-1.5,5.3
XS Rating Curve= 0
Exp/Cntr=.3,.1

Type RM Length L Ch R = 1 ,4.043   ,43,43,43
#Sta/Elev= 6
     -10   13.12       0   13.12     1.6    9.52     3.8    9.52     5.4   13.12
    15.4   13.12
#Mann= 3 , 0 , 0
     -10    .035       0       0    .035       0     5.4    .035       0
#XS Ineff= 2 , 0
               0   13.12     5.4           13.12
Permanent Ineff=
       F       F
Bank Sta=0,5.4
XS Rating Curve= 0
Exp/Cntr=.3,.1

Type RM Length L Ch R = 1 ,4       ,41,41,41
#Sta/Elev= 10
   -10.9   10.26     -.9   10.26     -.5   10.56       0   10.56     1.5    8.96
     3.2    8.96     5.2   10.66     5.5   10.66     6.2   10.06    16.2   10.06
#Mann= 3 , 0 , 0
   -10.9    .035       0       0    .035       0     5.2    .035       0
#XS Ineff= 2 , 0
               0   10.56     5.2           10.66
Permanent Ineff=
       F       F
Bank Sta=0,5.2
XS Rating Curve= 0
Exp/Cntr=.3,.1

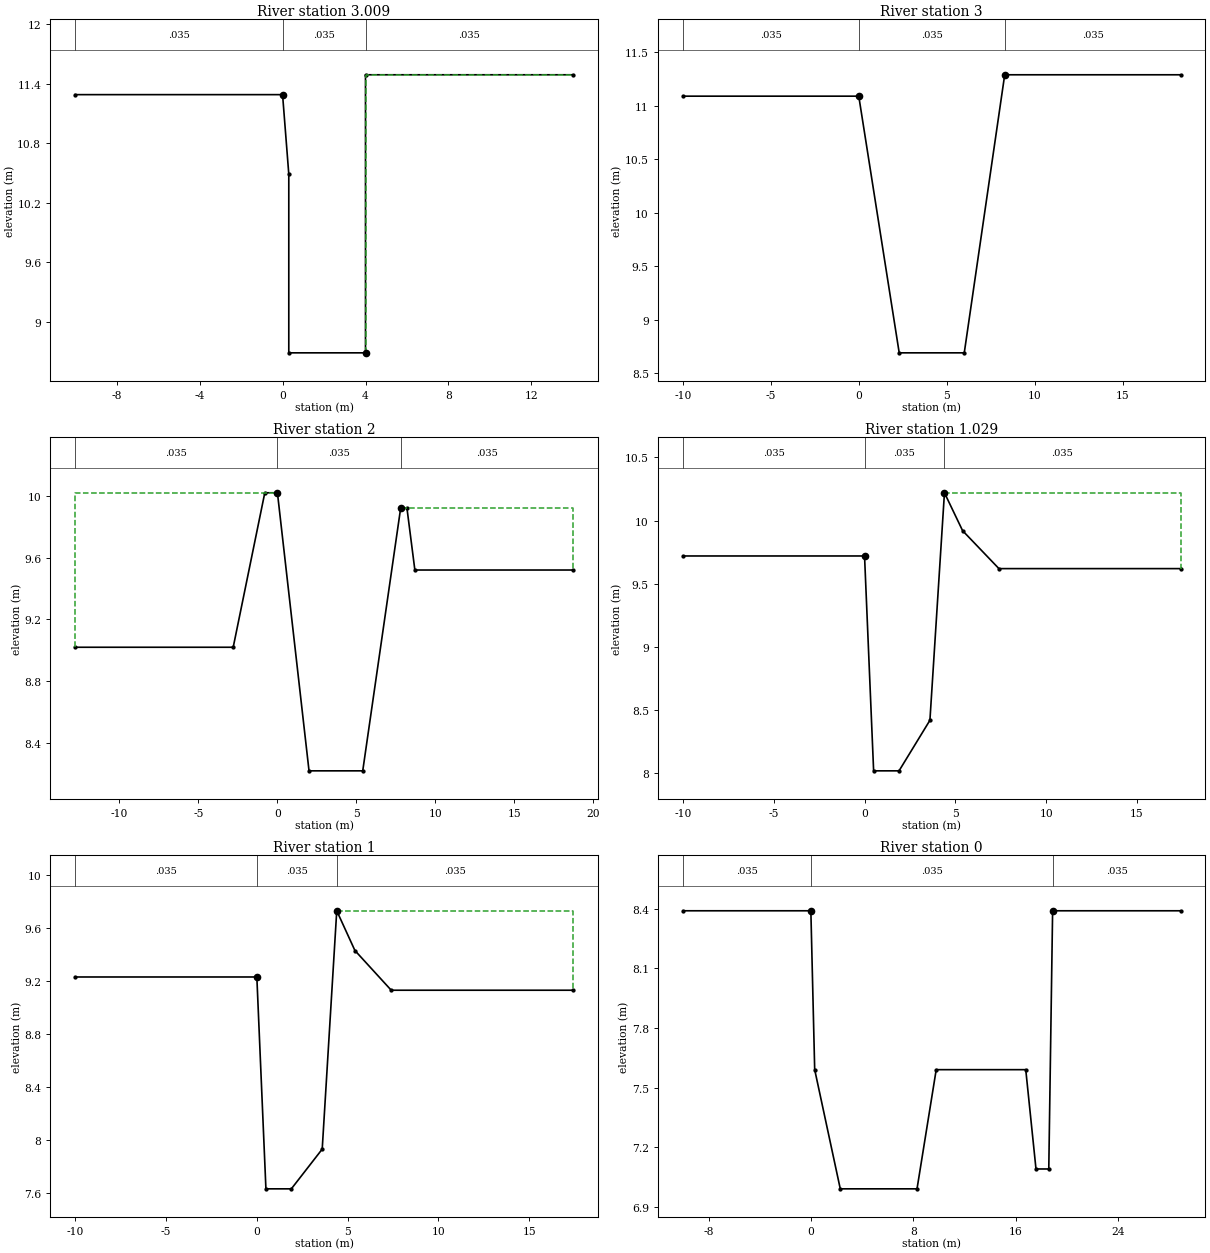
Type RM Length L Ch R = 1 ,3.009   ,9,9,9
#Sta/Elev= 7
     -10   11.29       0   11.29      .3   10.49      .3    8.69       4    8.69
       4   11.49      14   11.49
#Mann= 3 , 0 , 0
     -10    .035       0       0    .035       0       4    .035       0
#XS Ineff= 2 , 0
               0   11.29       4           11.49
Permanent Ineff=
       F       F
Bank Sta=0,4
XS Rating Curve= 0
Exp/Cntr=.3,.1

Type RM Length L Ch R = 1 ,3       ,50,50,50
#Sta/Elev= 6
     -10   11.09       0   11.09     2.3    8.69       6    8.69     8.3   11.29
    18.3   11.29
#Mann= 3 , 0 , 0
     -10    .035       0       0    .035       0     8.3    .035       0
#XS Ineff= 2 , 0
               0   11.09     8.3           11.29
Permanent Ineff=
       F       F
Bank Sta=0,8.3
XS Rating Curve= 0
Exp/Cntr=.3,.1

Type RM Length L Ch R = 1 ,2       ,21,21,21
#Sta/Elev= 10
   -12.8    9.02    -2.8    9.02     -.8   10.02       0   10.02       2    8.22
     5.4    8.22     7.8    9.92     8.2    9.92     8.7    9.52    18.7    9.52
#Mann= 3 , 0 , 0
   -12.8    .035       0       0    .035       0     7.8    .035       0
#XS Ineff= 2 , 0
               0   10.02     7.8            9.92
Permanent Ineff=
       F       F
Bank Sta=0,7.8
XS Rating Curve= 0
Exp/Cntr=.3,.1

Type RM Length L Ch R = 1 ,1.029   ,29,29,29
#Sta/Elev= 9
     -10    9.72       0    9.72      .5    8.02     1.9    8.02     3.6    8.42
     4.4   10.22     5.4    9.92     7.4    9.62    17.4    9.62
#Mann= 3 , 0 , 0
     -10    .035       0       0    .035       0     4.4    .035       0
#XS Ineff= 2 , 0
               0    9.72     4.4           10.22
Permanent Ineff=
       F       F
Bank Sta=0,4.4
XS Rating Curve= 0
Exp/Cntr=.3,.1

Type RM Length L Ch R = 1 ,1       ,50,50,50
#Sta/Elev= 9
     -10    9.23       0    9.23      .5    7.63     1.9    7.63     3.6    7.93
     4.4    9.73     5.4    9.43     7.4    9.13    17.4    9.13
#Mann= 3 , 0 , 0
     -10    .035       0       0    .035       0     4.4    .035       0
#XS Ineff= 2 , 0
               0    9.23     4.4            9.73
Permanent Ineff=
       F       F
Bank Sta=0,4.4
XS Rating Curve= 0
Exp/Cntr=.3,.1

Type RM Length L Ch R = 1 ,0       ,0,0,0
#Sta/Elev= 11
     -10    8.39       0    8.39      .3    7.59     2.3    6.99     8.3    6.99
     9.8    7.59    16.8    7.59    17.6    7.09    18.6    7.09    18.9    8.39
    28.9    8.39
#Mann= 3 , 0 , 0
     -10    .035       0       0    .035       0    18.9    .035       0
#XS Ineff= 2 , 0
       0       0    8.39    18.9       0    8.39
Permanent Ineff=
       F       F
Bank Sta=0,18.9
XS Rating Curve= 0
Exp/Cntr=.3,.1

Chan Stop Cuts=-1