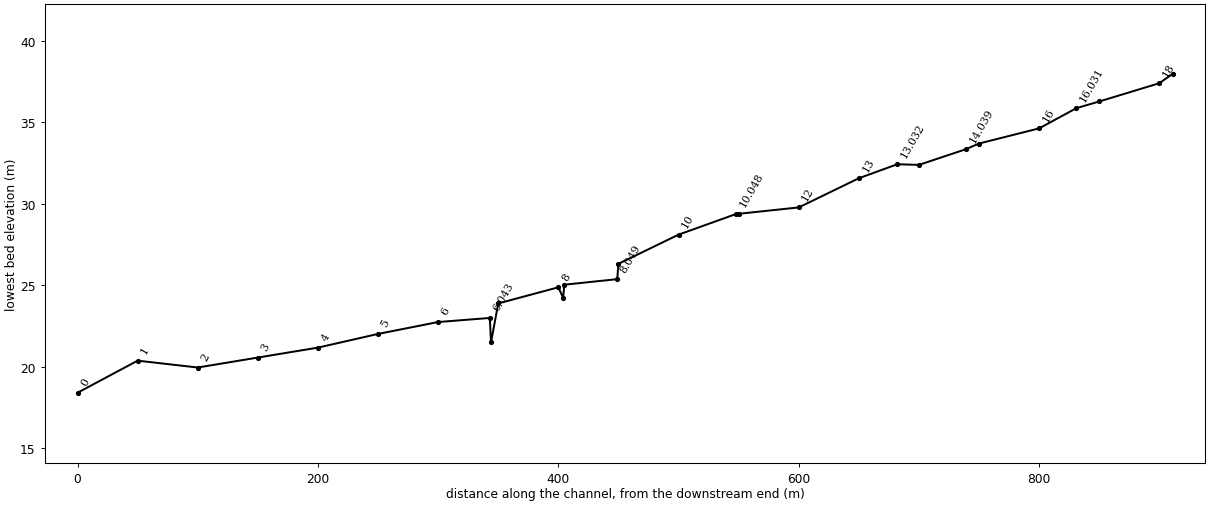
--- yahyun-ch.prj (project) ---

Proj Title=yahyun-ch
Current Plan=p01
Default Exp/Contr=.3,.1
SI Units
Geom File=g01
Flow File=f01
Plan File=p01
Y Axis Title=Elevation
X Axis Title(PF)=Main Channel Distance
X Axis Title(XS)=Station
BEGIN DESCRIPTION:
           BACK WATER COMPUTATION
      APPLICATION OF HEC-2 BY Samju Construction Engineering
      yahyun-ch: 10,20,30,50,80 yr
END DESCRIPTION:
DSS Export Rating Curves= 0
DSS Export Rating Curve Sorted= 0
DSS Export Volume Flow Curves= 0
DXF OffsetX= 0
DXF OffsetY= 0
DXF ScaleX= 1
DXF ScaleY= 10

--- yahyun-ch.p01 (plan) ---

Plan Title=Imported Plan 01
Version=Version 3.0.1  Mar 2001
Short Identifier=Imported Pla
Geom File=g01
Flow File=f01
Subcritical Flow
K Sum by GR= 0
Std Step Tol= 0.003
Critical Tol= 0.003
Num of Std Step Trials= 20
Max Error Tol= 0.1
Flow Tol Ratio= 0.001
Split Flow NTrial= 30
Split Flow Tol= 0.02
Split Flow Ratio= 0.02
Log Output Level= 0
Friction Slope Method= 1
Unsteady Friction Slope Method= 2
Parabolic Critical Depth
Global Vel Dist= 0 , 0 , 0
Global Log Level= 0
CheckData=True
Encroach Param=-1 ,0,0, 0
Computation Interval=1HOUR
Output Interval=1HOUR
Run HTab= 0
Run UNet= 0
Run PostProcess= 0
UNET Theta= 1
UNET ZTol= 0.02
UNET ZSATol= 0.1
UNET MxIter= 20
UNET MaxInSteps= 20
UNET DtIC= 0
UNET DtMin= 0
UNET MaxCRTS= 20
UNET WFStab= 2
UNET SFStab= 1
UNET WFX= 1
UNET SFX= 1
UNET Convert EG Bridges=-1
UNET Use Existing IB Tables=-1
Instantaneous Interval=1HOUR
Write IC File= 0
Write Velocity= 0
Write Detailed= 0

--- yahyun-ch.f01 (steady flow) ---

Flow Title=Imported Flow 01
Version=Version 3.0.1  Mar 2001
Number of Profiles= 5
Profile Names=PF 1,PF 2,PF 3,PF 4,PF 5
River Rch & RM=RIVER-1,Reach-1         ,18.011
     180     200     220     230     240
Boundary for River Rch & Prof#=RIVER-1,Reach-1         , 1
Up Type= 0
Dn Type= 3
Dn Slope=.0109
Boundary for River Rch & Prof#=RIVER-1,Reach-1         , 2
Up Type= 0
Dn Type= 3
Dn Slope=.0109
Boundary for River Rch & Prof#=RIVER-1,Reach-1         , 3
Up Type= 0
Dn Type= 3
Dn Slope=.0109
Boundary for River Rch & Prof#=RIVER-1,Reach-1         , 4
Up Type= 0
Dn Type= 3
Dn Slope=.0109
Boundary for River Rch & Prof#=RIVER-1,Reach-1         , 5
Up Type= 0
Dn Type= 3
Dn Slope=.0109
DSS Import GetInterval= 0
DSS Import GetPeak= 0
DSS Import FillOption= 0

--- yahyun-ch.g01 (geometry) ---

Geom Title=Imported Geom 01
Version=Version 3.0.1  Mar 2001

River Reach=RIVER-1         ,Reach-1
Reach XY= 2
              .5             .95              .5             .05

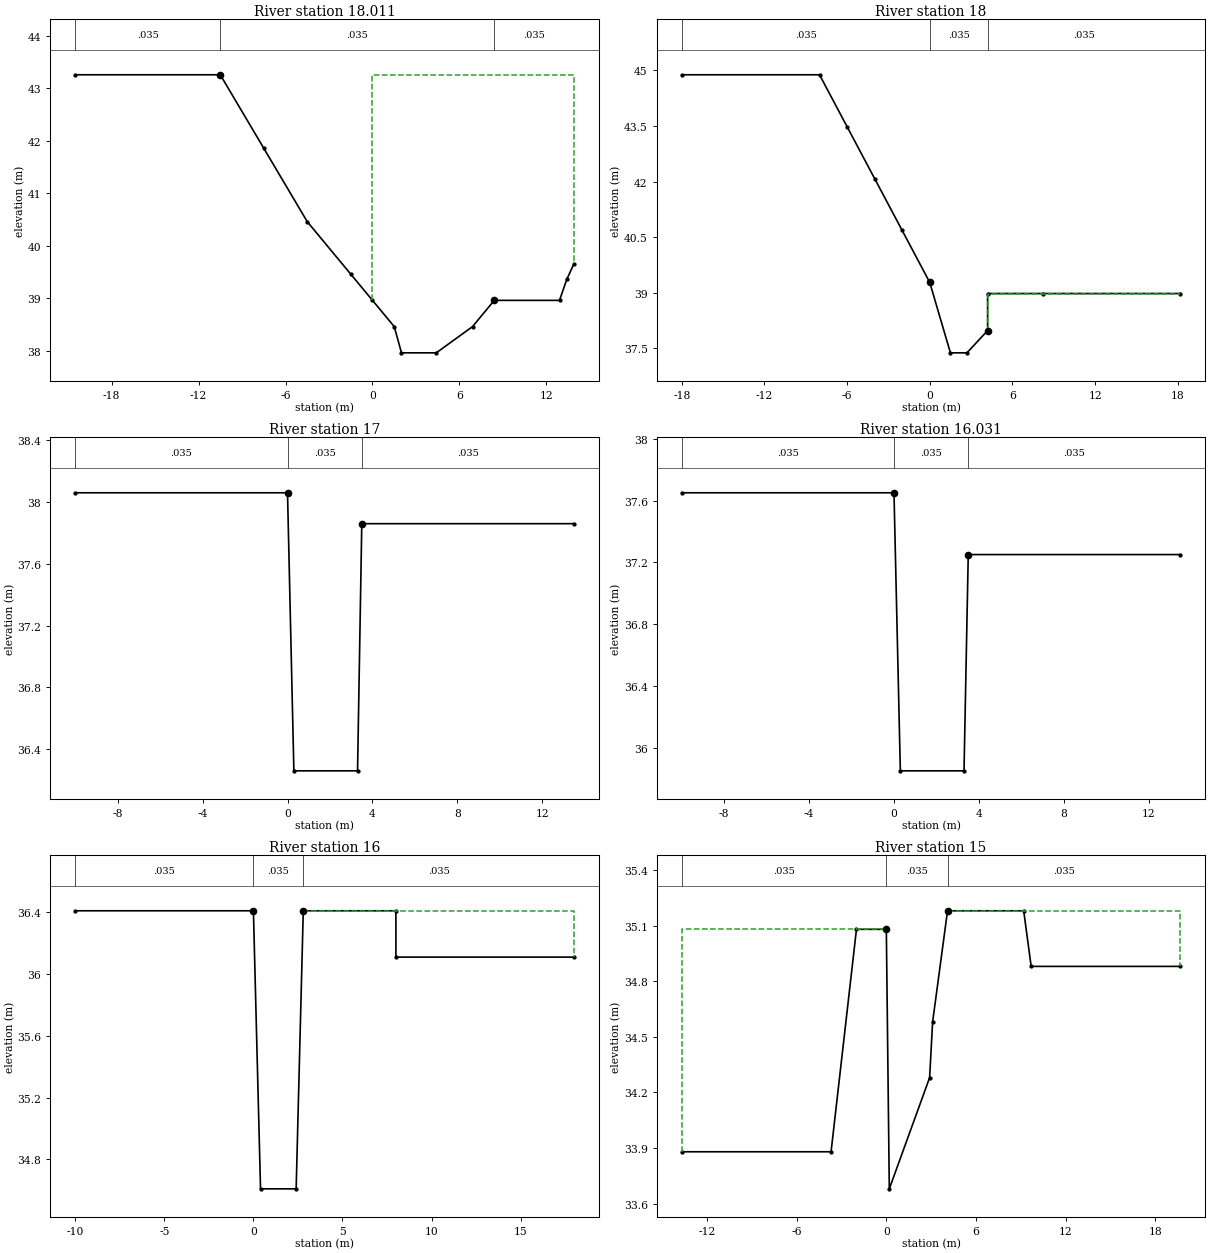
Type RM Length L Ch R = 1 ,18.011  ,11,11,11
#Sta/Elev= 14
   -20.5   43.26   -10.5   43.26    -7.5   41.86    -4.5   40.46    -1.5   39.46
       0   38.96     1.5   38.46       2   37.96     4.4   37.96     6.9   38.46
     8.4   38.96    12.9   38.96    13.4   39.36    13.9   39.66
#Mann= 3 , 0 , 0
   -20.5    .035       0   -10.5    .035       0     8.4    .035       0
#XS Ineff= 2 , 0
       0   -10.5   43.26     8.4       0   38.96
Permanent Ineff=
       F       F
Bank Sta=-10.5,8.4
XS Rating Curve= 0
Exp/Cntr=.3,.1

Type RM Length L Ch R = 1 ,18      ,50,50,50
#Sta/Elev= 12
     -18   44.88      -8   44.88      -6   43.48      -4   42.08      -2   40.68
       0   39.28     1.5   37.38     2.7   37.38     4.2   37.98     4.2   38.98
     8.2   38.98    18.2   38.98
#Mann= 3 , 0 , 0
     -18    .035       0       0    .035       0     4.2    .035       0
#XS Ineff= 2 , 0
               0   39.28     4.2           38.98
Permanent Ineff=
       F       F
Bank Sta=0,4.2
XS Rating Curve= 0
Exp/Cntr=.3,.1

Type RM Length L Ch R = 1 ,17      ,19,19,19
#Sta/Elev= 6
     -10   38.06       0   38.06      .3   36.26     3.3   36.26     3.5   37.86
    13.5   37.86
#Mann= 3 , 0 , 0
     -10    .035       0       0    .035       0     3.5    .035       0
#XS Ineff= 2 , 0
               0   38.06     3.5           37.86
Permanent Ineff=
       F       F
Bank Sta=0,3.5
XS Rating Curve= 0
Exp/Cntr=.3,.1

Type RM Length L Ch R = 1 ,16.031  ,31,31,31
#Sta/Elev= 6
     -10   37.65       0   37.65      .3   35.85     3.3   35.85     3.5   37.25
    13.5   37.25
#Mann= 3 , 0 , 0
     -10    .035       0       0    .035       0     3.5    .035       0
#XS Ineff= 2 , 0
               0   37.65     3.5           37.25
Permanent Ineff=
       F       F
Bank Sta=0,3.5
XS Rating Curve= 0
Exp/Cntr=.3,.1

Type RM Length L Ch R = 1 ,16      ,50,50,50
#Sta/Elev= 8
     -10   36.41       0   36.41      .4   34.61     2.4   34.61     2.8   36.41
       8   36.41       8   36.11      18   36.11
#Mann= 3 , 0 , 0
     -10    .035       0       0    .035       0     2.8    .035       0
#XS Ineff= 2 , 0
               0   36.41     2.8           36.41
Permanent Ineff=
       F       F
Bank Sta=0,2.8
XS Rating Curve= 0
Exp/Cntr=.3,.1

Type RM Length L Ch R = 1 ,15      ,11,11,11
#Sta/Elev= 11
   -13.7   33.88    -3.7   33.88      -2   35.08       0   35.08      .2   33.68
     2.9   34.28     3.1   34.58     4.1   35.18     9.2   35.18     9.7   34.88
    19.7   34.88
#Mann= 3 , 0 , 0
   -13.7    .035       0       0    .035       0     4.1    .035       0
#XS Ineff= 2 , 0
               0   35.08     4.1           35.18
Permanent Ineff=
       F       F
Bank Sta=0,4.1
XS Rating Curve= 0
Exp/Cntr=.3,.1

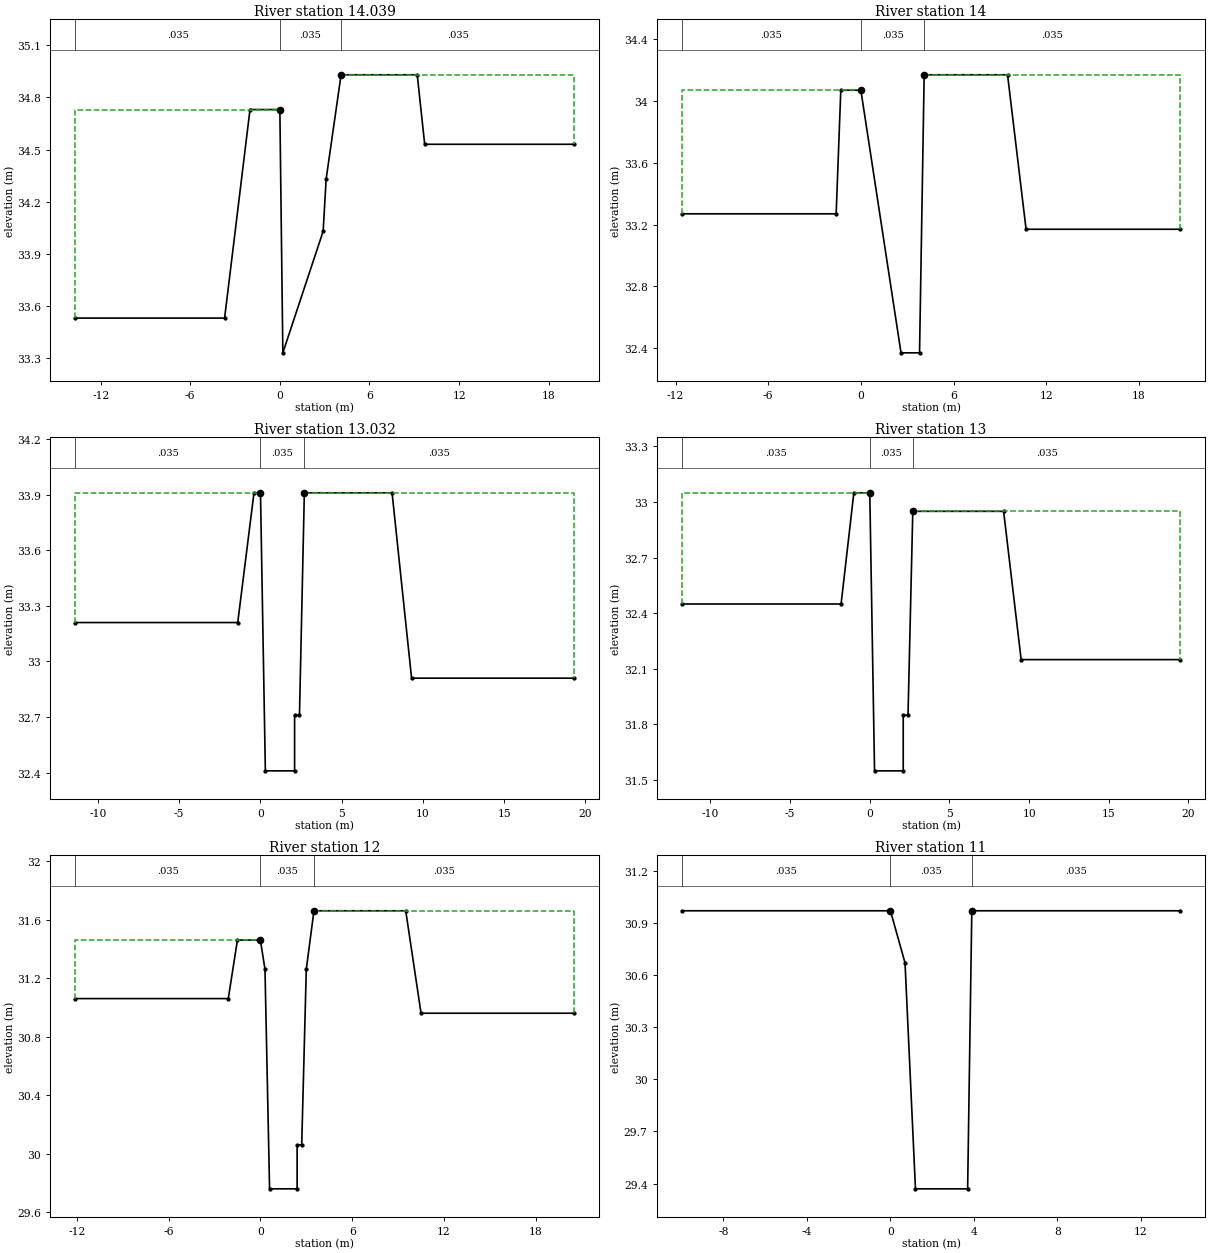
Type RM Length L Ch R = 1 ,14.039  ,39,39,39
#Sta/Elev= 11
   -13.7   33.53    -3.7   33.53      -2   34.73       0   34.73      .2   33.33
     2.9   34.03     3.1   34.33     4.1   34.93     9.2   34.93     9.7   34.53
    19.7   34.53
#Mann= 3 , 0 , 0
   -13.7    .035       0       0    .035       0     4.1    .035       0
#XS Ineff= 2 , 0
               0   34.73     4.1           34.93
Permanent Ineff=
       F       F
Bank Sta=0,4.1
XS Rating Curve= 0
Exp/Cntr=.3,.1

Type RM Length L Ch R = 1 ,14      ,18,18,18
#Sta/Elev= 10
   -11.6   33.27    -1.6   33.27    -1.3   34.07       0   34.07     2.6   32.37
     3.8   32.37     4.1   34.17     9.5   34.17    10.7   33.17    20.7   33.17
#Mann= 3 , 0 , 0
   -11.6    .035       0       0    .035       0     4.1    .035       0
#XS Ineff= 2 , 0
               0   34.07     4.1           34.17
Permanent Ineff=
       F       F
Bank Sta=0,4.1
XS Rating Curve= 0
Exp/Cntr=.3,.1

Type RM Length L Ch R = 1 ,13.032  ,32,32,32
#Sta/Elev= 12
   -11.4   33.21    -1.4   33.21     -.4   33.91       0   33.91      .3   32.41
     2.1   32.41     2.1   32.71     2.4   32.71     2.7   33.91     8.1   33.91
     9.3   32.91    19.3   32.91
#Mann= 3 , 0 , 0
   -11.4    .035       0       0    .035       0     2.7    .035       0
#XS Ineff= 2 , 0
               0   33.91     2.7           33.91
Permanent Ineff=
       F       F
Bank Sta=0,2.7
XS Rating Curve= 0
Exp/Cntr=.3,.1

Type RM Length L Ch R = 1 ,13      ,50,50,50
#Sta/Elev= 12
   -11.8   32.45    -1.8   32.45      -1   33.05       0   33.05      .3   31.55
     2.1   31.55     2.1   31.85     2.4   31.85     2.7   32.95     8.4   32.95
     9.5   32.15    19.5   32.15
#Mann= 3 , 0 , 0
   -11.8    .035       0       0    .035       0     2.7    .035       0
#XS Ineff= 2 , 0
               0   33.05     2.7           32.95
Permanent Ineff=
       F       F
Bank Sta=0,2.7
XS Rating Curve= 0
Exp/Cntr=.3,.1

Type RM Length L Ch R = 1 ,12      ,50,50,50
#Sta/Elev= 14
   -12.1   31.06    -2.1   31.06    -1.5   31.46       0   31.46      .3   31.26
      .6   29.76     2.4   29.76     2.4   30.06     2.7   30.06       3   31.26
     3.5   31.66     9.5   31.66    10.5   30.96    20.5   30.96
#Mann= 3 , 0 , 0
   -12.1    .035       0       0    .035       0     3.5    .035       0
#XS Ineff= 2 , 0
               0   31.46     3.5           31.66
Permanent Ineff=
       F       F
Bank Sta=0,3.5
XS Rating Curve= 0
Exp/Cntr=.3,.1

Type RM Length L Ch R = 1 ,11      ,2,2,2
#Sta/Elev= 7
     -10   30.97       0   30.97      .7   30.67     1.2   29.37     3.7   29.37
     3.9   30.97    13.9   30.97
#Mann= 3 , 0 , 0
     -10    .035       0       0    .035       0     3.9    .035       0
#XS Ineff= 2 , 0
               0   30.97     3.9           30.97
Permanent Ineff=
       F       F
Bank Sta=0,3.9
XS Rating Curve= 0
Exp/Cntr=.3,.1

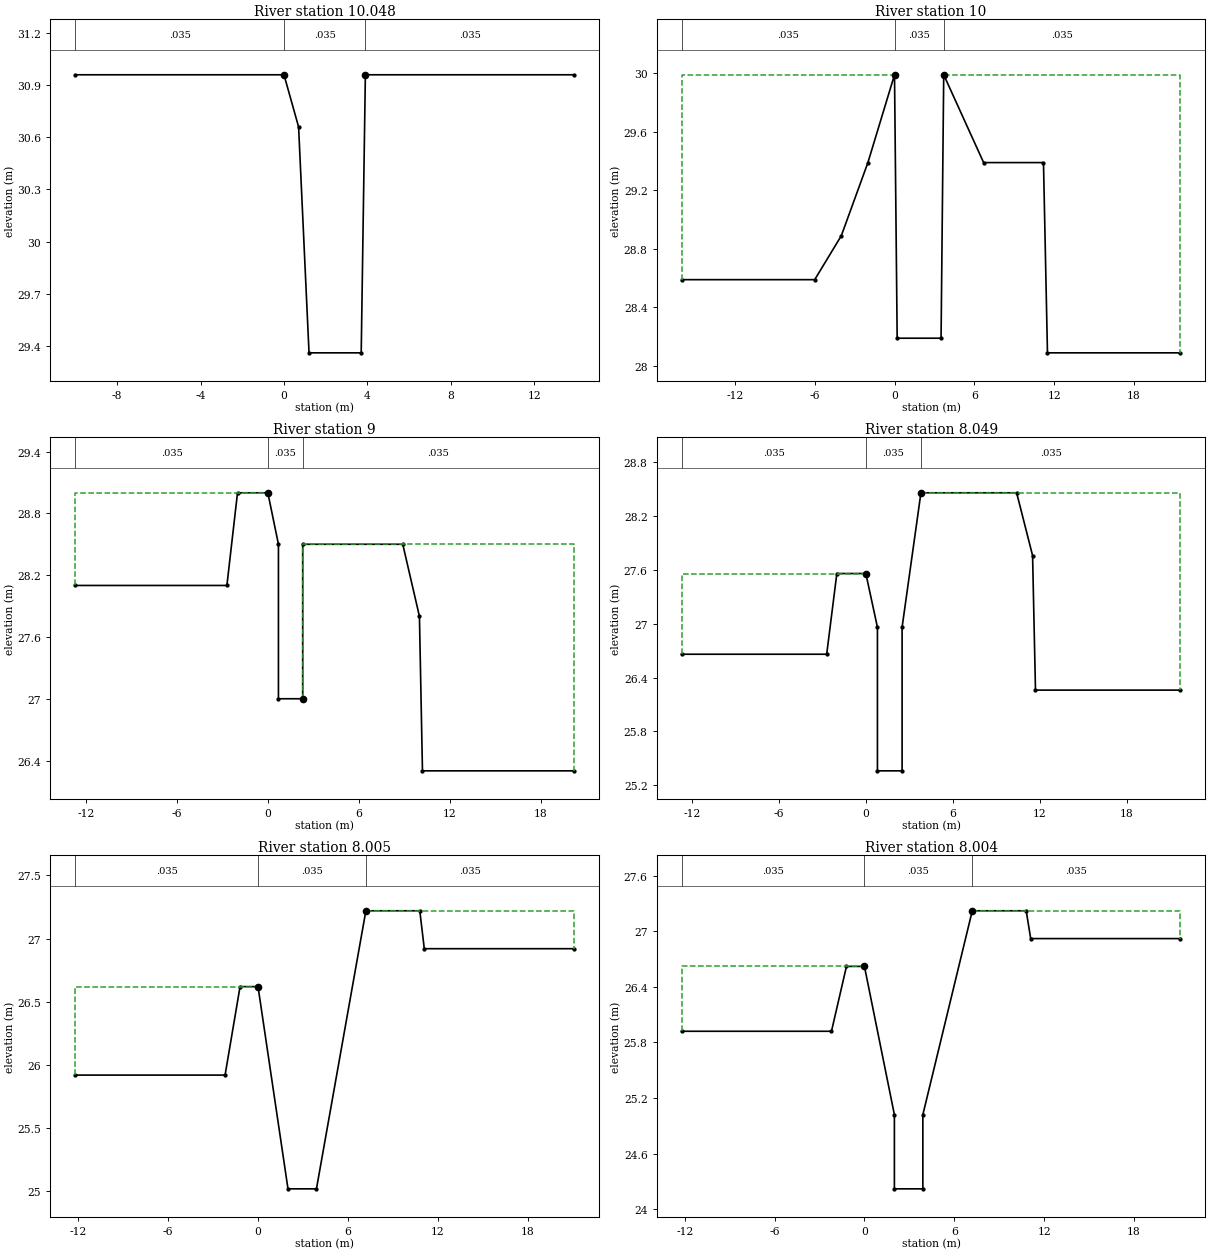
Type RM Length L Ch R = 1 ,10.048  ,48,48,48
#Sta/Elev= 7
     -10   30.96       0   30.96      .7   30.66     1.2   29.36     3.7   29.36
     3.9   30.96    13.9   30.96
#Mann= 3 , 0 , 0
     -10    .035       0       0    .035       0     3.9    .035       0
#XS Ineff= 2 , 0
               0   30.96     3.9           30.96
Permanent Ineff=
       F       F
Bank Sta=0,3.9
XS Rating Curve= 0
Exp/Cntr=.3,.1

Type RM Length L Ch R = 1 ,10      ,50,50,50
#Sta/Elev= 12
     -16   28.59      -6   28.59      -4   28.89      -2   29.39       0   29.99
      .2   28.19     3.5   28.19     3.7   29.99     6.7   29.39    11.2   29.39
    11.5   28.09    21.5   28.09
#Mann= 3 , 0 , 0
     -16    .035       0       0    .035       0     3.7    .035       0
#XS Ineff= 2 , 0
               0   29.99     3.7           29.99
Permanent Ineff=
       F       F
Bank Sta=0,3.7
XS Rating Curve= 0
Exp/Cntr=.3,.1

Type RM Length L Ch R = 1 ,9       ,1,1,1
#Sta/Elev= 12
   -12.7    28.1    -2.7    28.1      -2      29       0      29      .7    28.5
      .7      27     2.3      27     2.3    28.5     8.9    28.5      10    27.8
    10.2    26.3    20.2    26.3
#Mann= 3 , 0 , 0
   -12.7    .035       0       0    .035       0     2.3    .035       0
#XS Ineff= 2 , 0
               0      29     2.3            28.5
Permanent Ineff=
       F       F
Bank Sta=0,2.3
XS Rating Curve= 0
Exp/Cntr=.3,.1

Type RM Length L Ch R = 1 ,8.049   ,44,44,44
#Sta/Elev= 13
   -12.7   26.66    -2.7   26.66      -2   27.56       0   27.56      .8   26.96
      .8   25.36     2.5   25.36     2.5   26.96     3.8   28.46    10.4   28.46
    11.5   27.76    11.7   26.26    21.7   26.26
#Mann= 3 , 0 , 0
   -12.7    .035       0       0    .035       0     3.8    .035       0
#XS Ineff= 2 , 0
               0   27.56     3.8           28.46
Permanent Ineff=
       F       F
Bank Sta=0,3.8
XS Rating Curve= 0
Exp/Cntr=.3,.1

Type RM Length L Ch R = 1 ,8.005   ,1,1,1
#Sta/Elev= 10
   -12.2   25.92    -2.2   25.92    -1.2   26.62       0   26.62       2   25.02
     3.9   25.02     7.2   27.22    10.8   27.22    11.1   26.92    21.1   26.92
#Mann= 3 , 0 , 0
   -12.2    .035       0       0    .035       0     7.2    .035       0
#XS Ineff= 2 , 0
               0   26.62     7.2           27.22
Permanent Ineff=
       F       F
Bank Sta=0,7.2
XS Rating Curve= 0
Exp/Cntr=.3,.1

Type RM Length L Ch R = 1 ,8.004   ,4,4,4
#Sta/Elev= 13
   -12.2   25.92    -2.2   25.92    -1.2   26.62       0   26.62       0   26.62
       2   25.02       2   24.22     3.9   24.22     3.9   25.02     7.2   27.22
    10.8   27.22    11.1   26.92    21.1   26.92
#Mann= 3 , 0 , 0
   -12.2    .035       0       0    .035       0     7.2    .035       0
#XS Ineff= 2 , 0
               0   26.62     7.2           27.22
Permanent Ineff=
       F       F
Bank Sta=0,7.2
XS Rating Curve= 0
Exp/Cntr=.3,.1

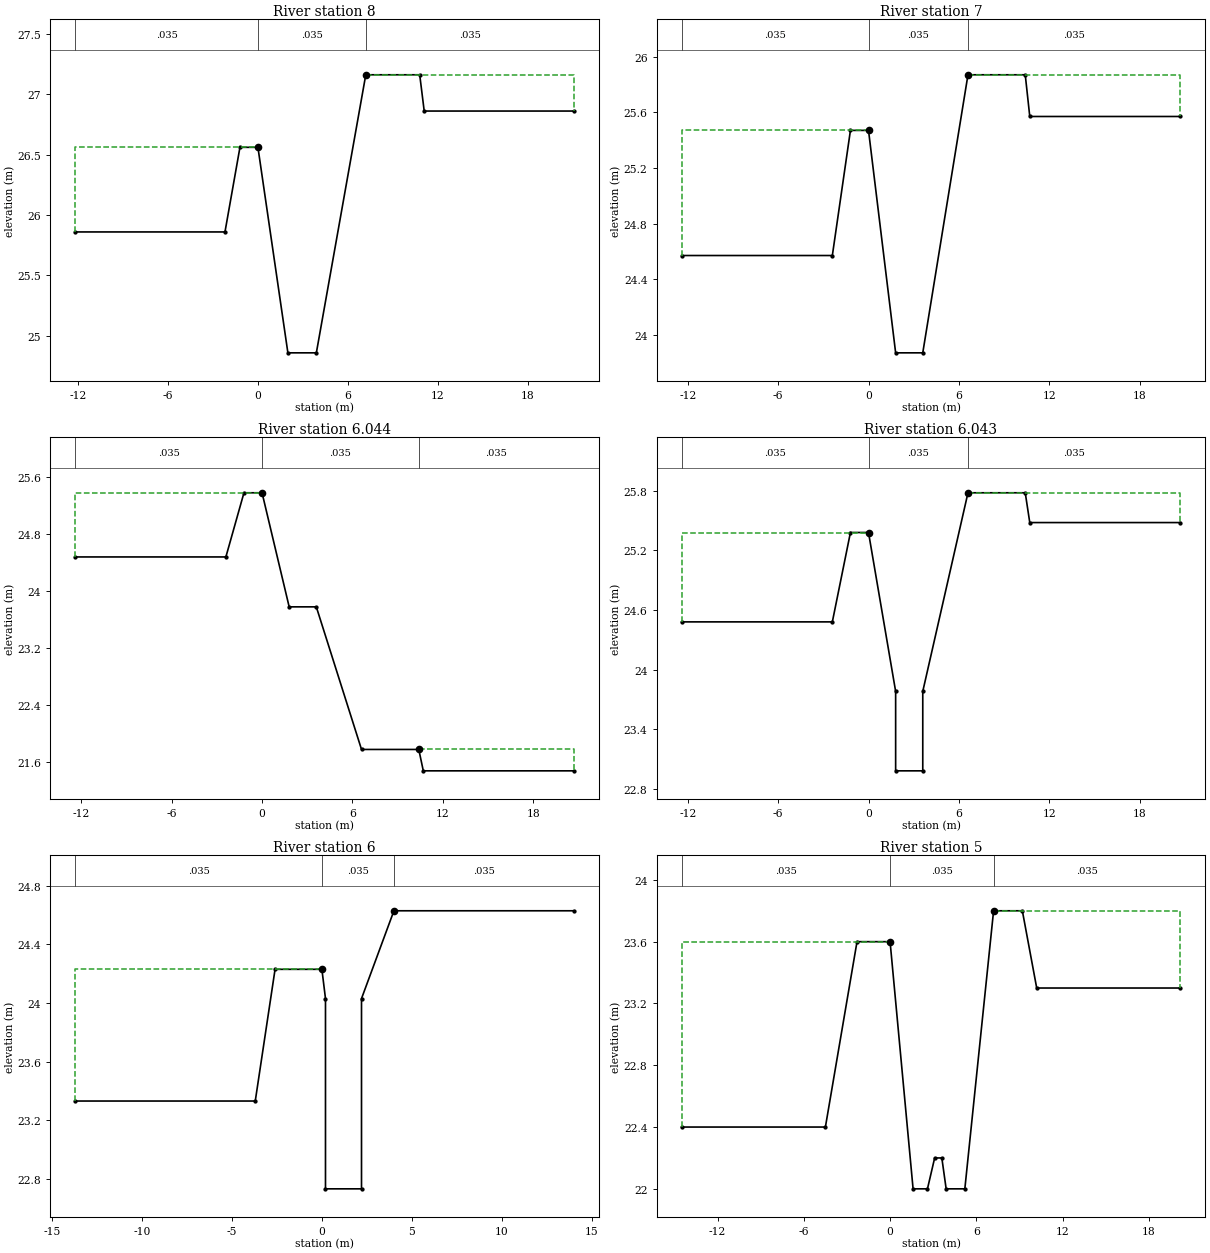
Type RM Length L Ch R = 1 ,8       ,50,50,50
#Sta/Elev= 11
   -12.2   25.86    -2.2   25.86    -1.2   26.56       0   26.56       0   26.56
       2   24.86     3.9   24.86     7.2   27.16    10.8   27.16    11.1   26.86
    21.1   26.86
#Mann= 3 , 0 , 0
   -12.2    .035       0       0    .035       0     7.2    .035       0
#XS Ineff= 2 , 0
               0   26.56     7.2           27.16
Permanent Ineff=
       F       F
Bank Sta=0,7.2
XS Rating Curve= 0
Exp/Cntr=.3,.1

Type RM Length L Ch R = 1 ,7       ,6,6,6
#Sta/Elev= 10
   -12.4   24.57    -2.4   24.57    -1.2   25.47       0   25.47     1.8   23.87
     3.6   23.87     6.6   25.87    10.4   25.87    10.7   25.57    20.7   25.57
#Mann= 3 , 0 , 0
   -12.4    .035       0       0    .035       0     6.6    .035       0
#XS Ineff= 2 , 0
               0   25.47     6.6           25.87
Permanent Ineff=
       F       F
Bank Sta=0,6.6
XS Rating Curve= 0
Exp/Cntr=.3,.1

Type RM Length L Ch R = 1 ,6.044   ,1,1,1
#Sta/Elev= 10
   -12.4   24.48    -2.4   24.48    -1.2   25.38       0   25.38     1.8   23.78
     3.6   23.78     6.6   21.78    10.4   21.78    10.7   21.48    20.7   21.48
#Mann= 3 , 0 , 0
   -12.4    .035       0       0    .035       0    10.4    .035       0
#XS Ineff= 2 , 0
               0   25.38    10.4           21.78
Permanent Ineff=
       F       F
Bank Sta=0,10.4
XS Rating Curve= 0
Exp/Cntr=.3,.1

Type RM Length L Ch R = 1 ,6.043   ,43,43,43
#Sta/Elev= 12
   -12.4   24.48    -2.4   24.48    -1.2   25.38       0   25.38     1.8   23.78
     1.8   22.98     3.6   22.98     3.6   23.78     6.6   25.78    10.4   25.78
    10.7   25.48    20.7   25.48
#Mann= 3 , 0 , 0
   -12.4    .035       0       0    .035       0     6.6    .035       0
#XS Ineff= 2 , 0
               0   25.38     6.6           25.78
Permanent Ineff=
       F       F
Bank Sta=0,6.6
XS Rating Curve= 0
Exp/Cntr=.3,.1

Type RM Length L Ch R = 1 ,6       ,50,50,50
#Sta/Elev= 10
   -13.7   23.33    -3.7   23.33    -2.6   24.23       0   24.23      .2   24.03
      .2   22.73     2.2   22.73     2.2   24.03       4   24.63      14   24.63
#Mann= 3 , 0 , 0
   -13.7    .035       0       0    .035       0       4    .035       0
#XS Ineff= 2 , 0
               0   24.23       4           24.63
Permanent Ineff=
       F       F
Bank Sta=0,4
XS Rating Curve= 0
Exp/Cntr=.3,.1

Type RM Length L Ch R = 1 ,5       ,50,50,50
#Sta/Elev= 14
   -14.5    22.4    -4.5    22.4    -2.3    23.6       0    23.6     1.6      22
     2.6      22     3.1    22.2     3.6    22.2     3.9      22     5.2      22
     7.2    23.8     9.2    23.8    10.2    23.3    20.2    23.3
#Mann= 3 , 0 , 0
   -14.5    .035       0       0    .035       0     7.2    .035       0
#XS Ineff= 2 , 0
               0    23.6     7.2            23.8
Permanent Ineff=
       F       F
Bank Sta=0,7.2
XS Rating Curve= 0
Exp/Cntr=.3,.1

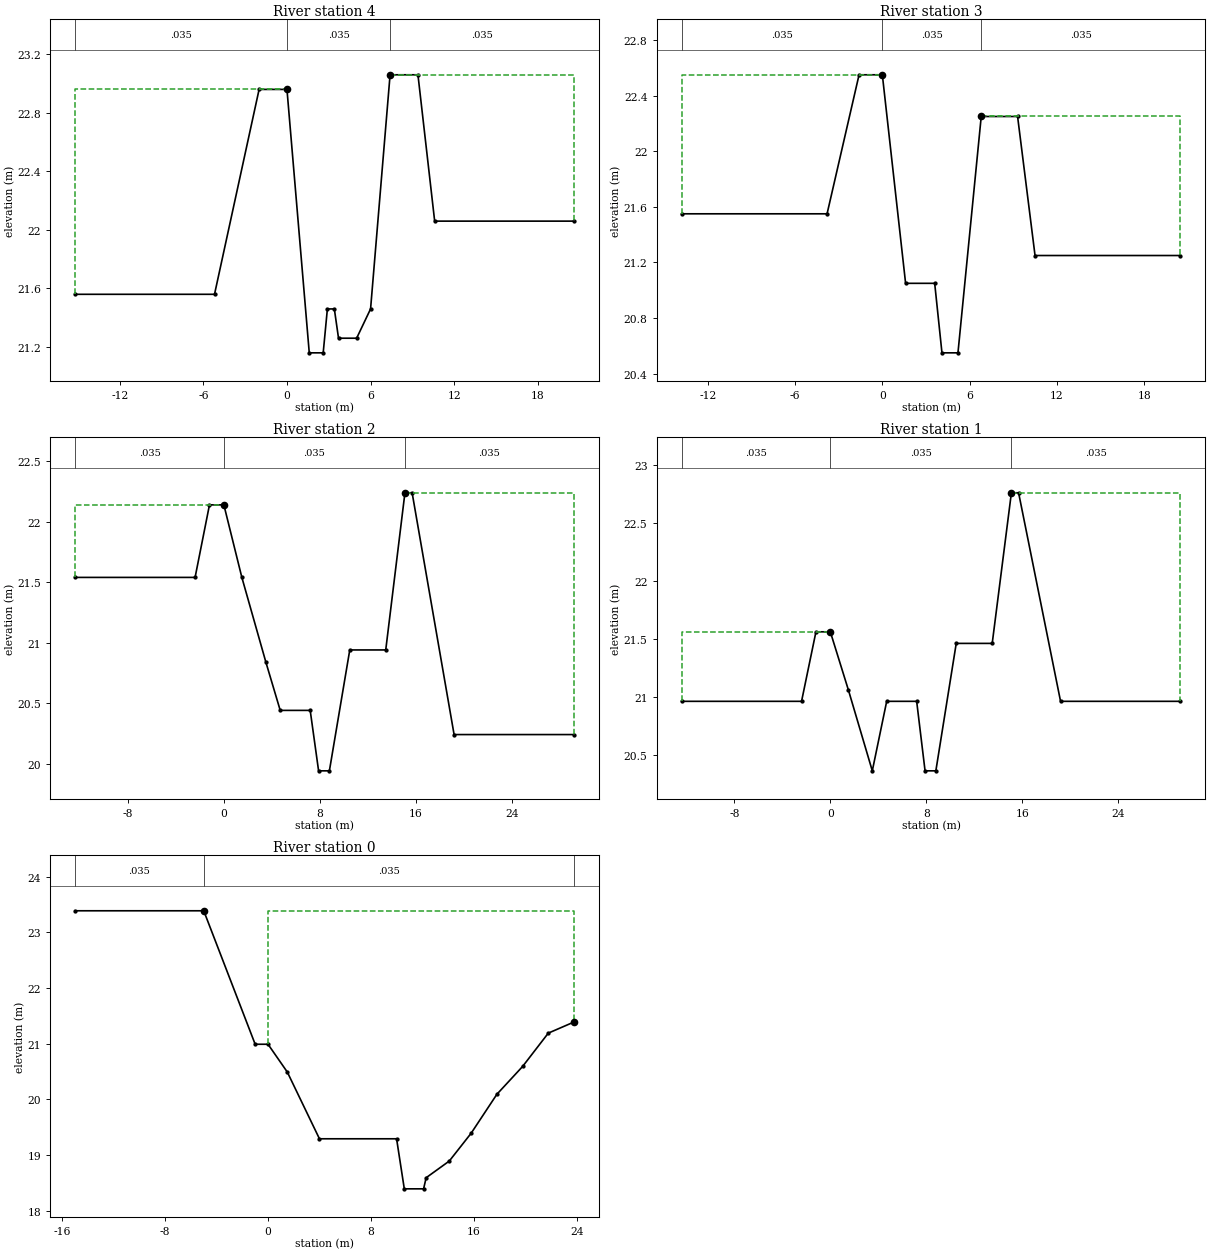
Type RM Length L Ch R = 1 ,4       ,50,50,50
#Sta/Elev= 15
   -15.2   21.56    -5.2   21.56      -2   22.96       0   22.96     1.6   21.16
     2.6   21.16     2.9   21.46     3.4   21.46     3.7   21.26       5   21.26
       6   21.46     7.4   23.06     9.4   23.06    10.6   22.06    20.6   22.06
#Mann= 3 , 0 , 0
   -15.2    .035       0       0    .035       0     7.4    .035       0
#XS Ineff= 2 , 0
               0   22.96     7.4           23.06
Permanent Ineff=
       F       F
Bank Sta=0,7.4
XS Rating Curve= 0
Exp/Cntr=.3,.1

Type RM Length L Ch R = 1 ,3       ,50,50,50
#Sta/Elev= 12
   -13.8   21.55    -3.8   21.55    -1.6   22.55       0   22.55     1.6   21.05
     3.6   21.05     4.1   20.55     5.2   20.55     6.8   22.25     9.3   22.25
    10.5   21.25    20.5   21.25
#Mann= 3 , 0 , 0
   -13.8    .035       0       0    .035       0     6.8    .035       0
#XS Ineff= 2 , 0
               0   22.55     6.8           22.25
Permanent Ineff=
       F       F
Bank Sta=0,6.8
XS Rating Curve= 0
Exp/Cntr=.3,.1

Type RM Length L Ch R = 1 ,2       ,50,50,50
#Sta/Elev= 16
   -12.4   21.54    -2.4   21.54    -1.2   22.14       0   22.14     1.5   21.54
     3.5   20.84     4.7   20.44     7.2   20.44     7.9   19.94     8.8   19.94
    10.5   20.94    13.5   20.94    15.1   22.24    15.7   22.24    19.2   20.24
    29.2   20.24
#Mann= 3 , 0 , 0
   -12.4    .035       0       0    .035       0    15.1    .035       0
#XS Ineff= 2 , 0
               0   22.14    15.1           22.24
Permanent Ineff=
       F       F
Bank Sta=0,15.1
XS Rating Curve= 0
Exp/Cntr=.3,.1

Type RM Length L Ch R = 1 ,1       ,50,50,50
#Sta/Elev= 16
   -12.4   20.96    -2.4   20.96    -1.2   21.56       0   21.56     1.5   21.06
     3.5   20.36     4.7   20.96     7.2   20.96     7.9   20.36     8.8   20.36
    10.5   21.46    13.5   21.46    15.1   22.76    15.7   22.76    19.2   20.96
    29.2   20.96
#Mann= 3 , 0 , 0
   -12.4    .035       0       0    .035       0    15.1    .035       0
#XS Ineff= 2 , 0
               0   21.56    15.1           22.76
Permanent Ineff=
       F       F
Bank Sta=0,15.1
XS Rating Curve= 0
Exp/Cntr=.3,.1

Type RM Length L Ch R = 1 ,0       ,0,0,0
#Sta/Elev= 16
     -15   23.39      -5   23.39      -1   20.99       0   20.99     1.5   20.49
       4   19.29      10   19.29    10.6   18.39    12.1   18.39    12.3   18.59
    14.1   18.89    15.8   19.39    17.8   20.09    19.8   20.59    21.8   21.19
    23.8   21.39
#Mann= 3 , 0 , 0
     -15    .035       0      -5    .035       0    23.8    .035       0
#XS Ineff= 2 , 0
       0      -5   23.39    23.8       0   21.39
Permanent Ineff=
       F       F
Bank Sta=-5,23.8
XS Rating Curve= 0
Exp/Cntr=.3,.1

Chan Stop Cuts=-1