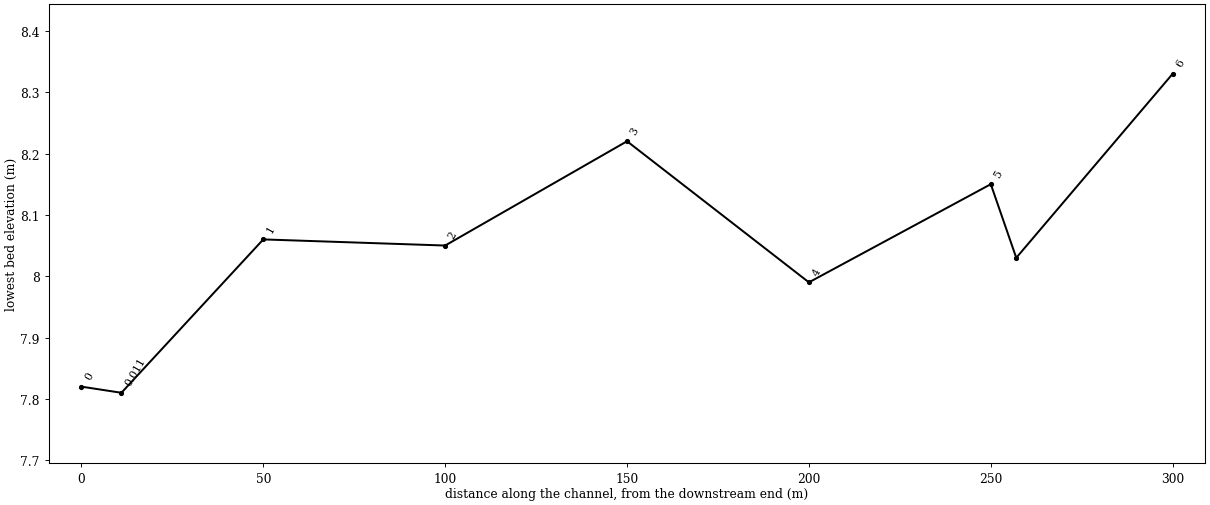
HEC-RAS study mangsang-ch.prj: mangsang-ch

--- mangsang-ch.g01 (geometry) --- (continued)

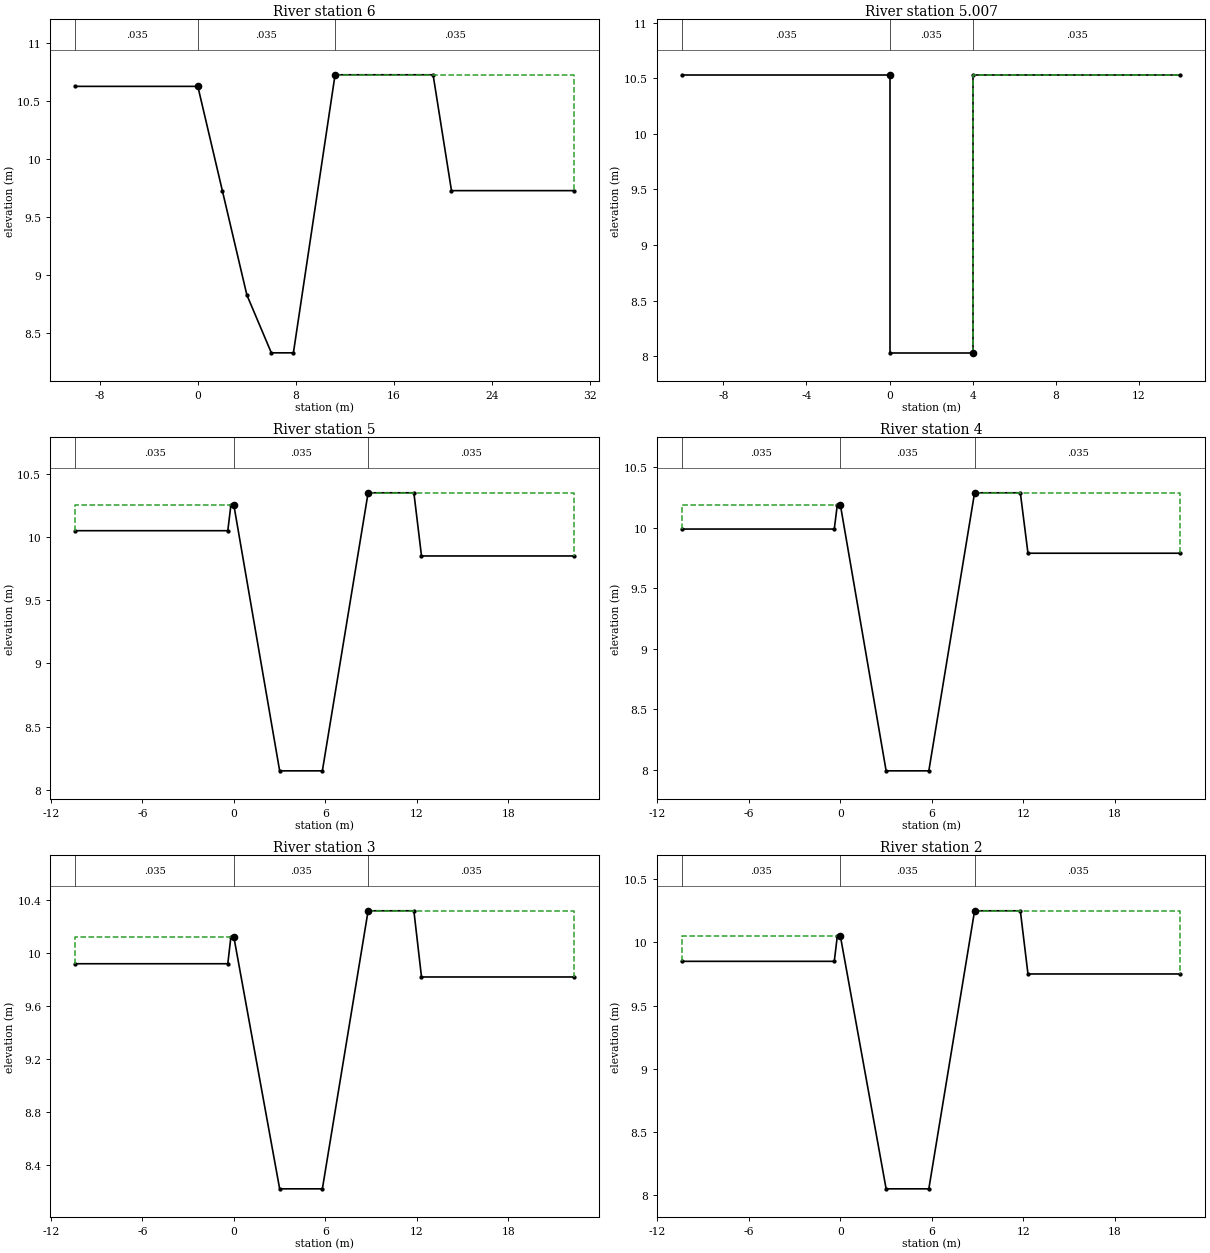
Type RM Length L Ch R = 1 ,6       ,43,43,43
#Sta/Elev= 10
     -10   10.63       0   10.63       2    9.73       4    8.83       6    8.33
     7.8    8.33    11.2   10.73    19.2   10.73    20.7    9.73    30.7    9.73
#Mann= 3 , 0 , 0
     -10    .035       0       0    .035       0    11.2    .035       0
#XS Ineff= 2 , 0
               0   10.63    11.2           10.73
Permanent Ineff=
       F       F
Bank Sta=0,11.2
XS Rating Curve= 0
Exp/Cntr=.3,.1

Type RM Length L Ch R = 1 ,5.007   ,7,7,7
#Sta/Elev= 6
     -10   10.53       0   10.53       0    8.03       4    8.03       4   10.53
      14   10.53
#Mann= 3 , 0 , 0
     -10    .035       0       0    .035       0       4    .035       0
#XS Ineff= 2 , 0
               0   10.53       4           10.53
Permanent Ineff=
       F       F
Bank Sta=0,4
XS Rating Curve= 0
Exp/Cntr=.3,.1

Type RM Length L Ch R = 1 ,5       ,50,50,50
#Sta/Elev= 10
   -10.4   10.05     -.4   10.05     -.2   10.25       0   10.25       3    8.15
     5.8    8.15     8.8   10.35    11.8   10.35    12.3    9.85    22.3    9.85
#Mann= 3 , 0 , 0
   -10.4    .035       0       0    .035       0     8.8    .035       0
#XS Ineff= 2 , 0
               0   10.25     8.8           10.35
Permanent Ineff=
       F       F
Bank Sta=0,8.8
XS Rating Curve= 0
Exp/Cntr=.3,.1

Type RM Length L Ch R = 1 ,4       ,50,50,50
#Sta/Elev= 10
   -10.4    9.99     -.4    9.99     -.2   10.19       0   10.19       3    7.99
     5.8    7.99     8.8   10.29    11.8   10.29    12.3    9.79    22.3    9.79
#Mann= 3 , 0 , 0
   -10.4    .035       0       0    .035       0     8.8    .035       0
#XS Ineff= 2 , 0
               0   10.19     8.8           10.29
Permanent Ineff=
       F       F
Bank Sta=0,8.8
XS Rating Curve= 0
Exp/Cntr=.3,.1

Type RM Length L Ch R = 1 ,3       ,50,50,50
#Sta/Elev= 10
   -10.4    9.92     -.4    9.92     -.2   10.12       0   10.12       3    8.22
     5.8    8.22     8.8   10.32    11.8   10.32    12.3    9.82    22.3    9.82
#Mann= 3 , 0 , 0
   -10.4    .035       0       0    .035       0     8.8    .035       0
#XS Ineff= 2 , 0
               0   10.12     8.8           10.32
Permanent Ineff=
       F       F
Bank Sta=0,8.8
XS Rating Curve= 0
Exp/Cntr=.3,.1

Type RM Length L Ch R = 1 ,2       ,50,50,50
#Sta/Elev= 10
   -10.4    9.85     -.4    9.85     -.2   10.05       0   10.05       3    8.05
     5.8    8.05     8.8   10.25    11.8   10.25    12.3    9.75    22.3    9.75
#Mann= 3 , 0 , 0
   -10.4    .035       0       0    .035       0     8.8    .035       0
#XS Ineff= 2 , 0
               0   10.05     8.8           10.25
Permanent Ineff=
       F       F
Bank Sta=0,8.8
XS Rating Curve= 0
Exp/Cntr=.3,.1

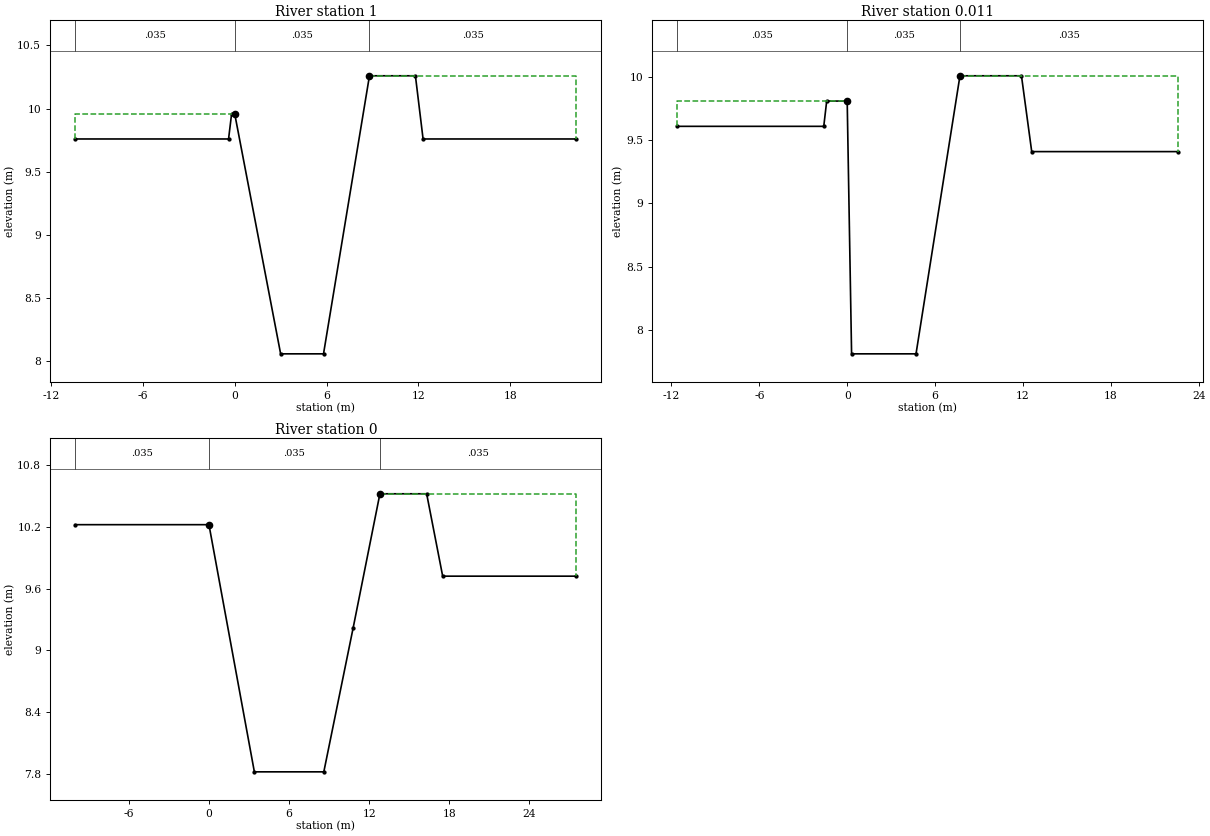
Type RM Length L Ch R = 1 ,1       ,39,39,39
#Sta/Elev= 10
   -10.4    9.76     -.4    9.76     -.2    9.96       0    9.96       3    8.06
     5.8    8.06     8.8   10.26    11.8   10.26    12.3    9.76    22.3    9.76
#Mann= 3 , 0 , 0
   -10.4    .035       0       0    .035       0     8.8    .035       0
#XS Ineff= 2 , 0
               0    9.96     8.8           10.26
Permanent Ineff=
       F       F
Bank Sta=0,8.8
XS Rating Curve= 0
Exp/Cntr=.3,.1

Type RM Length L Ch R = 1 ,0.011   ,11,11,11
#Sta/Elev= 10
   -11.6    9.61    -1.6    9.61    -1.4    9.81       0    9.81      .3    7.81
     4.7    7.81     7.7   10.01    11.9   10.01    12.6    9.41    22.6    9.41
#Mann= 3 , 0 , 0
   -11.6    .035       0       0    .035       0     7.7    .035       0
#XS Ineff= 2 , 0
               0    9.81     7.7           10.01
Permanent Ineff=
       F       F
Bank Sta=0,7.7
XS Rating Curve= 0
Exp/Cntr=.3,.1

Type RM Length L Ch R = 1 ,0       ,0,0,0
#Sta/Elev= 9
     -10   10.22       0   10.22     3.4    7.82     8.6    7.82    10.8    9.22
    12.8   10.52    16.3   10.52    17.5    9.72    27.5    9.72
#Mann= 3 , 0 , 0
     -10    .035       0       0    .035       0    12.8    .035       0
#XS Ineff= 2 , 0
               0   10.22    12.8           10.52
Permanent Ineff=
       F       F
Bank Sta=0,12.8
XS Rating Curve= 0
Exp/Cntr=.3,.1

Chan Stop Cuts=-1