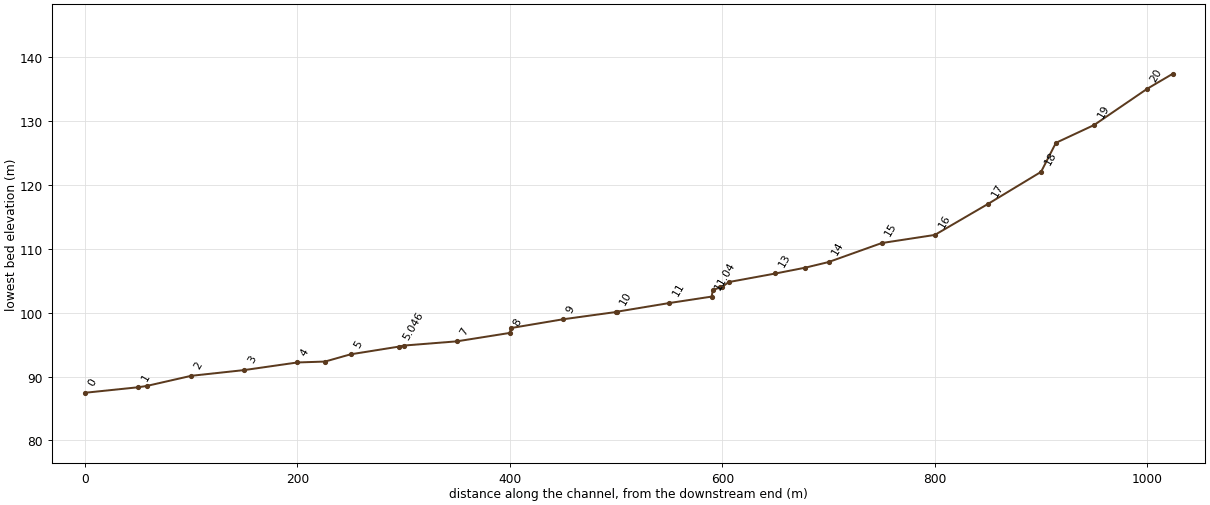
--- soyang-ch.prj (project) ---

Proj Title=soyang-ch
Current Plan=p01
Default Exp/Contr=.3,.1
SI Units
Geom File=g01
Flow File=f01
Plan File=p01
Y Axis Title=Elevation
X Axis Title(PF)=Main Channel Distance
X Axis Title(XS)=Station
BEGIN DESCRIPTION:
           BACK WATER COMPUTATION
      APPLICATION OF HEC-2 BY Samju Construction Engineering
     soyang-ch: 10,20,30,50,80 yr
END DESCRIPTION:
DSS Export Rating Curves= 0
DSS Export Rating Curve Sorted= 0
DSS Export Volume Flow Curves= 0
DXF OffsetX= 0
DXF OffsetY= 0
DXF ScaleX= 1
DXF ScaleY= 10

--- soyang-ch.p01 (plan) ---

Plan Title=Imported Plan 01
Version=Version 3.0.1  Mar 2001
Short Identifier=Imported Pla
Geom File=g01
Flow File=f01
Subcritical Flow
K Sum by GR= 0
Std Step Tol= 0.003
Critical Tol= 0.003
Num of Std Step Trials= 20
Max Error Tol= 0.1
Flow Tol Ratio= 0.001
Split Flow NTrial= 30
Split Flow Tol= 0.02
Split Flow Ratio= 0.02
Log Output Level= 0
Friction Slope Method= 1
Unsteady Friction Slope Method= 2
Parabolic Critical Depth
Global Vel Dist= 0 , 0 , 0
Global Log Level= 0
CheckData=True
Encroach Param=-1 ,0,0, 0
Computation Interval=1HOUR
Output Interval=1HOUR
Run HTab= 0
Run UNet= 0
Run PostProcess= 0
UNET Theta= 1
UNET ZTol= 0.02
UNET ZSATol= 0.1
UNET MxIter= 20
UNET MaxInSteps= 20
UNET DtIC= 0
UNET DtMin= 0
UNET MaxCRTS= 20
UNET WFStab= 2
UNET SFStab= 1
UNET WFX= 1
UNET SFX= 1
UNET Convert EG Bridges=-1
UNET Use Existing IB Tables=-1
Instantaneous Interval=1HOUR
Write IC File= 0
Write Velocity= 0
Write Detailed= 0

--- soyang-ch.f01 (steady flow) ---

Flow Title=Imported Flow 01
Version=Version 3.0.1  Mar 2001
Number of Profiles= 5
Profile Names=PF 1,PF 2,PF 3,PF 4,PF 5
River Rch & RM=RIVER-1,Reach-1         ,20.024
     180     200     220     230     240
Boundary for River Rch & Prof#=RIVER-1,Reach-1         , 1
Up Type= 0
Dn Type= 3
Dn Slope=.0109
Boundary for River Rch & Prof#=RIVER-1,Reach-1         , 2
Up Type= 0
Dn Type= 3
Dn Slope=.0109
Boundary for River Rch & Prof#=RIVER-1,Reach-1         , 3
Up Type= 0
Dn Type= 3
Dn Slope=.0109
Boundary for River Rch & Prof#=RIVER-1,Reach-1         , 4
Up Type= 0
Dn Type= 3
Dn Slope=.0109
Boundary for River Rch & Prof#=RIVER-1,Reach-1         , 5
Up Type= 0
Dn Type= 3
Dn Slope=.0109
DSS Import GetInterval= 0
DSS Import GetPeak= 0
DSS Import FillOption= 0

--- soyang-ch.g01 (geometry) ---

Geom Title=Imported Geom 01
Version=Version 3.0.1  Mar 2001

River Reach=RIVER-1         ,Reach-1
Reach XY= 2
              .5             .95              .5             .05

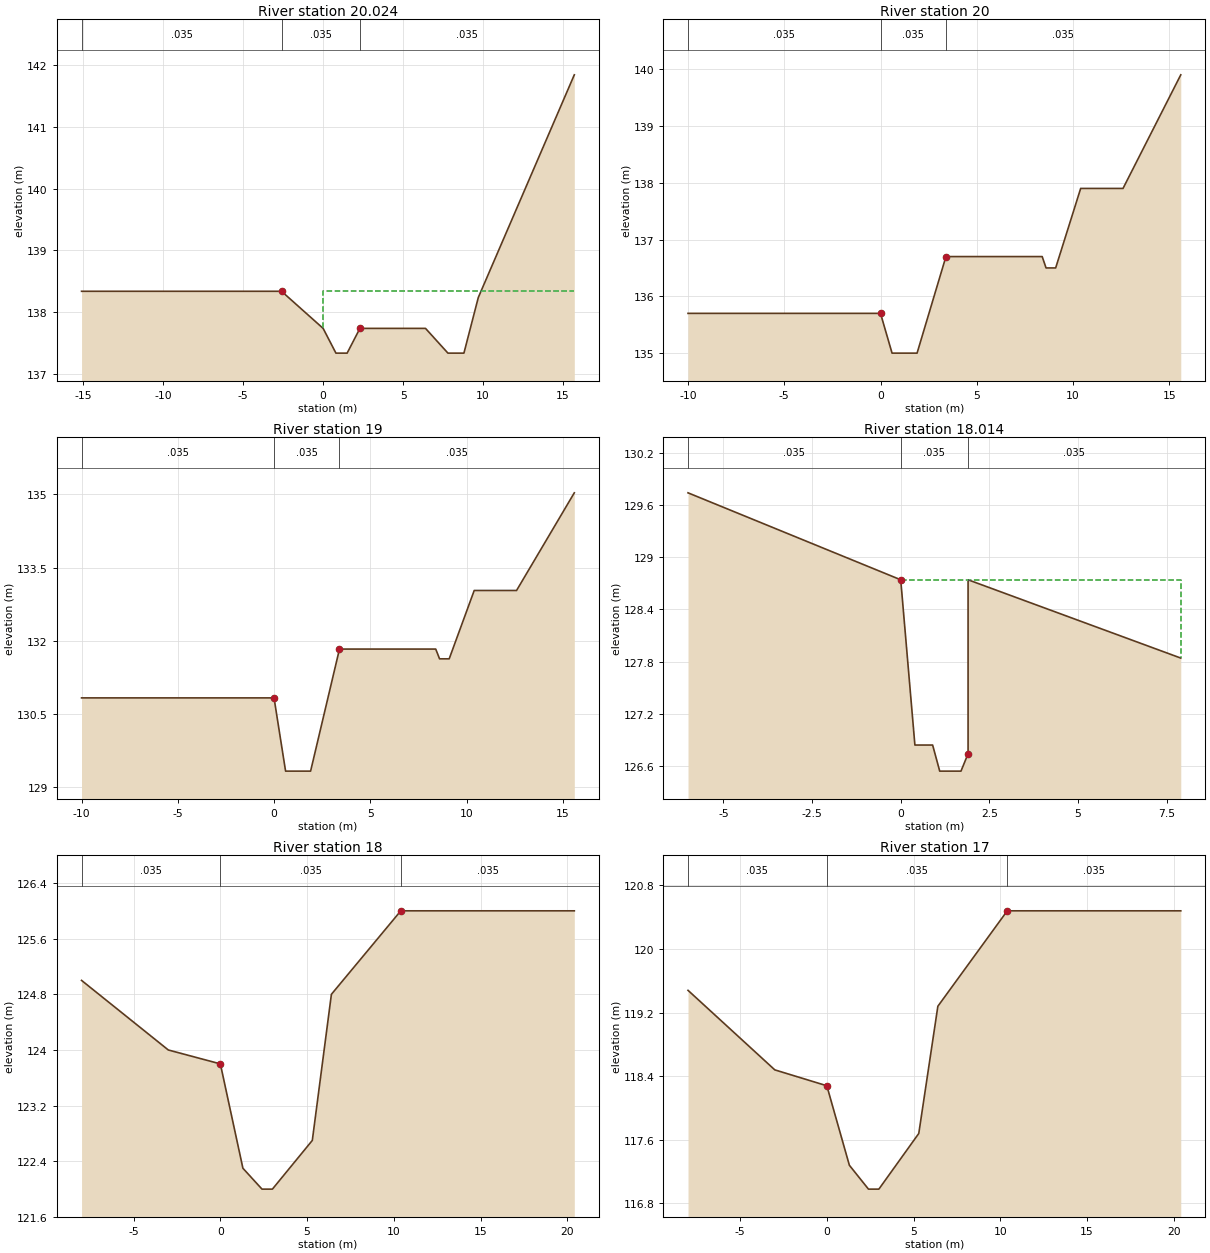
Type RM Length L Ch R = 1 ,20.024  ,24,24,24
#Sta/Elev= 14
   -15.1  138.34    -5.1  138.34    -2.6  138.34       0  137.74      .8  137.34
    1.15  137.34     1.5  137.34     2.3  137.74     6.4  137.74     7.8  137.34
     8.8  137.34     9.7  138.24    12.7  140.04    15.7  141.84
#Mann= 3 , 0 , 0
   -15.1    .035       0    -2.6    .035       0     2.3    .035       0
#XS Ineff= 2 , 0
       0    -2.6  138.34     2.3       0  137.74
Permanent Ineff=
       F       F
Bank Sta=-2.6,2.3
XS Rating Curve= 0
Exp/Cntr=.3,.1

Type RM Length L Ch R = 1 ,20      ,50,50,50
#Sta/Elev= 11
     -10   135.7       0   135.7      .6     135     1.9     135     3.4   136.7
     8.4   136.7     8.6   136.5     9.1   136.5    10.4   137.9    12.6   137.9
    15.6   139.9
#Mann= 3 , 0 , 0
     -10    .035       0       0    .035       0     3.4    .035       0
#XS Ineff= 2 , 0
       0       0   135.7     3.4       0   136.7
Permanent Ineff=
       F       F
Bank Sta=0,3.4
XS Rating Curve= 0
Exp/Cntr=.3,.1

Type RM Length L Ch R = 1 ,19      ,36,36,36
#Sta/Elev= 11
     -10  130.83       0  130.83      .6  129.33     1.9  129.33     3.4  131.83
     8.4  131.83     8.6  131.63     9.1  131.63    10.4  133.03    12.6  133.03
    15.6  135.03
#Mann= 3 , 0 , 0
     -10    .035       0       0    .035       0     3.4    .035       0
#XS Ineff= 2 , 0
               0  130.83     3.4          131.83
Permanent Ineff=
       F       F
Bank Sta=0,3.4
XS Rating Curve= 0
Exp/Cntr=.3,.1

Type RM Length L Ch R = 1 ,18.014  ,14,14,14
#Sta/Elev= 11
      -6  129.74      -3  129.24       0  128.74      .4  126.84      .9  126.84
     1.1  126.54     1.7  126.54     1.9  126.74     1.9  128.74     4.9  128.29
     7.9  127.84
#Mann= 3 , 0 , 0
      -6    .035       0       0    .035       0     1.9    .035       0
#XS Ineff= 2 , 0
       0       0  128.74     1.9       0  126.74
Permanent Ineff=
       F       F
Bank Sta=0,1.9
XS Rating Curve= 0
Exp/Cntr=.3,.1

Type RM Length L Ch R = 1 ,18      ,50,50,50
#Sta/Elev= 11
      -8     125      -3     124       0   123.8     1.3   122.3     2.4     122
     2.7     122       3     122     5.3   122.7     6.4   124.8    10.4     126
    20.4     126
#Mann= 3 , 0 , 0
      -8    .035       0       0    .035       0    10.4    .035       0
#XS Ineff= 2 , 0
               0   123.8    10.4             126
Permanent Ineff=
       F       F
Bank Sta=0,10.4
XS Rating Curve= 0
Exp/Cntr=.3,.1

Type RM Length L Ch R = 1 ,17      ,50,50,50
#Sta/Elev= 11
      -8  119.48      -3  118.48       0  118.28     1.3  117.28     2.4  116.98
     2.7  116.98       3  116.98     5.3  117.68     6.4  119.28    10.4  120.48
    20.4  120.48
#Mann= 3 , 0 , 0
      -8    .035       0       0    .035       0    10.4    .035       0
#XS Ineff= 2 , 0
               0  118.28    10.4          120.48
Permanent Ineff=
       F       F
Bank Sta=0,10.4
XS Rating Curve= 0
Exp/Cntr=.3,.1

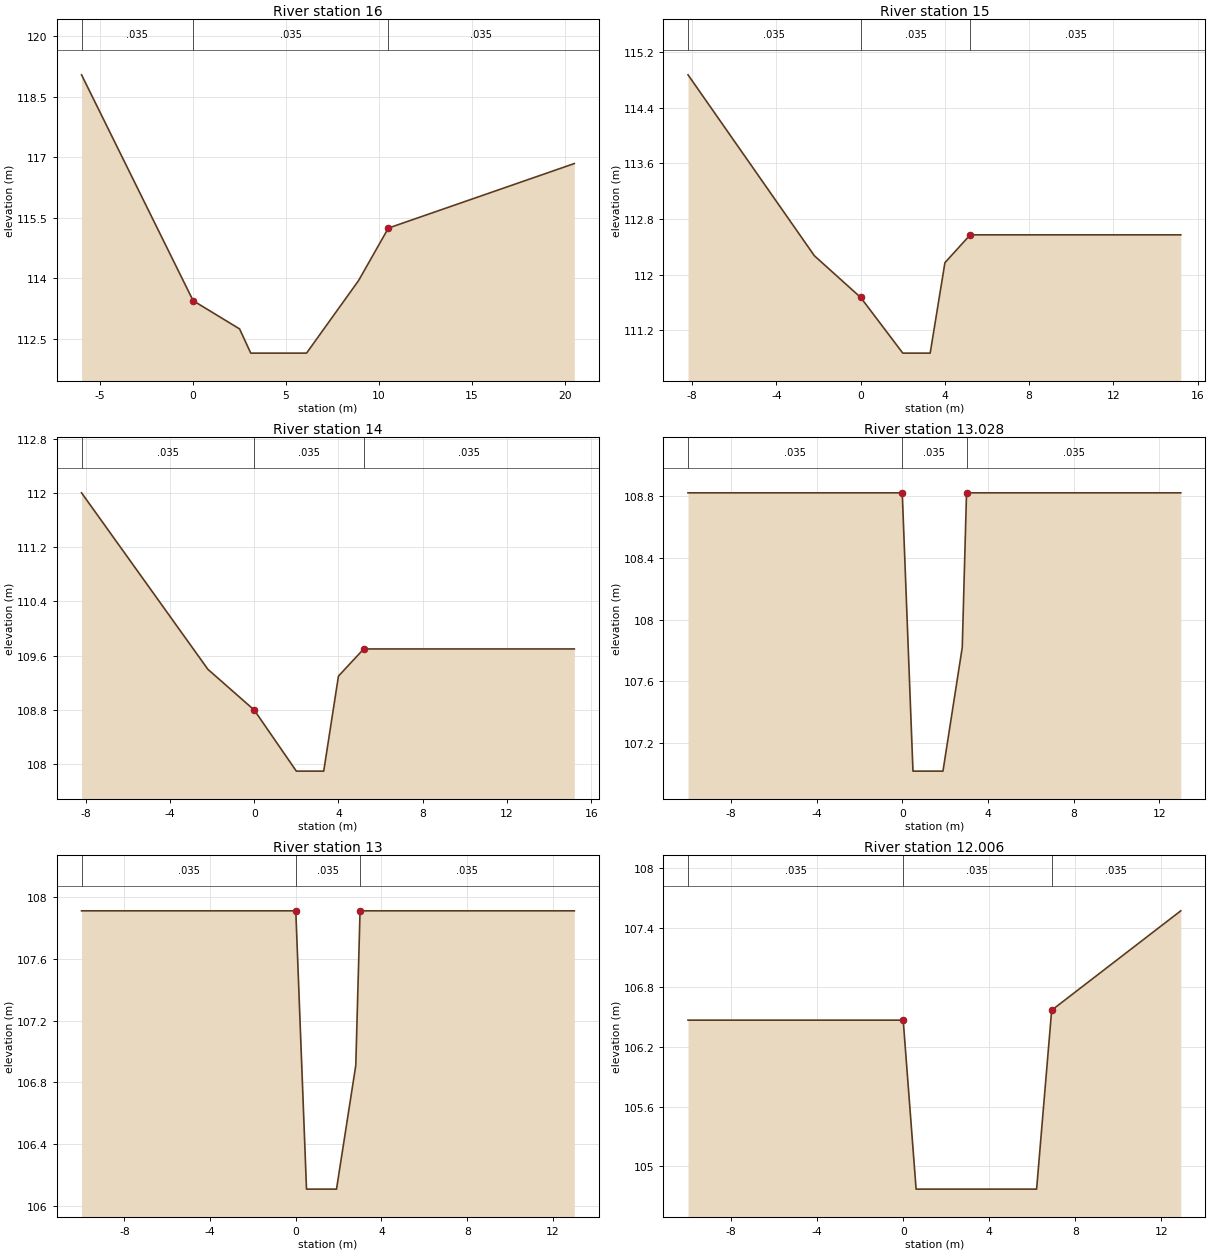
Type RM Length L Ch R = 1 ,16      ,50,50,50
#Sta/Elev= 11
      -6  119.04      -3  116.24       0  113.44     2.5  112.74     3.1  112.14
     4.6  112.14     6.1  112.14     8.9  113.94    10.5  115.24    15.5  116.04
    20.5  116.84
#Mann= 3 , 0 , 0
      -6    .035       0       0    .035       0    10.5    .035       0
#XS Ineff= 2 , 0
       0       0  113.44    10.5       0  115.24
Permanent Ineff=
       F       F
Bank Sta=0,10.5
XS Rating Curve= 0
Exp/Cntr=.3,.1

Type RM Length L Ch R = 1 ,15      ,50,50,50
#Sta/Elev= 9
    -8.2  114.87    -5.2  113.57    -2.2  112.27       0  111.67       2  110.87
     3.3  110.87       4  112.17     5.2  112.57    15.2  112.57
#Mann= 3 , 0 , 0
    -8.2    .035       0       0    .035       0     5.2    .035       0
#XS Ineff= 2 , 0
               0  111.67     5.2          112.57
Permanent Ineff=
       F       F
Bank Sta=0,5.2
XS Rating Curve= 0
Exp/Cntr=.3,.1

Type RM Length L Ch R = 1 ,14      ,22,22,22
#Sta/Elev= 9
    -8.2     112    -5.2   110.7    -2.2   109.4       0   108.8       2   107.9
     3.3   107.9       4   109.3     5.2   109.7    15.2   109.7
#Mann= 3 , 0 , 0
    -8.2    .035       0       0    .035       0     5.2    .035       0
#XS Ineff= 2 , 0
               0   108.8     5.2           109.7
Permanent Ineff=
       F       F
Bank Sta=0,5.2
XS Rating Curve= 0
Exp/Cntr=.3,.1

Type RM Length L Ch R = 1 ,13.028  ,28,28,28
#Sta/Elev= 7
     -10  108.82       0  108.82      .5  107.02     1.9  107.02     2.8  107.82
       3  108.82      13  108.82
#Mann= 3 , 0 , 0
     -10    .035       0       0    .035       0       3    .035       0
#XS Ineff= 2 , 0
               0  108.82       3          108.82
Permanent Ineff=
       F       F
Bank Sta=0,3
XS Rating Curve= 0
Exp/Cntr=.3,.1

Type RM Length L Ch R = 1 ,13      ,44,44,44
#Sta/Elev= 7
     -10  107.91       0  107.91      .5  106.11     1.9  106.11     2.8  106.91
       3  107.91      13  107.91
#Mann= 3 , 0 , 0
     -10    .035       0       0    .035       0       3    .035       0
#XS Ineff= 2 , 0
               0  107.91       3          107.91
Permanent Ineff=
       F       F
Bank Sta=0,3
XS Rating Curve= 0
Exp/Cntr=.3,.1

Type RM Length L Ch R = 1 ,12.006  ,6,6,6
#Sta/Elev= 7
     -10  106.47       0  106.47      .6  104.77     6.2  104.77     6.9  106.57
     9.9  107.07    12.9  107.57
#Mann= 3 , 0 , 0
     -10    .035       0       0    .035       0     6.9    .035       0
#XS Ineff= 2 , 0
               0  106.47     6.9          106.57
Permanent Ineff=
       F       F
Bank Sta=0,6.9
XS Rating Curve= 0
Exp/Cntr=.3,.1

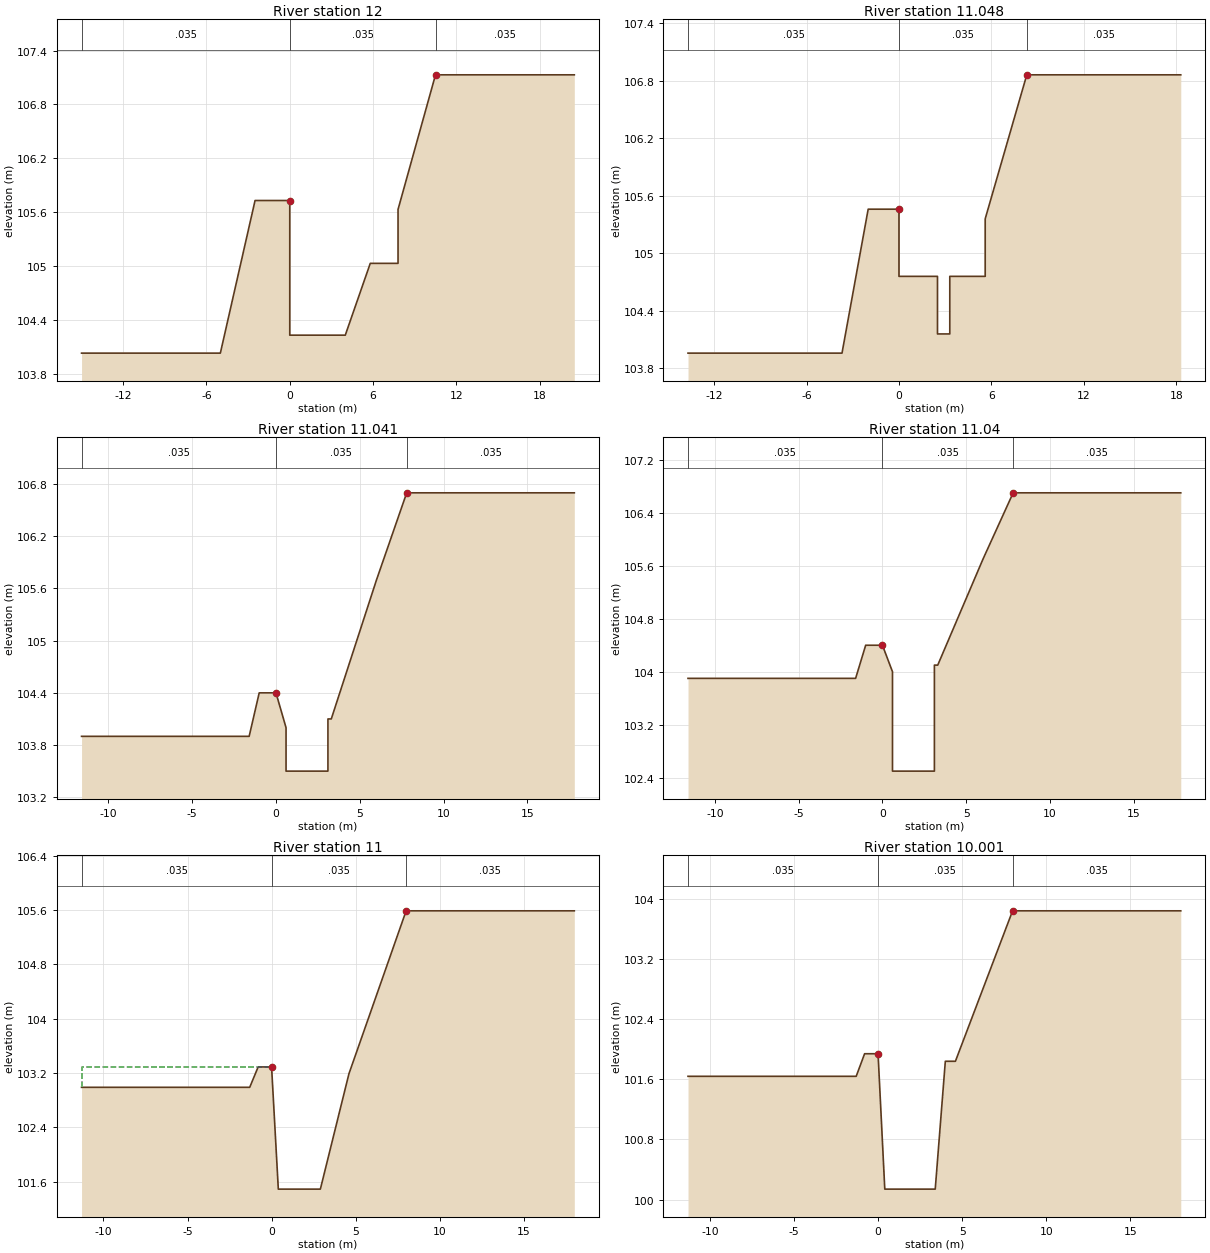
Type RM Length L Ch R = 1 ,12      ,2,2,2
#Sta/Elev= 11
     -15  104.03      -5  104.03    -2.5  105.73       0  105.73       0  104.23
       4  104.23     5.8  105.03     7.8  105.03     7.8  105.63    10.5  107.13
    20.5  107.13
#Mann= 3 , 0 , 0
     -15    .035       0       0    .035       0    10.5    .035       0
#XS Ineff= 2 , 0
       0       0  105.73    10.5       0  107.13
Permanent Ineff=
       F       F
Bank Sta=0,10.5
XS Rating Curve= 0
Exp/Cntr=.3,.1

Type RM Length L Ch R = 1 ,11.048  ,7,7,7
#Sta/Elev= 13
   -13.7  103.96    -3.7  103.96      -2  105.46       0  105.46       0  104.76
     2.5  104.76     2.5  104.16     3.3  104.16     3.3  104.76     5.6  104.76
     5.6  105.36     8.3  106.86    18.3  106.86
#Mann= 3 , 0 , 0
   -13.7    .035       0       0    .035       0     8.3    .035       0
#XS Ineff= 2 , 0
       0       0  105.46     8.3       0  106.86
Permanent Ineff=
       F       F
Bank Sta=0,8.3
XS Rating Curve= 0
Exp/Cntr=.3,.1

Type RM Length L Ch R = 1 ,11.041  ,1,1,1
#Sta/Elev= 12
   -11.6   103.9    -1.6   103.9      -1   104.4       0   104.4      .6     104
      .6   103.5     3.1   103.5     3.1   104.1     3.3   104.1       6   105.7
     7.8   106.7    17.8   106.7
#Mann= 3 , 0 , 0
   -11.6    .035       0       0    .035       0     7.8    .035       0
#XS Ineff= 2 , 0
       0       0   104.4     7.8       0   106.7
Permanent Ineff=
       F       F
Bank Sta=0,7.8
XS Rating Curve= 0
Exp/Cntr=.3,.1

Type RM Length L Ch R = 1 ,11.04   ,40,40,40
#Sta/Elev= 14
   -11.6   103.9    -1.6   103.9      -1   104.4       0   104.4      .6     104
      .6   103.5      .6   102.5     3.1   102.5     3.1   103.5     3.1   104.1
     3.3   104.1       6   105.7     7.8   106.7    17.8   106.7
#Mann= 3 , 0 , 0
   -11.6    .035       0       0    .035       0     7.8    .035       0
#XS Ineff= 2 , 0
       0       0   104.4     7.8       0   106.7
Permanent Ineff=
       F       F
Bank Sta=0,7.8
XS Rating Curve= 0
Exp/Cntr=.3,.1

Type RM Length L Ch R = 1 ,11      ,49,49,49
#Sta/Elev= 9
   -11.3  102.99    -1.3  102.99     -.8  103.29       0  103.29      .4  101.49
     2.9  101.49     4.6  103.19       8  105.59      18  105.59
#Mann= 3 , 0 , 0
   -11.3    .035       0       0    .035       0       8    .035       0
#XS Ineff= 2 , 0
               0  103.29       8          105.59
Permanent Ineff=
       F       F
Bank Sta=0,8
XS Rating Curve= 0
Exp/Cntr=.3,.1

Type RM Length L Ch R = 1 ,10.001  ,1,1,1
#Sta/Elev= 10
   -11.3  101.64    -1.3  101.64     -.8  101.94       0  101.94      .4  100.14
     3.4  100.14       4  101.84     4.6  101.84       8  103.84      18  103.84
#Mann= 3 , 0 , 0
   -11.3    .035       0       0    .035       0       8    .035       0
#XS Ineff= 2 , 0
       0       0  101.94       8       0  103.84
Permanent Ineff=
       F       F
Bank Sta=0,8
XS Rating Curve= 0
Exp/Cntr=.3,.1

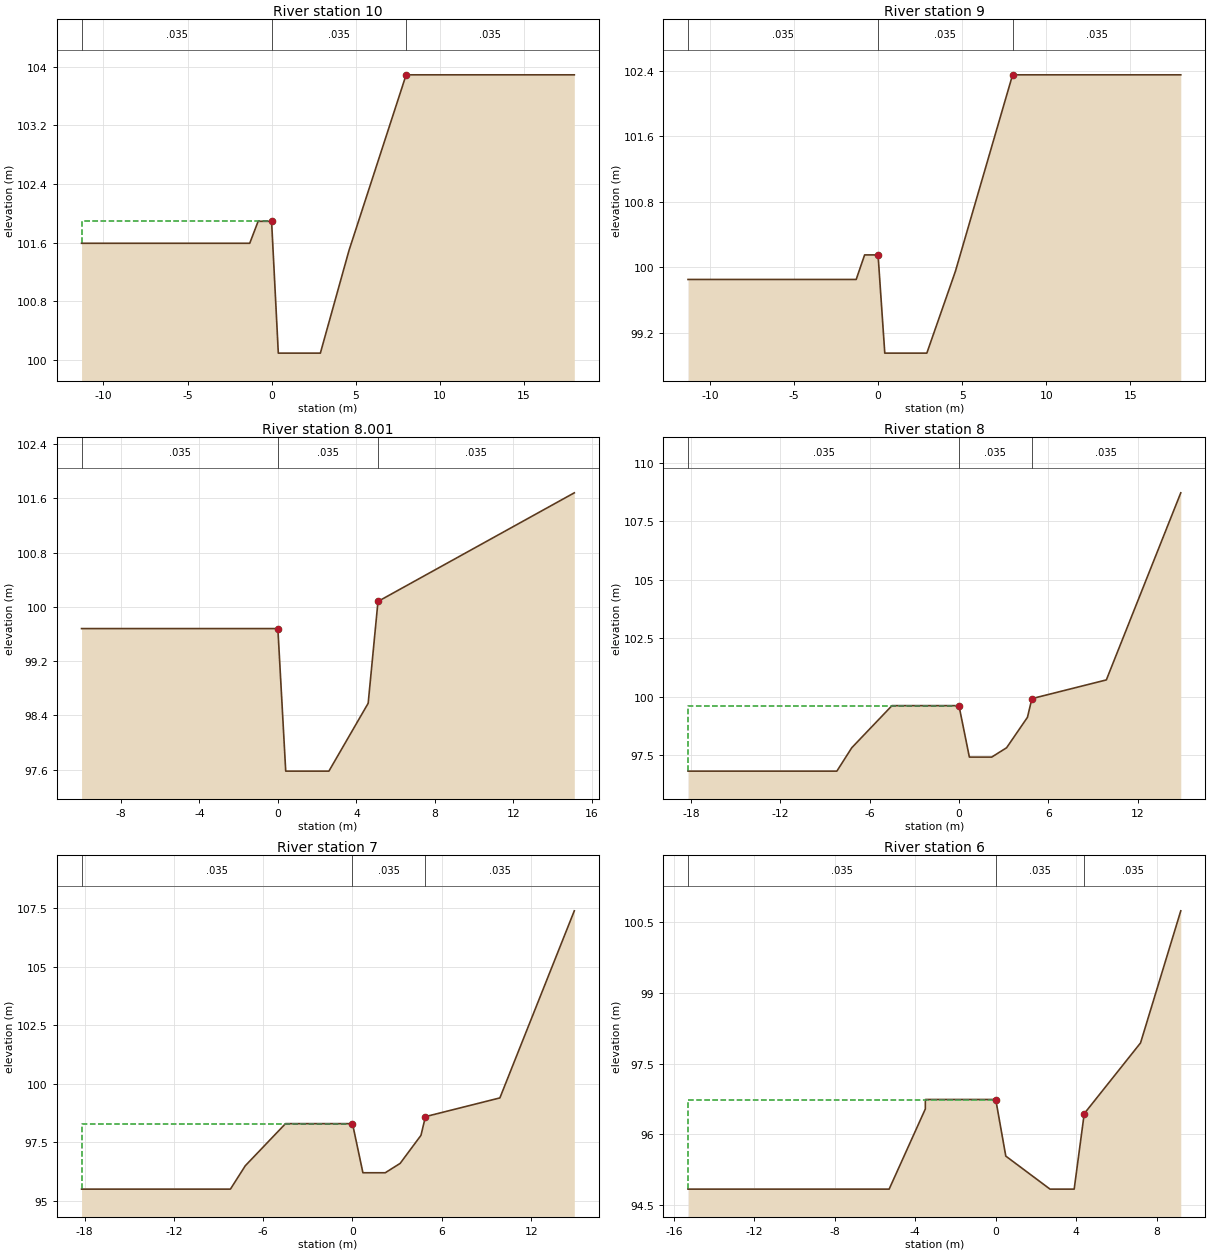
Type RM Length L Ch R = 1 ,10      ,50,50,50
#Sta/Elev= 9
   -11.3  101.59    -1.3  101.59     -.8  101.89       0  101.89      .4  100.09
     2.9  100.09     4.6  101.49       8  103.89      18  103.89
#Mann= 3 , 0 , 0
   -11.3    .035       0       0    .035       0       8    .035       0
#XS Ineff= 2 , 0
               0  101.89       8          103.89
Permanent Ineff=
       F       F
Bank Sta=0,8
XS Rating Curve= 0
Exp/Cntr=.3,.1

Type RM Length L Ch R = 1 ,9       ,49,49,49
#Sta/Elev= 9
   -11.3   99.85    -1.3   99.85     -.8  100.15       0  100.15      .4   98.95
     2.9   98.95     4.6   99.95       8  102.35      18  102.35
#Mann= 3 , 0 , 0
   -11.3    .035       0       0    .035       0       8    .035       0
#XS Ineff= 2 , 0
       0       0  100.15       8       0  102.35
Permanent Ineff=
       F       F
Bank Sta=0,8
XS Rating Curve= 0
Exp/Cntr=.3,.1

Type RM Length L Ch R = 1 ,8.001   ,1,1,1
#Sta/Elev= 8
     -10   99.68       0   99.68      .4   97.58     2.6   97.58     4.6   98.58
     5.1  100.08    10.1  100.88    15.1  101.68
#Mann= 3 , 0 , 0
     -10    .035       0       0    .035       0     5.1    .035       0
#XS Ineff= 2 , 0
               0   99.68     5.1          100.08
Permanent Ineff=
       F       F
Bank Sta=0,5.1
XS Rating Curve= 0
Exp/Cntr=.3,.1

Type RM Length L Ch R = 1 ,8       ,50,50,50
#Sta/Elev= 12
   -18.2   96.82    -8.2   96.82    -7.2   97.82    -4.5   99.62       0   99.62
      .7   97.42     2.2   97.42     3.2   97.82     4.6   99.12     4.9   99.92
     9.9  100.72    14.9  108.72
#Mann= 3 , 0 , 0
   -18.2    .035       0       0    .035       0     4.9    .035       0
#XS Ineff= 2 , 0
               0   99.62     4.9           99.92
Permanent Ineff=
       F       F
Bank Sta=0,4.9
XS Rating Curve= 0
Exp/Cntr=.3,.1

Type RM Length L Ch R = 1 ,7       ,50,50,50
#Sta/Elev= 12
   -18.2    95.5    -8.2    95.5    -7.2    96.5    -4.5    98.3       0    98.3
      .7    96.2     2.2    96.2     3.2    96.6     4.6    97.8     4.9    98.6
     9.9    99.4    14.9   107.4
#Mann= 3 , 0 , 0
   -18.2    .035       0       0    .035       0     4.9    .035       0
#XS Ineff= 2 , 0
               0    98.3     4.9            98.6
Permanent Ineff=
       F       F
Bank Sta=0,4.9
XS Rating Curve= 0
Exp/Cntr=.3,.1

Type RM Length L Ch R = 1 ,6       ,4,4,4
#Sta/Elev= 11
   -15.3   94.84    -5.3   94.84    -3.5   96.54    -3.5   96.74       0   96.74
      .5   95.54     2.7   94.84     3.9   94.84     4.4   96.44     7.2   97.94
     9.2  100.74
#Mann= 3 , 0 , 0
   -15.3    .035       0       0    .035       0     4.4    .035       0
#XS Ineff= 2 , 0
               0   96.74     4.4           96.44
Permanent Ineff=
       F       F
Bank Sta=0,4.4
XS Rating Curve= 0
Exp/Cntr=.3,.1

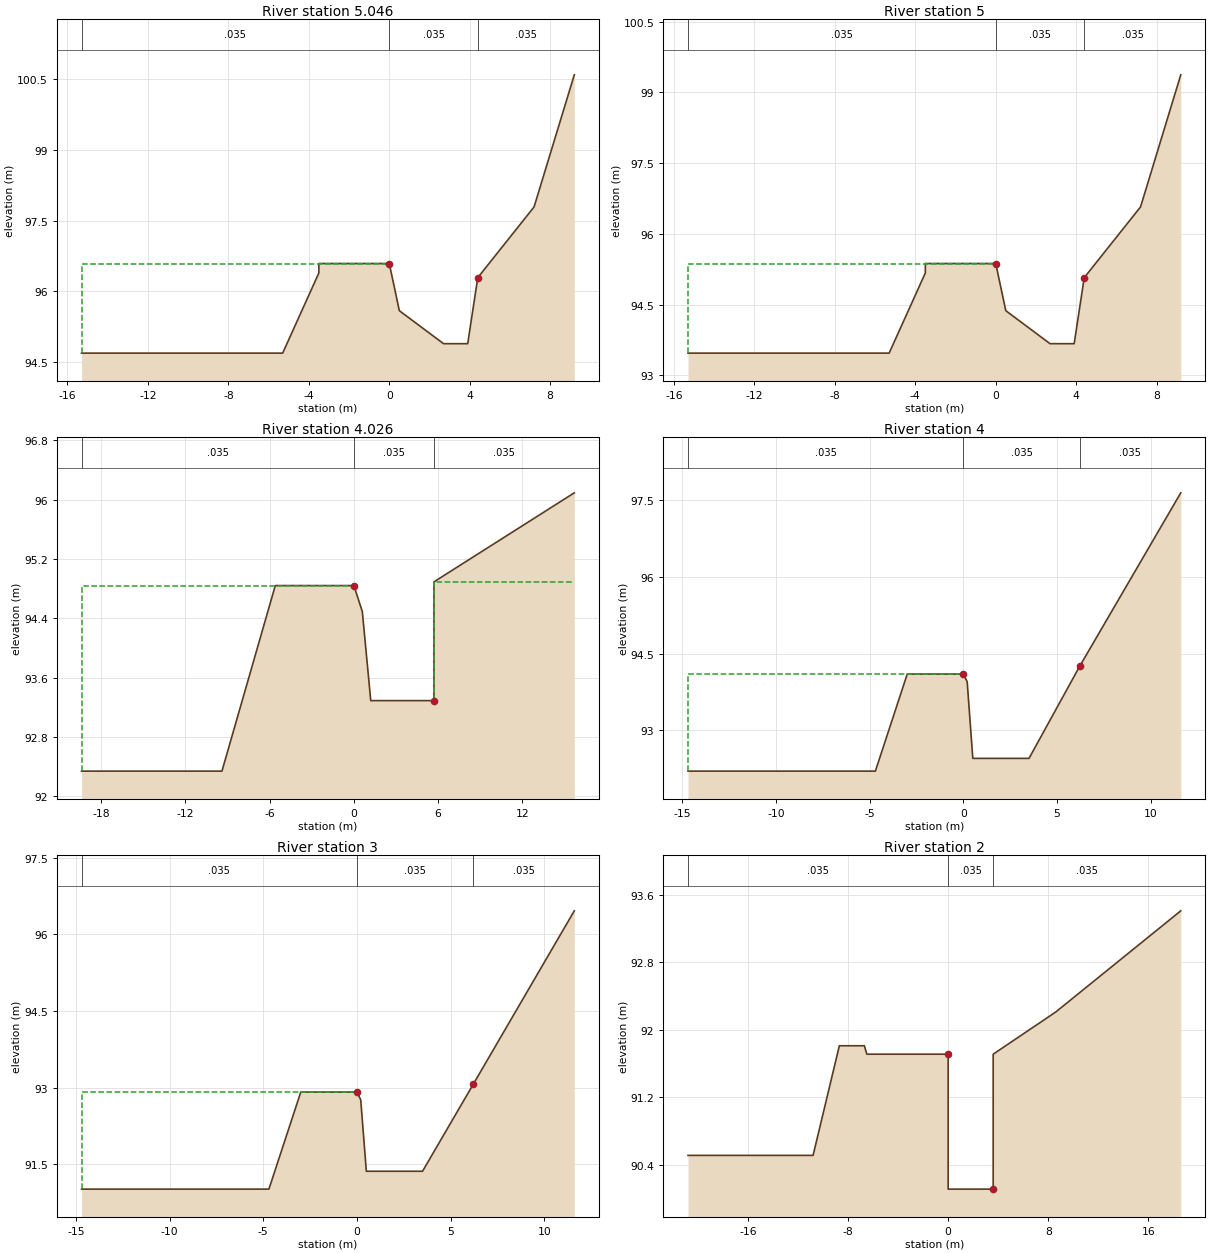
Type RM Length L Ch R = 1 ,5.046   ,46,46,46
#Sta/Elev= 11
   -15.3   94.69    -5.3   94.69    -3.5   96.39    -3.5   96.59       0   96.59
      .5   95.59     2.7   94.89     3.9   94.89     4.4   96.29     7.2   97.79
     9.2  100.59
#Mann= 3 , 0 , 0
   -15.3    .035       0       0    .035       0     4.4    .035       0
#XS Ineff= 2 , 0
               0   96.59     4.4           96.29
Permanent Ineff=
       F       F
Bank Sta=0,4.4
XS Rating Curve= 0
Exp/Cntr=.3,.1

Type RM Length L Ch R = 1 ,5       ,24,24,24
#Sta/Elev= 11
   -15.3   93.47    -5.3   93.47    -3.5   95.17    -3.5   95.37       0   95.37
      .5   94.37     2.7   93.67     3.9   93.67     4.4   95.07     7.2   96.57
     9.2   99.37
#Mann= 3 , 0 , 0
   -15.3    .035       0       0    .035       0     4.4    .035       0
#XS Ineff= 2 , 0
               0   95.37     4.4           95.07
Permanent Ineff=
       F       F
Bank Sta=0,4.4
XS Rating Curve= 0
Exp/Cntr=.3,.1

Type RM Length L Ch R = 1 ,4.026   ,26,26,26
#Sta/Elev= 10
   -19.4   92.34    -9.4   92.34    -5.6   94.84       0   94.84      .6   94.49
     1.2   93.29     5.7   93.29     5.7   94.89    10.7   95.49    15.7   96.09
#Mann= 3 , 0 , 0
   -19.4    .035       0       0    .035       0     5.7    .035       0
#XS Ineff= 2 , 0
               0   94.84     5.7           94.89
Permanent Ineff=
       F       F
Bank Sta=0,5.7
XS Rating Curve= 0
Exp/Cntr=.3,.1

Type RM Length L Ch R = 1 ,4       ,50,50,50
#Sta/Elev= 10
   -14.7    92.2    -4.7    92.2      -3    94.1       0    94.1      .2   93.95
      .5   92.45     3.5   92.45     6.2   94.25     8.9   95.95    11.6   97.65
#Mann= 3 , 0 , 0
   -14.7    .035       0       0    .035       0     6.2    .035       0
#XS Ineff= 2 , 0
               0    94.1     6.2           94.25
Permanent Ineff=
       F       F
Bank Sta=0,6.2
XS Rating Curve= 0
Exp/Cntr=.3,.1

Type RM Length L Ch R = 1 ,3       ,50,50,50
#Sta/Elev= 10
   -14.7   91.01    -4.7   91.01      -3   92.91       0   92.91      .2   92.76
      .5   91.36     3.5   91.36     6.2   93.06     8.9   94.76    11.6   96.46
#Mann= 3 , 0 , 0
   -14.7    .035       0       0    .035       0     6.2    .035       0
#XS Ineff= 2 , 0
               0   92.91     6.2           93.06
Permanent Ineff=
       F       F
Bank Sta=0,6.2
XS Rating Curve= 0
Exp/Cntr=.3,.1

Type RM Length L Ch R = 1 ,2       ,42,42,42
#Sta/Elev= 12
   -20.8   90.51   -10.8   90.51    -8.7   91.81    -6.7   91.81    -6.5   91.71
       0   91.71       0   90.11     3.6   90.11     3.6   91.71     8.6   92.21
    13.6   92.81    18.6   93.41
#Mann= 3 , 0 , 0
   -20.8    .035       0       0    .035       0     3.6    .035       0
#XS Ineff= 2 , 0
       0       0   91.71     3.6       0   90.11
Permanent Ineff=
       F       F
Bank Sta=0,3.6
XS Rating Curve= 0
Exp/Cntr=.3,.1

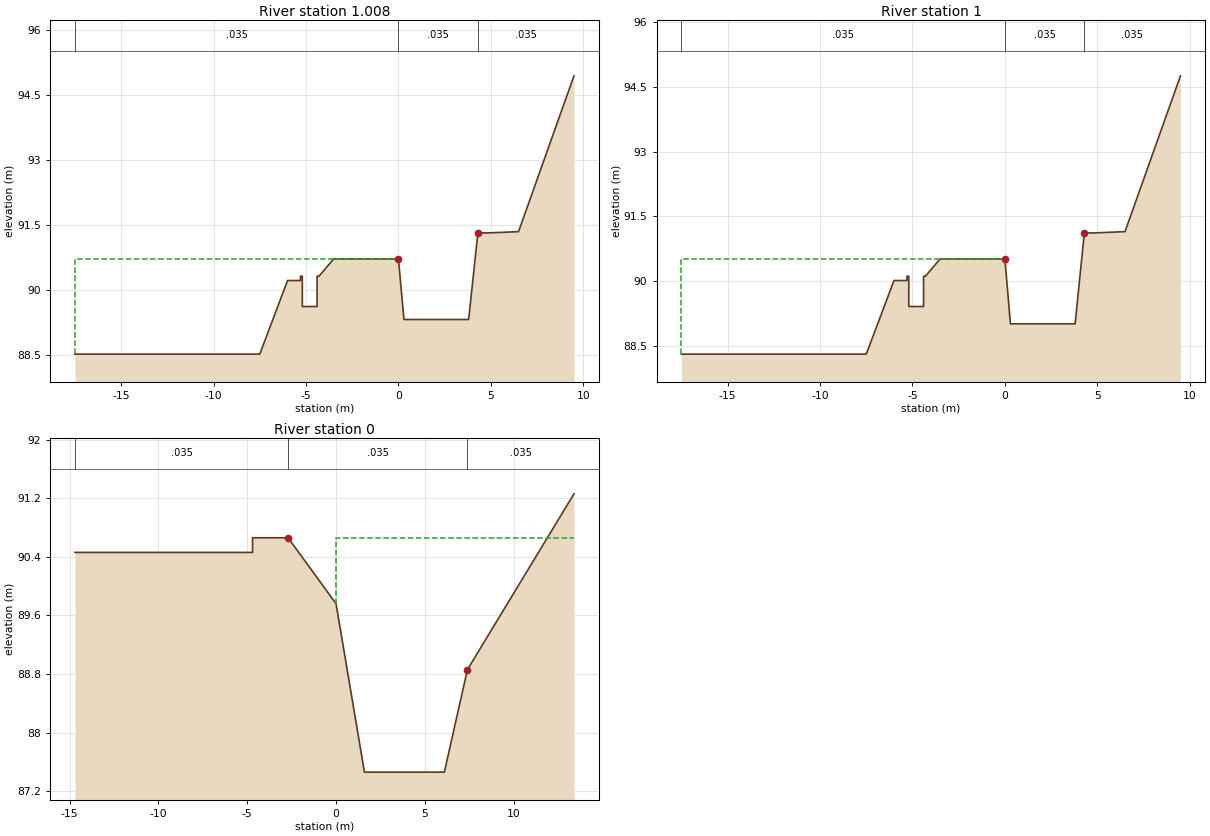
Type RM Length L Ch R = 1 ,1.008   ,8,8,8
#Sta/Elev= 19
   -17.5   88.52    -7.5   88.52      -6   90.22    -5.3   90.22    -5.3   90.32
    -5.2   90.32    -5.2   89.62    -4.4   89.62    -4.4   90.32    -4.3   90.32
    -3.5   90.72       0   90.72      .3   89.32     3.8   89.32     4.3   91.32
     4.8   91.32     6.5   91.35       8   93.15     9.5   94.95
#Mann= 3 , 0 , 0
   -17.5    .035       0       0    .035       0     4.3    .035       0
#XS Ineff= 2 , 0
               0   90.72     4.3           91.32
Permanent Ineff=
       F       F
Bank Sta=0,4.3
XS Rating Curve= 0
Exp/Cntr=.3,.1

Type RM Length L Ch R = 1 ,1       ,50,50,50
#Sta/Elev= 19
   -17.5   88.32    -7.5   88.32      -6   90.02    -5.3   90.02    -5.3   90.12
    -5.2   90.12    -5.2   89.42    -4.4   89.42    -4.4   90.12    -4.3   90.12
    -3.5   90.52       0   90.52      .3   89.02     3.8   89.02     4.3   91.12
     4.8   91.12     6.5   91.15       8   92.95     9.5   94.75
#Mann= 3 , 0 , 0
   -17.5    .035       0       0    .035       0     4.3    .035       0
#XS Ineff= 2 , 0
               0   90.52     4.3           91.12
Permanent Ineff=
       F       F
Bank Sta=0,4.3
XS Rating Curve= 0
Exp/Cntr=.3,.1

Type RM Length L Ch R = 1 ,0       ,0,0,0
#Sta/Elev= 10
   -14.7   90.46    -4.7   90.46    -4.7   90.66    -2.7   90.66       0   89.76
     1.6   87.46     6.1   87.46     7.4   88.86    10.4   90.06    13.4   91.26
#Mann= 3 , 0 , 0
   -14.7    .035       0    -2.7    .035       0     7.4    .035       0
#XS Ineff= 2 , 0
       0    -2.7   90.66     7.4       0   88.86
Permanent Ineff=
       F       F
Bank Sta=-2.7,7.4
XS Rating Curve= 0
Exp/Cntr=.3,.1

Chan Stop Cuts=-1