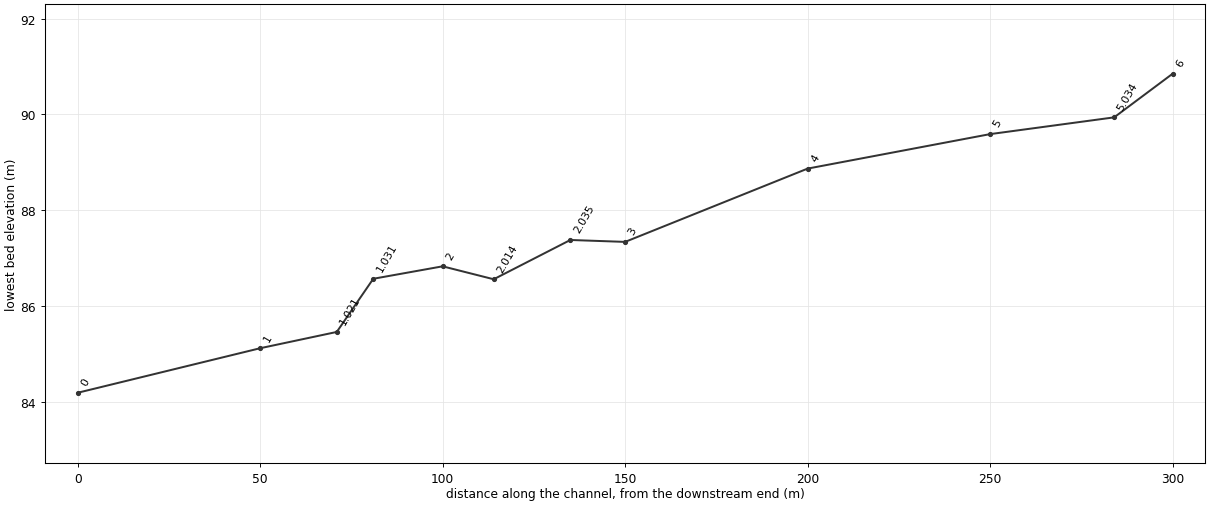
HEC-RAS study doondae-ch.prj: doondae-ch

--- doondae-ch.g01 (geometry) --- (continued)

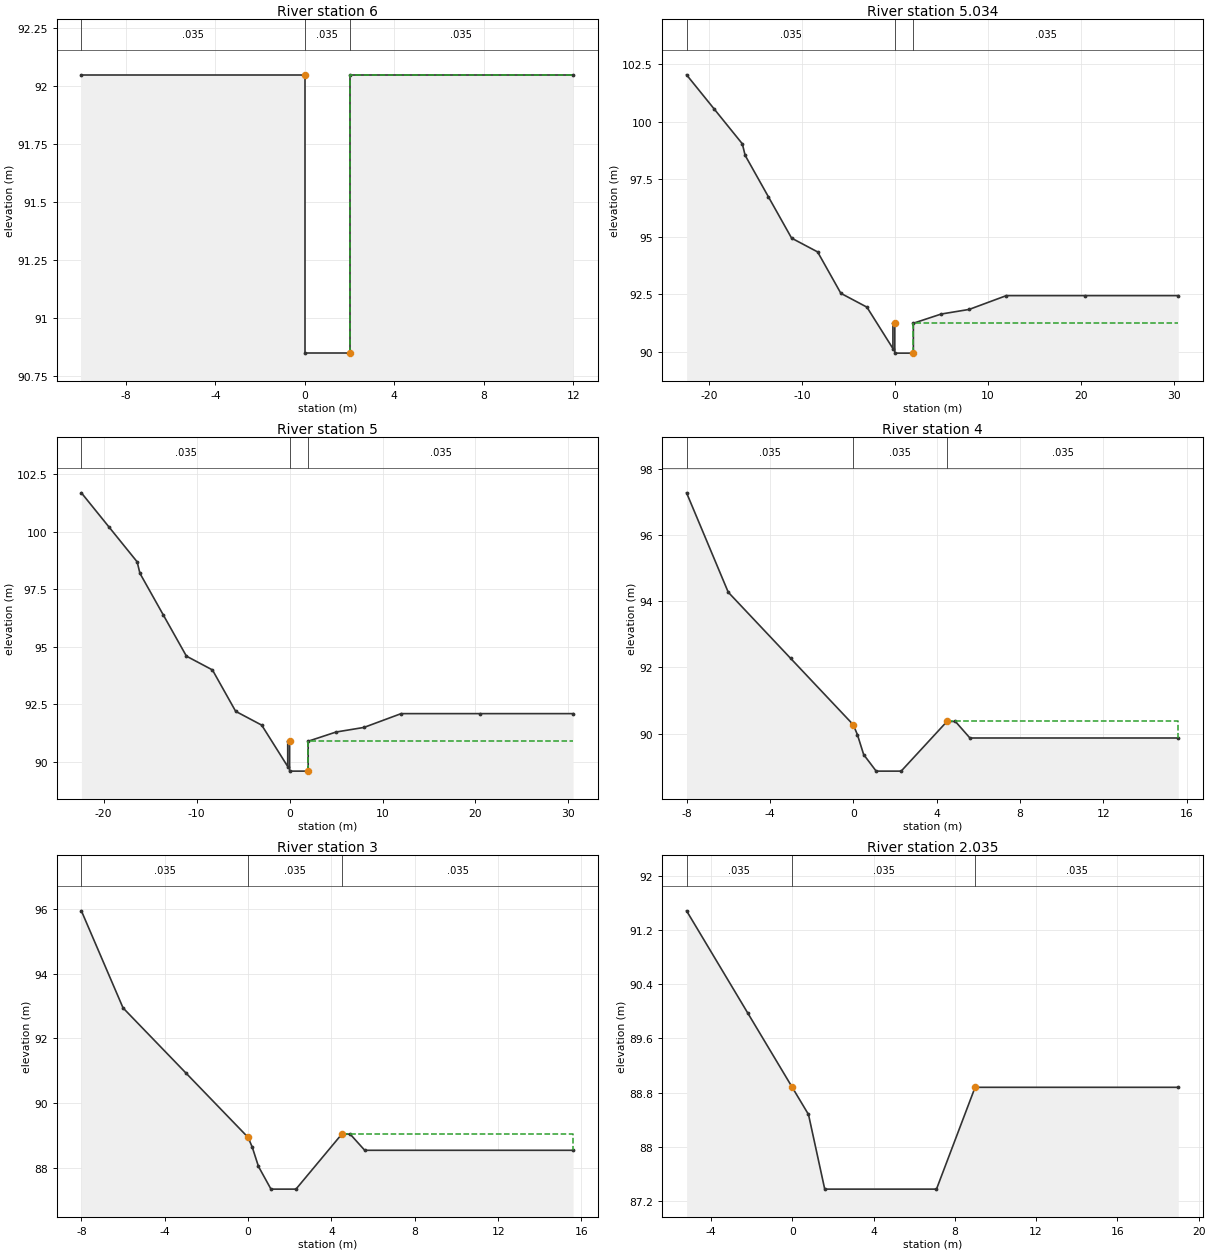
Type RM Length L Ch R = 1 ,6       ,16,16,16
#Sta/Elev= 6
     -10   92.05       0   92.05       0   90.85       2   90.85       2   92.05
      12   92.05
#Mann= 3 , 0 , 0
     -10    .035       0       0    .035       0       2    .035       0
#XS Ineff= 2 , 0
               0   92.05       2           92.05
Permanent Ineff=
       F       F
Bank Sta=0,2
XS Rating Curve= 0
Exp/Cntr=.3,.1

Type RM Length L Ch R = 1 ,5.034   ,34,34,34
#Sta/Elev= 20
   -22.4  102.04   -19.4  100.54   -16.4   99.04   -16.1   98.54   -13.6   96.74
   -11.1   94.94    -8.3   94.34    -5.8   92.54      -3   91.94     -.2   90.14
     -.2   91.24       0   91.24       0   89.94       2   89.94       2   91.24
       5   91.64       8   91.84      12   92.44    20.5   92.44    30.5   92.44
#Mann= 3 , 0 , 0
   -22.4    .035       0       0    .035       0       2    .035       0
#XS Ineff= 2 , 0
               0   91.24       2           91.24
Permanent Ineff=
       F       F
Bank Sta=0,2
XS Rating Curve= 0
Exp/Cntr=.3,.1

Type RM Length L Ch R = 1 ,5       ,50,50,50
#Sta/Elev= 20
   -22.4  101.69   -19.4  100.19   -16.4   98.69   -16.1   98.19   -13.6   96.39
   -11.1   94.59    -8.3   93.99    -5.8   92.19      -3   91.59     -.2   89.79
     -.2   90.89       0   90.89       0   89.59       2   89.59       2   90.89
       5   91.29       8   91.49      12   92.09    20.5   92.09    30.5   92.09
#Mann= 3 , 0 , 0
   -22.4    .035       0       0    .035       0       2    .035       0
#XS Ineff= 2 , 0
               0   90.89       2           90.89
Permanent Ineff=
       F       F
Bank Sta=0,2
XS Rating Curve= 0
Exp/Cntr=.3,.1

Type RM Length L Ch R = 1 ,4       ,50,50,50
#Sta/Elev= 12
      -8   97.27      -6   94.27      -3   92.27       0   90.27      .2   89.97
      .5   89.37     1.1   88.87     2.3   88.87     4.5   90.37     4.9   90.37
     5.6   89.87    15.6   89.87
#Mann= 3 , 0 , 0
      -8    .035       0       0    .035       0     4.5    .035       0
#XS Ineff= 2 , 0
               0   90.27     4.5           90.37
Permanent Ineff=
       F       F
Bank Sta=0,4.5
XS Rating Curve= 0
Exp/Cntr=.3,.1

Type RM Length L Ch R = 1 ,3       ,15,15,15
#Sta/Elev= 12
      -8   95.94      -6   92.94      -3   90.94       0   88.94      .2   88.64
      .5   88.04     1.1   87.34     2.3   87.34     4.5   89.04     4.9   89.04
     5.6   88.54    15.6   88.54
#Mann= 3 , 0 , 0
      -8    .035       0       0    .035       0     4.5    .035       0
#XS Ineff= 2 , 0
               0   88.94     4.5           89.04
Permanent Ineff=
       F       F
Bank Sta=0,4.5
XS Rating Curve= 0
Exp/Cntr=.3,.1

Type RM Length L Ch R = 1 ,2.035   ,21,21,21
#Sta/Elev= 8
    -5.2   91.48    -2.2   89.98       0   88.88      .8   88.48     1.6   87.38
     7.1   87.38       9   88.88      19   88.88
#Mann= 3 , 0 , 0
    -5.2    .035       0       0    .035       0       9    .035       0
#XS Ineff= 2 , 0
               0   88.88       9           88.88
Permanent Ineff=
       F       F
Bank Sta=0,9
XS Rating Curve= 0
Exp/Cntr=.3,.1

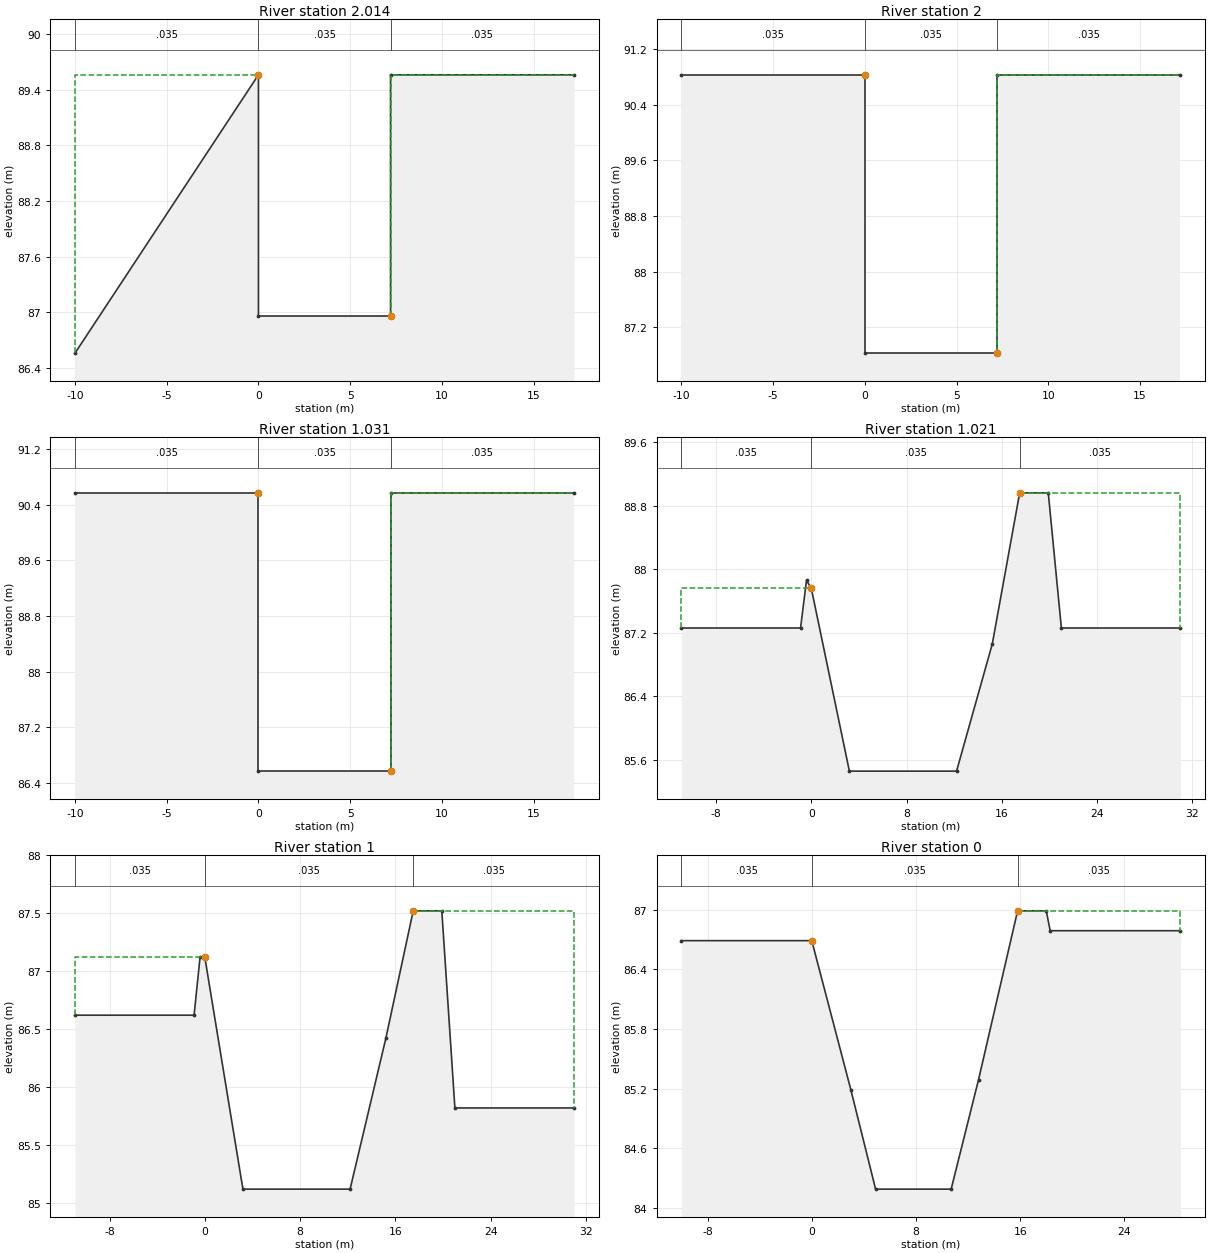
Type RM Length L Ch R = 1 ,2.014   ,14,14,14
#Sta/Elev= 6
     -10   86.56       0   89.56       0   86.96     7.2   86.96     7.2   89.56
    17.2   89.56
#Mann= 3 , 0 , 0
     -10    .035       0       0    .035       0     7.2    .035       0
#XS Ineff= 2 , 0
               0   89.56     7.2           89.56
Permanent Ineff=
       F       F
Bank Sta=0,7.2
XS Rating Curve= 0
Exp/Cntr=.3,.1

Type RM Length L Ch R = 1 ,2       ,19,19,19
#Sta/Elev= 6
     -10   90.83       0   90.83       0   86.83     7.2   86.83     7.2   90.83
    17.2   90.83
#Mann= 3 , 0 , 0
     -10    .035       0       0    .035       0     7.2    .035       0
#XS Ineff= 2 , 0
               0   90.83     7.2           90.83
Permanent Ineff=
       F       F
Bank Sta=0,7.2
XS Rating Curve= 0
Exp/Cntr=.3,.1

Type RM Length L Ch R = 1 ,1.031   ,10,10,10
#Sta/Elev= 6
     -10   90.57       0   90.57       0   86.57     7.2   86.57     7.2   90.57
    17.2   90.57
#Mann= 3 , 0 , 0
     -10    .035       0       0    .035       0     7.2    .035       0
#XS Ineff= 2 , 0
               0   90.57     7.2           90.57
Permanent Ineff=
       F       F
Bank Sta=0,7.2
XS Rating Curve= 0
Exp/Cntr=.3,.1

Type RM Length L Ch R = 1 ,1.021   ,21,21,21
#Sta/Elev= 11
   -10.9   87.26     -.9   87.26     -.4   87.86       0   87.76     3.2   85.46
    12.2   85.46    15.2   87.06    17.5   88.96    19.9   88.96      21   87.26
      31   87.26
#Mann= 3 , 0 , 0
   -10.9    .035       0       0    .035       0    17.5    .035       0
#XS Ineff= 2 , 0
               0   87.76    17.5           88.96
Permanent Ineff=
       F       F
Bank Sta=0,17.5
XS Rating Curve= 0
Exp/Cntr=.3,.1

Type RM Length L Ch R = 1 ,1       ,50,50,50
#Sta/Elev= 11
   -10.9   86.62     -.9   86.62     -.4   87.12       0   87.12     3.2   85.12
    12.2   85.12    15.2   86.42    17.5   87.52    19.9   87.52      21   85.82
      31   85.82
#Mann= 3 , 0 , 0
   -10.9    .035       0       0    .035       0    17.5    .035       0
#XS Ineff= 2 , 0
               0   87.12    17.5           87.52
Permanent Ineff=
       F       F
Bank Sta=0,17.5
XS Rating Curve= 0
Exp/Cntr=.3,.1

Type RM Length L Ch R = 1 ,0       ,0,0,0
#Sta/Elev= 10
     -10   86.69       0   86.69       3   85.19     4.9   84.19    10.7   84.19
    12.8   85.29    15.8   86.99      18   86.99    18.3   86.79    28.3   86.79
#Mann= 3 , 0 , 0
     -10    .035       0       0    .035       0    15.8    .035       0
#XS Ineff= 2 , 0
               0   86.69    15.8           86.99
Permanent Ineff=
       F       F
Bank Sta=0,15.8
XS Rating Curve= 0
Exp/Cntr=.3,.1

Chan Stop Cuts=-1