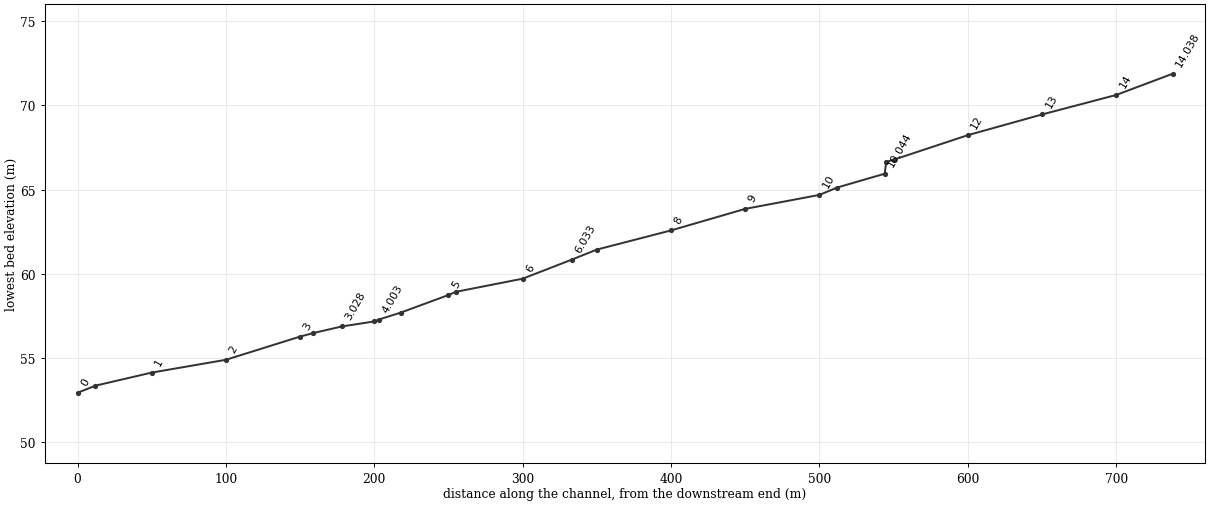
--- wonzawool-ch.prj (project) ---

Proj Title=wonzawool-ch
Current Plan=p01
Default Exp/Contr=.3,.1
SI Units
Geom File=g01
Flow File=f01
Plan File=p01
Y Axis Title=Elevation
X Axis Title(PF)=Main Channel Distance
X Axis Title(XS)=Station
BEGIN DESCRIPTION:
           BACK WATER COMPUTATION
      APPLICATION OF HEC-2 BY Samju Construction Engineering
      wonzawool-ch: 10,20,30,50,80 yr
END DESCRIPTION:
DSS Export Rating Curves= 0
DSS Export Rating Curve Sorted= 0
DSS Export Volume Flow Curves= 0
DXF OffsetX= 0
DXF OffsetY= 0
DXF ScaleX= 1
DXF ScaleY= 10

--- wonzawool-ch.p01 (plan) ---

Plan Title=Imported Plan 01
Version=Version 3.0.1  Mar 2001
Short Identifier=Imported Pla
Geom File=g01
Flow File=f01
Subcritical Flow
K Sum by GR= 0
Std Step Tol= 0.003
Critical Tol= 0.003
Num of Std Step Trials= 20
Max Error Tol= 0.1
Flow Tol Ratio= 0.001
Split Flow NTrial= 30
Split Flow Tol= 0.02
Split Flow Ratio= 0.02
Log Output Level= 0
Friction Slope Method= 1
Unsteady Friction Slope Method= 2
Parabolic Critical Depth
Global Vel Dist= 0 , 0 , 0
Global Log Level= 0
CheckData=True
Encroach Param=-1 ,0,0, 0
Computation Interval=1HOUR
Output Interval=1HOUR
Run HTab= 0
Run UNet= 0
Run PostProcess= 0
UNET Theta= 1
UNET ZTol= 0.02
UNET ZSATol= 0.1
UNET MxIter= 20
UNET MaxInSteps= 20
UNET DtIC= 0
UNET DtMin= 0
UNET MaxCRTS= 20
UNET WFStab= 2
UNET SFStab= 1
UNET WFX= 1
UNET SFX= 1
UNET Convert EG Bridges=-1
UNET Use Existing IB Tables=-1
Instantaneous Interval=1HOUR
Write IC File= 0
Write Velocity= 0
Write Detailed= 0

--- wonzawool-ch.f01 (steady flow) ---

Flow Title=Imported Flow 01
Version=Version 3.0.1  Mar 2001
Number of Profiles= 5
Profile Names=PF 1,PF 2,PF 3,PF 4,PF 5
River Rch & RM=RIVER-1,Reach-1         ,14.038
     180     200     220     230     240
Boundary for River Rch & Prof#=RIVER-1,Reach-1         , 1
Up Type= 0
Dn Type= 3
Dn Slope=.0109
Boundary for River Rch & Prof#=RIVER-1,Reach-1         , 2
Up Type= 0
Dn Type= 3
Dn Slope=.0109
Boundary for River Rch & Prof#=RIVER-1,Reach-1         , 3
Up Type= 0
Dn Type= 3
Dn Slope=.0109
Boundary for River Rch & Prof#=RIVER-1,Reach-1         , 4
Up Type= 0
Dn Type= 3
Dn Slope=.0109
Boundary for River Rch & Prof#=RIVER-1,Reach-1         , 5
Up Type= 0
Dn Type= 3
Dn Slope=.0109
DSS Import GetInterval= 0
DSS Import GetPeak= 0
DSS Import FillOption= 0

--- wonzawool-ch.g01 (geometry) ---

Geom Title=Imported Geom 01
Version=Version 3.0.1  Mar 2001

River Reach=RIVER-1         ,Reach-1
Reach XY= 2
              .5             .95              .5             .05

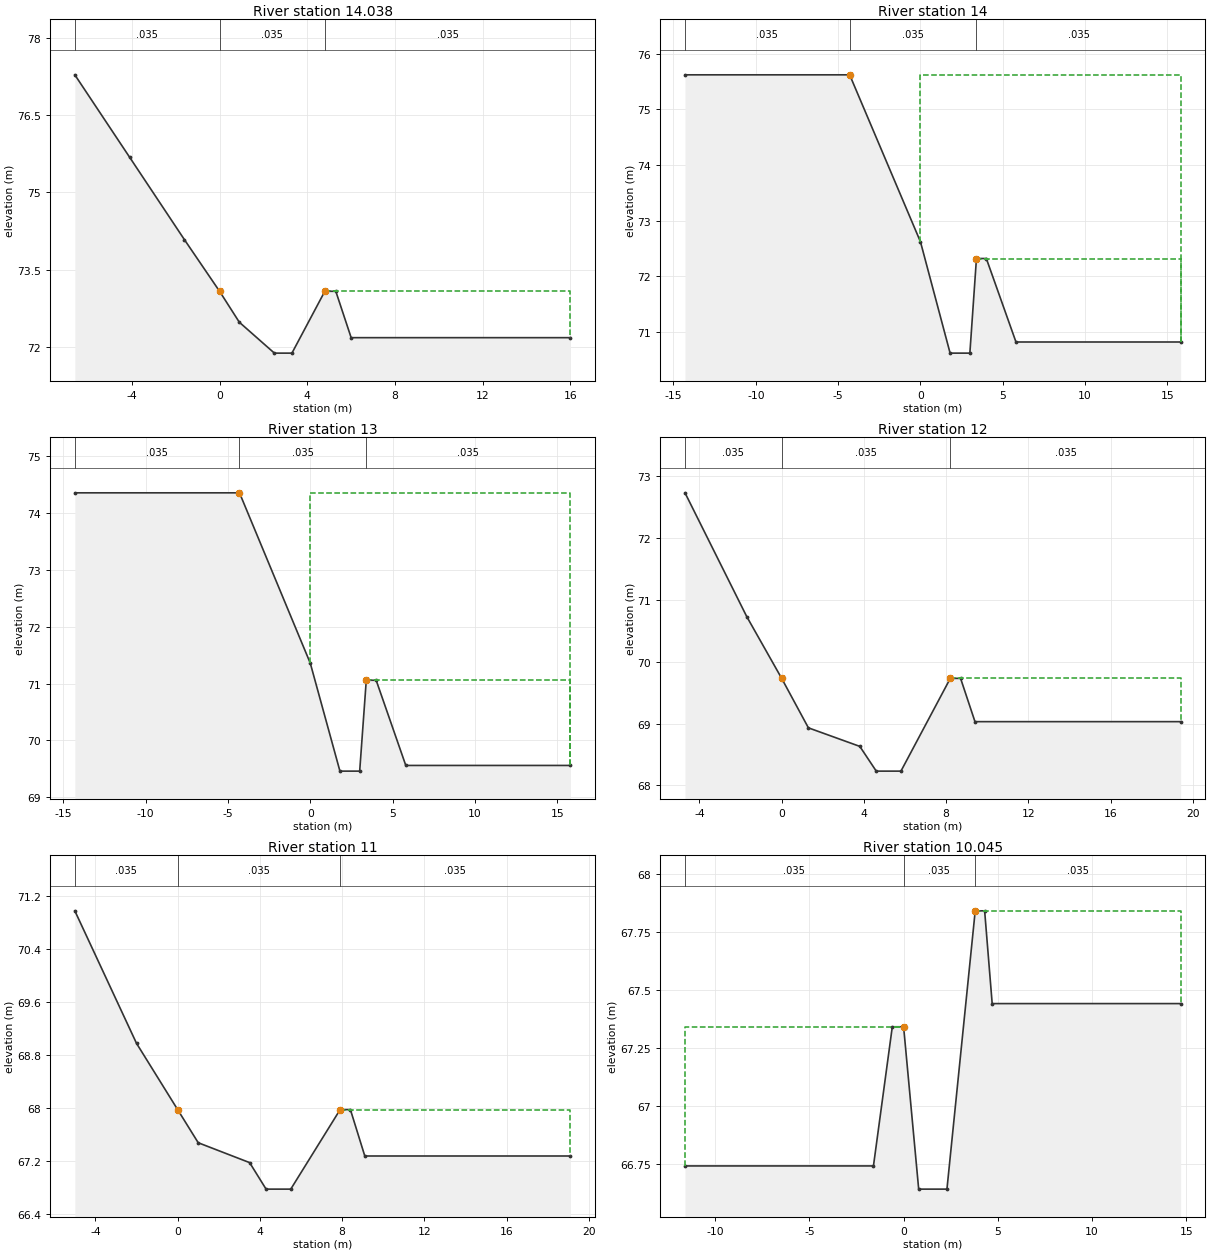
Type RM Length L Ch R = 1 ,14.038  ,38,38,38
#Sta/Elev= 11
    -6.6   77.28    -4.1   75.68    -1.6   74.08       0   73.08      .9   72.48
     2.5   71.88     3.3   71.88     4.8   73.08     5.3   73.08       6   72.18
      16   72.18
#Mann= 3 , 0 , 0
    -6.6    .035       0       0    .035       0     4.8    .035       0
#XS Ineff= 2 , 0
               0   73.08     4.8           73.08
Permanent Ineff=
       F       F
Bank Sta=0,4.8
XS Rating Curve= 0
Exp/Cntr=.3,.1

Type RM Length L Ch R = 1 ,14      ,50,50,50
#Sta/Elev= 9
   -14.3   75.62    -4.3   75.62       0   72.62     1.8   70.62       3   70.62
     3.4   72.32       4   72.32     5.8   70.82    15.8   70.82
#Mann= 3 , 0 , 0
   -14.3    .035       0    -4.3    .035       0     3.4    .035       0
#XS Ineff= 2 , 0
       0    -4.3   75.62     3.4       0   72.32
Permanent Ineff=
       F       F
Bank Sta=-4.3,3.4
XS Rating Curve= 0
Exp/Cntr=.3,.1

Type RM Length L Ch R = 1 ,13      ,50,50,50
#Sta/Elev= 9
   -14.3   74.36    -4.3   74.36       0   71.36     1.8   69.46       3   69.46
     3.4   71.06       4   71.06     5.8   69.56    15.8   69.56
#Mann= 3 , 0 , 0
   -14.3    .035       0    -4.3    .035       0     3.4    .035       0
#XS Ineff= 2 , 0
       0    -4.3   74.36     3.4       0   71.06
Permanent Ineff=
       F       F
Bank Sta=-4.3,3.4
XS Rating Curve= 0
Exp/Cntr=.3,.1

Type RM Length L Ch R = 1 ,12      ,50,50,50
#Sta/Elev= 11
    -4.7   72.73    -1.7   70.73       0   69.73     1.3   68.93     3.8   68.63
     4.6   68.23     5.8   68.23     8.2   69.73     8.7   69.73     9.4   69.03
    19.4   69.03
#Mann= 3 , 0 , 0
    -4.7    .035       0       0    .035       0     8.2    .035       0
#XS Ineff= 2 , 0
               0   69.73     8.2           69.73
Permanent Ineff=
       F       F
Bank Sta=0,8.2
XS Rating Curve= 0
Exp/Cntr=.3,.1

Type RM Length L Ch R = 1 ,11      ,5,5,5
#Sta/Elev= 11
      -5   70.97      -2   68.97       0   67.97       1   67.47     3.5   67.17
     4.3   66.77     5.5   66.77     7.9   67.97     8.4   67.97     9.1   67.27
    19.1   67.27
#Mann= 3 , 0 , 0
      -5    .035       0       0    .035       0     7.9    .035       0
#XS Ineff= 2 , 0
               0   67.97     7.9           67.97
Permanent Ineff=
       F       F
Bank Sta=0,7.9
XS Rating Curve= 0
Exp/Cntr=.3,.1

Type RM Length L Ch R = 1 ,10.045  ,1,1,1
#Sta/Elev= 10
   -11.6   66.74    -1.6   66.74     -.6   67.34       0   67.34      .8   66.64
     2.3   66.64     3.8   67.84     4.3   67.84     4.7   67.44    14.7   67.44
#Mann= 3 , 0 , 0
   -11.6    .035       0       0    .035       0     3.8    .035       0
#XS Ineff= 2 , 0
               0   67.34     3.8           67.84
Permanent Ineff=
       F       F
Bank Sta=0,3.8
XS Rating Curve= 0
Exp/Cntr=.3,.1

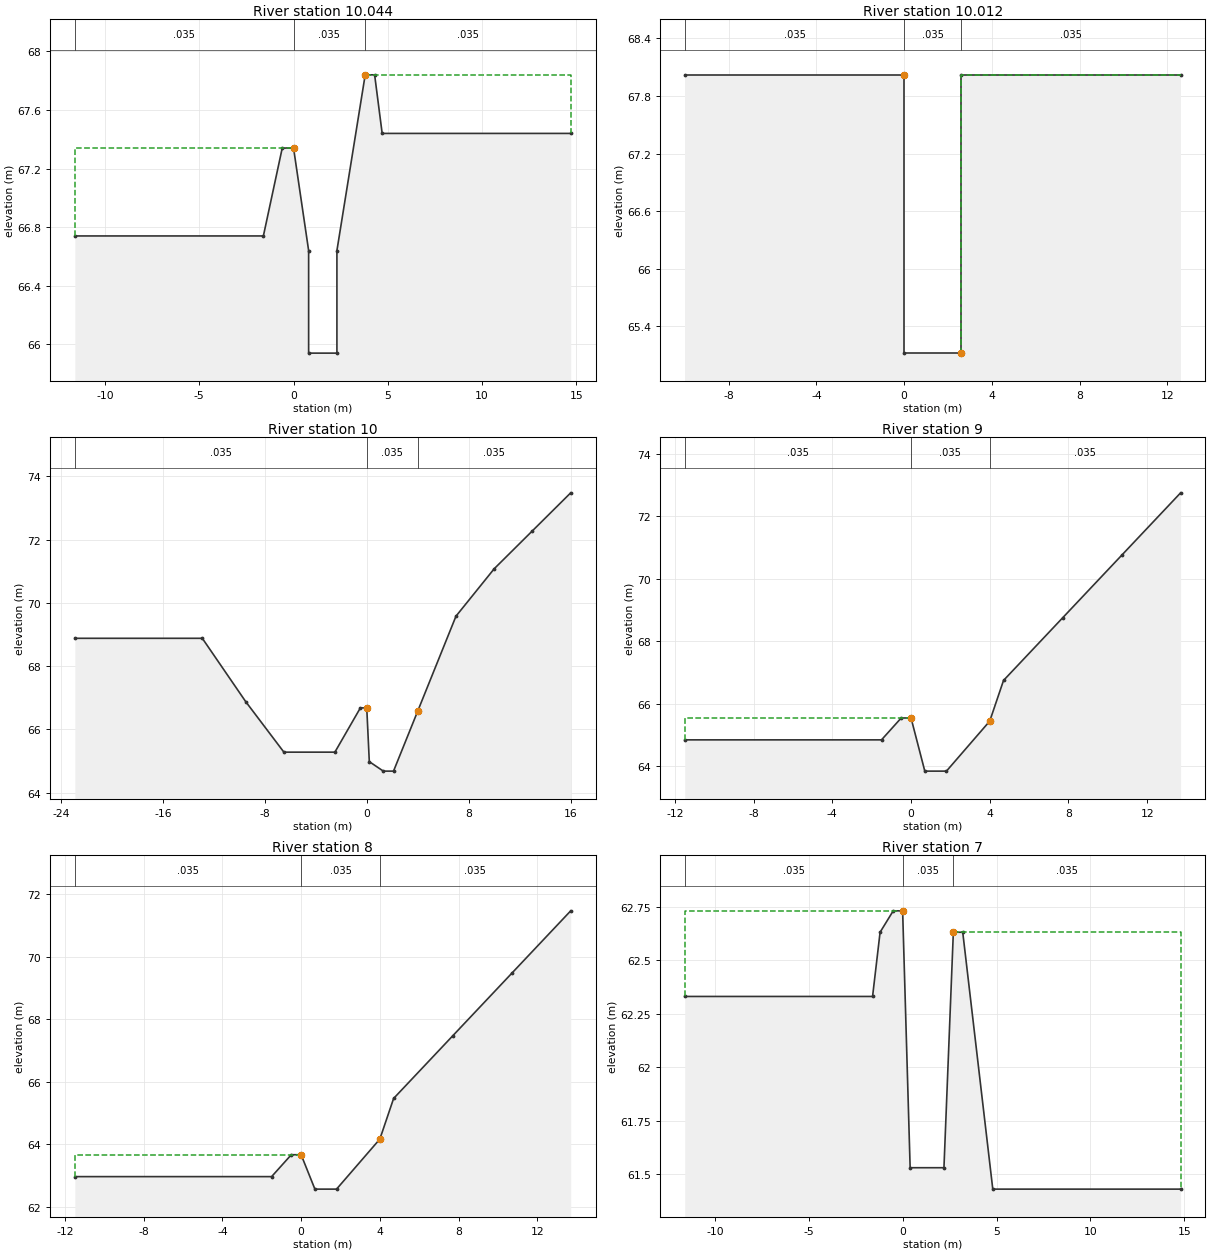
Type RM Length L Ch R = 1 ,10.044  ,32,32,32
#Sta/Elev= 12
   -11.6   66.74    -1.6   66.74     -.6   67.34       0   67.34      .8   66.64
      .8   65.94     2.3   65.94     2.3   66.64     3.8   67.84     4.3   67.84
     4.7   67.44    14.7   67.44
#Mann= 3 , 0 , 0
   -11.6    .035       0       0    .035       0     3.8    .035       0
#XS Ineff= 2 , 0
               0   67.34     3.8           67.84
Permanent Ineff=
       F       F
Bank Sta=0,3.8
XS Rating Curve= 0
Exp/Cntr=.3,.1

Type RM Length L Ch R = 1 ,10.012  ,12,12,12
#Sta/Elev= 6
     -10   68.02       0   68.02       0   65.12     2.6   65.12     2.6   68.02
    12.6   68.02
#Mann= 3 , 0 , 0
     -10    .035       0       0    .035       0     2.6    .035       0
#XS Ineff= 2 , 0
               0   68.02     2.6           68.02
Permanent Ineff=
       F       F
Bank Sta=0,2.6
XS Rating Curve= 0
Exp/Cntr=.3,.1

Type RM Length L Ch R = 1 ,10      ,50,50,50
#Sta/Elev= 15
   -22.9   68.88   -12.9   68.88    -9.5   66.88    -6.5   65.28    -2.5   65.28
     -.5   66.68       0   66.68      .2   64.98     1.3   64.68     2.1   64.68
       4   66.58       7   69.58      10   71.08      13   72.28      16   73.48
#Mann= 3 , 0 , 0
   -22.9    .035       0       0    .035       0       4    .035       0
#XS Ineff= 2 , 0
               0   66.68       4           66.58
Permanent Ineff=
       F       F
Bank Sta=0,4
XS Rating Curve= 0
Exp/Cntr=.3,.1

Type RM Length L Ch R = 1 ,9       ,50,50,50
#Sta/Elev= 11
   -11.5   64.85    -1.5   64.85     -.5   65.55       0   65.55      .7   63.85
     1.8   63.85       4   65.45     4.7   66.75     7.7   68.75    10.7   70.75
    13.7   72.75
#Mann= 3 , 0 , 0
   -11.5    .035       0       0    .035       0       4    .035       0
#XS Ineff= 2 , 0
               0   65.55       4           65.45
Permanent Ineff=
       F       F
Bank Sta=0,4
XS Rating Curve= 0
Exp/Cntr=.3,.1

Type RM Length L Ch R = 1 ,8       ,50,50,50
#Sta/Elev= 11
   -11.5   62.97    -1.5   62.97     -.5   63.67       0   63.67      .7   62.57
     1.8   62.57       4   64.17     4.7   65.47     7.7   67.47    10.7   69.47
    13.7   71.47
#Mann= 3 , 0 , 0
   -11.5    .035       0       0    .035       0       4    .035       0
#XS Ineff= 2 , 0
               0   63.67       4           64.17
Permanent Ineff=
       F       F
Bank Sta=0,4
XS Rating Curve= 0
Exp/Cntr=.3,.1

Type RM Length L Ch R = 1 ,7       ,17,17,17
#Sta/Elev= 11
   -11.6   62.33    -1.6   62.33    -1.2   62.63     -.5   62.73       0   62.73
      .4   61.53     2.2   61.53     2.7   62.63     3.2   62.63     4.8   61.43
    14.8   61.43
#Mann= 3 , 0 , 0
   -11.6    .035       0       0    .035       0     2.7    .035       0
#XS Ineff= 2 , 0
               0   62.73     2.7           62.63
Permanent Ineff=
       F       F
Bank Sta=0,2.7
XS Rating Curve= 0
Exp/Cntr=.3,.1

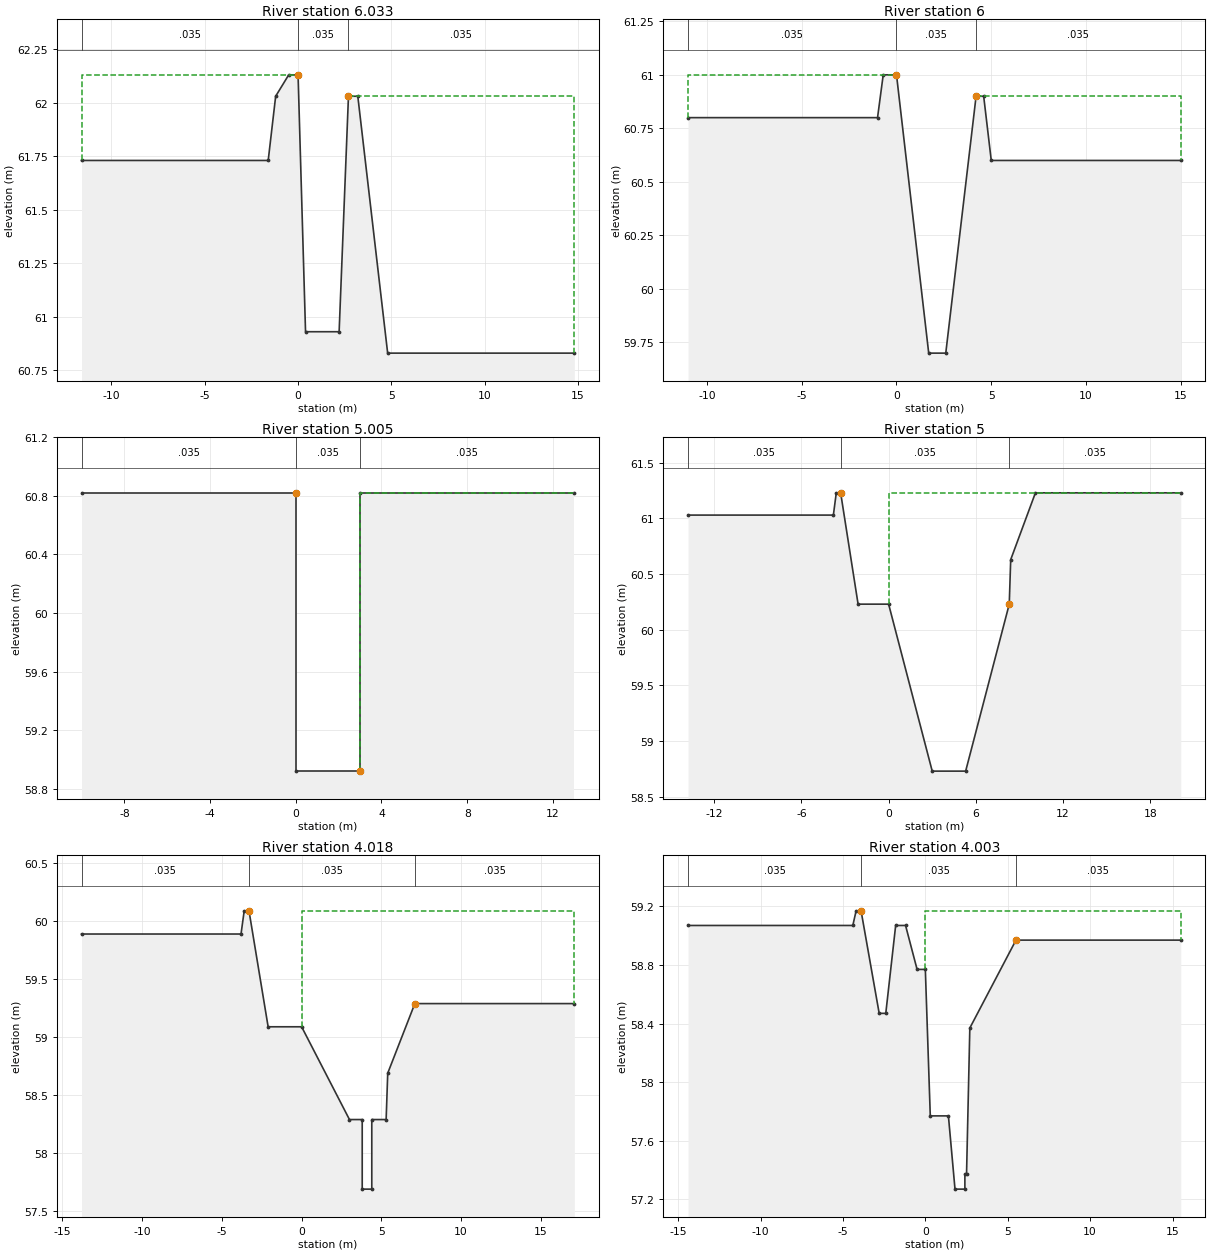
Type RM Length L Ch R = 1 ,6.033   ,33,33,33
#Sta/Elev= 11
   -11.6   61.73    -1.6   61.73    -1.2   62.03     -.5   62.13       0   62.13
      .4   60.93     2.2   60.93     2.7   62.03     3.2   62.03     4.8   60.83
    14.8   60.83
#Mann= 3 , 0 , 0
   -11.6    .035       0       0    .035       0     2.7    .035       0
#XS Ineff= 2 , 0
               0   62.13     2.7           62.03
Permanent Ineff=
       F       F
Bank Sta=0,2.7
XS Rating Curve= 0
Exp/Cntr=.3,.1

Type RM Length L Ch R = 1 ,6       ,45,45,45
#Sta/Elev= 10
     -11    60.8      -1    60.8     -.7      61       0      61     1.7    59.7
     2.6    59.7     4.2    60.9     4.6    60.9       5    60.6      15    60.6
#Mann= 3 , 0 , 0
     -11    .035       0       0    .035       0     4.2    .035       0
#XS Ineff= 2 , 0
               0      61     4.2            60.9
Permanent Ineff=
       F       F
Bank Sta=0,4.2
XS Rating Curve= 0
Exp/Cntr=.3,.1

Type RM Length L Ch R = 1 ,5.005   ,5,5,5
#Sta/Elev= 6
     -10   60.82       0   60.82       0   58.92       3   58.92       3   60.82
      13   60.82
#Mann= 3 , 0 , 0
     -10    .035       0       0    .035       0       3    .035       0
#XS Ineff= 2 , 0
               0   60.82       3           60.82
Permanent Ineff=
       F       F
Bank Sta=0,3
XS Rating Curve= 0
Exp/Cntr=.3,.1

Type RM Length L Ch R = 1 ,5       ,32,32,32
#Sta/Elev= 12
   -13.8   61.03    -3.8   61.03    -3.6   61.23    -3.3   61.23    -2.1   60.23
       0   60.23       3   58.73     5.3   58.73     8.3   60.23     8.4   60.63
    10.1   61.23    20.1   61.23
#Mann= 3 , 0 , 0
   -13.8    .035       0    -3.3    .035       0     8.3    .035       0
#XS Ineff= 2 , 0
       0    -3.3   61.23     8.3       0   60.23
Permanent Ineff=
       F       F
Bank Sta=-3.3,8.3
XS Rating Curve= 0
Exp/Cntr=.3,.1

Type RM Length L Ch R = 1 ,4.018   ,15,15,15
#Sta/Elev= 15
   -13.8   59.89    -3.8   59.89    -3.6   60.09    -3.3   60.09    -2.1   59.09
       0   59.09       3   58.29     3.8   58.29     3.8   57.69     4.4   57.69
     4.4   58.29     5.3   58.29     5.4   58.69     7.1   59.29    17.1   59.29
#Mann= 3 , 0 , 0
   -13.8    .035       0    -3.3    .035       0     7.1    .035       0
#XS Ineff= 2 , 0
       0    -3.3   60.09     7.1       0   59.29
Permanent Ineff=
       F       F
Bank Sta=-3.3,7.1
XS Rating Curve= 0
Exp/Cntr=.3,.1

Type RM Length L Ch R = 1 ,4.003   ,3,3,3
#Sta/Elev= 19
   -14.4   59.07    -4.4   59.07    -4.2   59.17    -3.9   59.17    -2.8   58.47
    -2.4   58.47    -1.8   59.07    -1.2   59.07     -.5   58.77       0   58.77
      .3   57.77     1.4   57.77     1.8   57.27     2.4   57.27     2.4   57.37
     2.5   57.37     2.7   58.37     5.5   58.97    15.5   58.97
#Mann= 3 , 0 , 0
   -14.4    .035       0    -3.9    .035       0     5.5    .035       0
#XS Ineff= 2 , 0
       0    -3.9   59.17     5.5       0   58.97
Permanent Ineff=
       F       F
Bank Sta=-3.9,5.5
XS Rating Curve= 0
Exp/Cntr=.3,.1

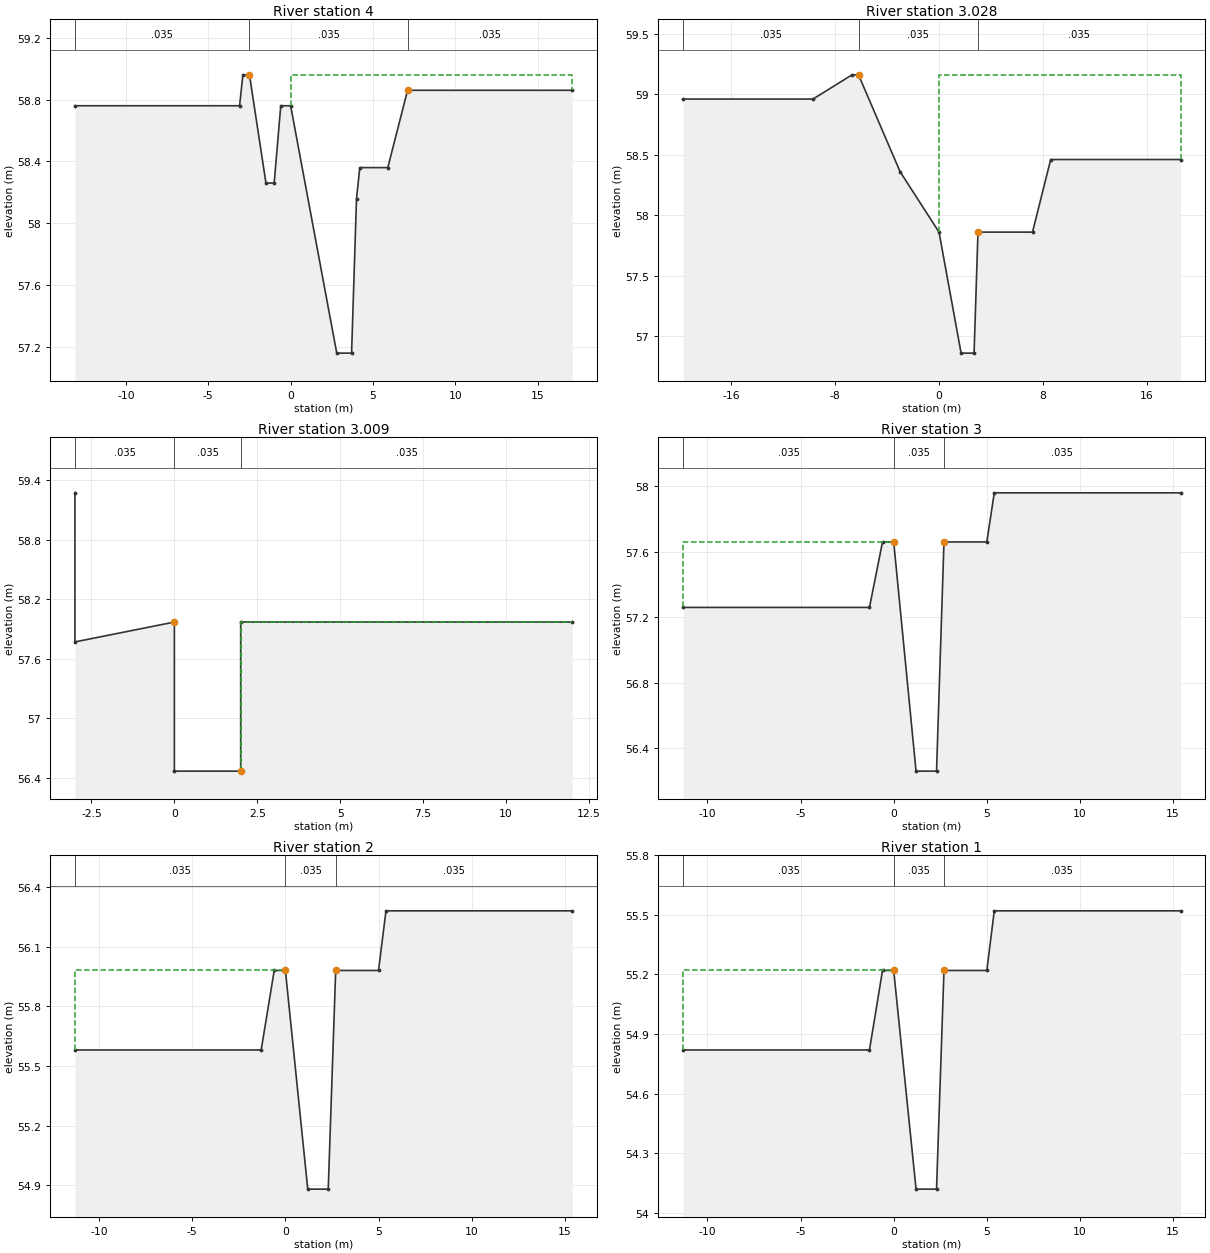
Type RM Length L Ch R = 1 ,4       ,22,22,22
#Sta/Elev= 15
   -13.1   58.76    -3.1   58.76    -2.9   58.96    -2.5   58.96    -1.5   58.26
      -1   58.26     -.6   58.76       0   58.76     2.8   57.16     3.7   57.16
       4   58.16     4.2   58.36     5.9   58.36     7.1   58.86    17.1   58.86
#Mann= 3 , 0 , 0
   -13.1    .035       0    -2.5    .035       0     7.1    .035       0
#XS Ineff= 2 , 0
       0    -2.5   58.96     7.1       0   58.86
Permanent Ineff=
       F       F
Bank Sta=-2.5,7.1
XS Rating Curve= 0
Exp/Cntr=.3,.1

Type RM Length L Ch R = 1 ,3.028   ,19,19,19
#Sta/Elev= 12
   -19.7   58.96    -9.7   58.96    -6.7   59.16    -6.2   59.16      -3   58.36
       0   57.86     1.7   56.86     2.7   56.86       3   57.86     7.2   57.86
     8.6   58.46    18.6   58.46
#Mann= 3 , 0 , 0
   -19.7    .035       0    -6.2    .035       0       3    .035       0
#XS Ineff= 2 , 0
       0    -6.2   59.16       3       0   57.86
Permanent Ineff=
       F       F
Bank Sta=-6.2,3
XS Rating Curve= 0
Exp/Cntr=.3,.1

Type RM Length L Ch R = 1 ,3.009   ,9,9,9
#Sta/Elev= 7
      -3   59.27      -3   57.77       0   57.97       0   56.47       2   56.47
       2   57.97      12   57.97
#Mann= 3 , 0 , 0
      -3    .035       0       0    .035       0       2    .035       0
#XS Ineff= 2 , 0
               0   57.97       2           57.97
Permanent Ineff=
       F       F
Bank Sta=0,2
XS Rating Curve= 0
Exp/Cntr=.3,.1

Type RM Length L Ch R = 1 ,3       ,50,50,50
#Sta/Elev= 10
   -11.3   57.26    -1.3   57.26     -.6   57.66       0   57.66     1.2   56.26
     2.3   56.26     2.7   57.66       5   57.66     5.4   57.96    15.4   57.96
#Mann= 3 , 0 , 0
   -11.3    .035       0       0    .035       0     2.7    .035       0
#XS Ineff= 2 , 0
               0   57.66     2.7           57.66
Permanent Ineff=
       F       F
Bank Sta=0,2.7
XS Rating Curve= 0
Exp/Cntr=.3,.1

Type RM Length L Ch R = 1 ,2       ,50,50,50
#Sta/Elev= 10
   -11.3   55.58    -1.3   55.58     -.6   55.98       0   55.98     1.2   54.88
     2.3   54.88     2.7   55.98       5   55.98     5.4   56.28    15.4   56.28
#Mann= 3 , 0 , 0
   -11.3    .035       0       0    .035       0     2.7    .035       0
#XS Ineff= 2 , 0
               0   55.98     2.7           55.98
Permanent Ineff=
       F       F
Bank Sta=0,2.7
XS Rating Curve= 0
Exp/Cntr=.3,.1

Type RM Length L Ch R = 1 ,1       ,38,38,38
#Sta/Elev= 10
   -11.3   54.82    -1.3   54.82     -.6   55.22       0   55.22     1.2   54.12
     2.3   54.12     2.7   55.22       5   55.22     5.4   55.52    15.4   55.52
#Mann= 3 , 0 , 0
   -11.3    .035       0       0    .035       0     2.7    .035       0
#XS Ineff= 2 , 0
               0   55.22     2.7           55.22
Permanent Ineff=
       F       F
Bank Sta=0,2.7
XS Rating Curve= 0
Exp/Cntr=.3,.1

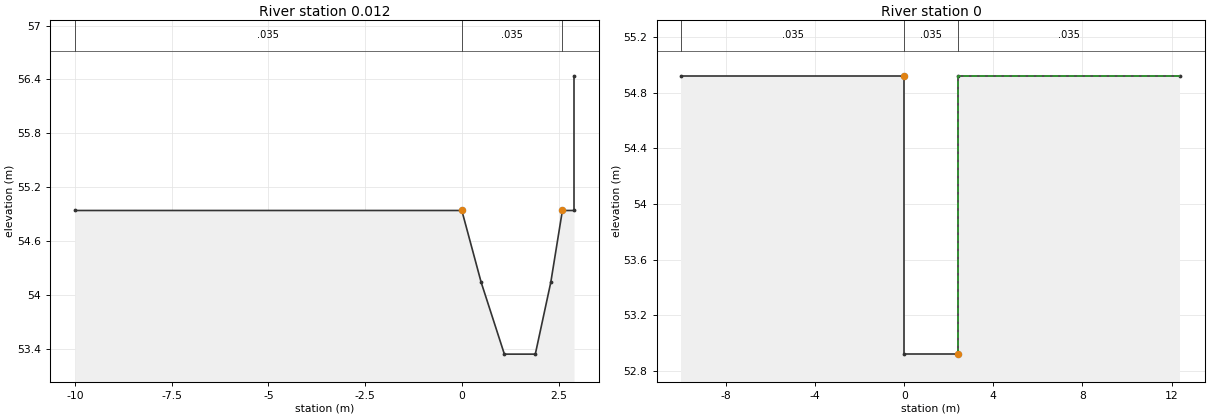
Type RM Length L Ch R = 1 ,0.012   ,12,12,12
#Sta/Elev= 9
     -10   54.94       0   54.94      .5   54.14     1.1   53.34     1.9   53.34
     2.3   54.14     2.6   54.94     2.9   54.94     2.9   56.44
#Mann= 3 , 0 , 0
     -10    .035       0       0    .035       0     2.6    .035       0
#XS Ineff= 2 , 0
               0   54.94     2.6           54.94
Permanent Ineff=
       F       F
Bank Sta=0,2.6
XS Rating Curve= 0
Exp/Cntr=.3,.1

Type RM Length L Ch R = 1 ,0       ,0,0,0
#Sta/Elev= 6
     -10   54.92       0   54.92       0   52.92     2.4   52.92     2.4   54.92
    12.4   54.92
#Mann= 3 , 0 , 0
     -10    .035       0       0    .035       0     2.4    .035       0
#XS Ineff= 2 , 0
               0   54.92     2.4           54.92
Permanent Ineff=
       F       F
Bank Sta=0,2.4
XS Rating Curve= 0
Exp/Cntr=.3,.1

Chan Stop Cuts=-1