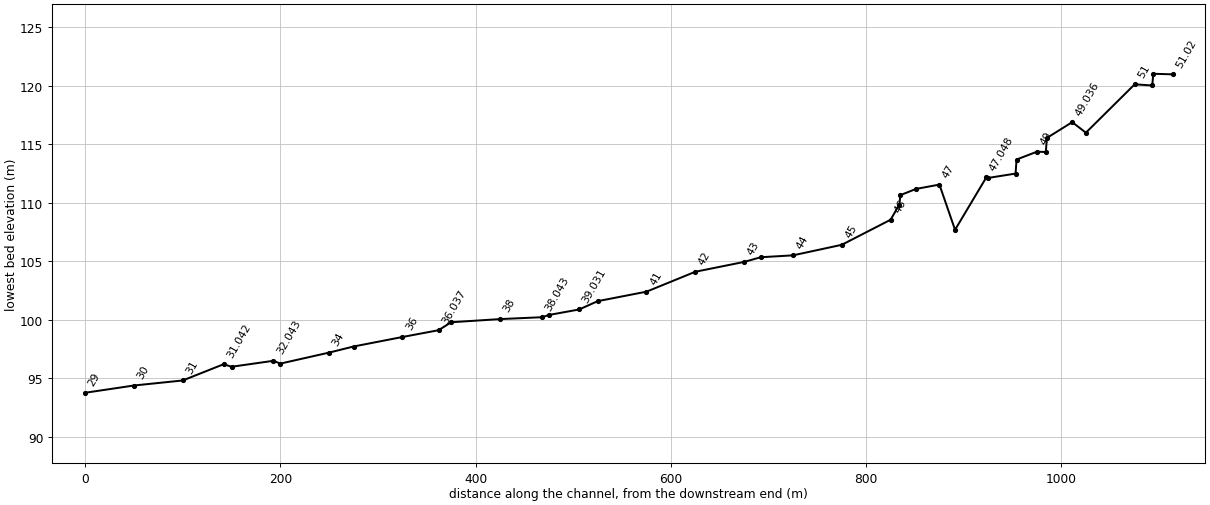
--- sinsan-ch.prj (project) ---

Proj Title=sinsan-ch
Current Plan=p01
Default Exp/Contr=.3,.1
SI Units
Geom File=g01
Flow File=f01
Plan File=p01
Y Axis Title=Elevation
X Axis Title(PF)=Main Channel Distance
X Axis Title(XS)=Station
BEGIN DESCRIPTION:
           BACK WATER COMPUTATION
      APPLICATION OF HEC-2 BY Samju Construction Engineering
      sinsan-ch: 10,20,30,50,80 yr
END DESCRIPTION:
DSS Export Rating Curves= 0
DSS Export Rating Curve Sorted= 0
DSS Export Volume Flow Curves= 0
DXF OffsetX= 0
DXF OffsetY= 0
DXF ScaleX= 1
DXF ScaleY= 10

--- sinsan-ch.p01 (plan) ---

Plan Title=Imported Plan 01
Version=Version 3.0.1  Mar 2001
Short Identifier=Imported Pla
Geom File=g01
Flow File=f01
Subcritical Flow
K Sum by GR= 0
Std Step Tol= 0.003
Critical Tol= 0.003
Num of Std Step Trials= 20
Max Error Tol= 0.1
Flow Tol Ratio= 0.001
Split Flow NTrial= 30
Split Flow Tol= 0.02
Split Flow Ratio= 0.02
Log Output Level= 0
Friction Slope Method= 1
Unsteady Friction Slope Method= 2
Parabolic Critical Depth
Global Vel Dist= 0 , 0 , 0
Global Log Level= 0
CheckData=True
Encroach Param=-1 ,0,0, 0
Computation Interval=1HOUR
Output Interval=1HOUR
Run HTab= 0
Run UNet= 0
Run PostProcess= 0
UNET Theta= 1
UNET ZTol= 0.02
UNET ZSATol= 0.1
UNET MxIter= 20
UNET MaxInSteps= 20
UNET DtIC= 0
UNET DtMin= 0
UNET MaxCRTS= 20
UNET WFStab= 2
UNET SFStab= 1
UNET WFX= 1
UNET SFX= 1
UNET Convert EG Bridges=-1
UNET Use Existing IB Tables=-1
Instantaneous Interval=1HOUR
Write IC File= 0
Write Velocity= 0
Write Detailed= 0

--- sinsan-ch.f01 (steady flow) ---

Flow Title=Imported Flow 01
Version=Version 3.0.1  Mar 2001
Number of Profiles= 5
Profile Names=PF 1,PF 2,PF 3,PF 4,PF 5
River Rch & RM=RIVER-1,Reach-1         ,51.02
     180     200     220     230     240
Boundary for River Rch & Prof#=RIVER-1,Reach-1         , 1
Up Type= 0
Dn Type= 3
Dn Slope=.0109
Boundary for River Rch & Prof#=RIVER-1,Reach-1         , 2
Up Type= 0
Dn Type= 3
Dn Slope=.0109
Boundary for River Rch & Prof#=RIVER-1,Reach-1         , 3
Up Type= 0
Dn Type= 3
Dn Slope=.0109
Boundary for River Rch & Prof#=RIVER-1,Reach-1         , 4
Up Type= 0
Dn Type= 3
Dn Slope=.0109
Boundary for River Rch & Prof#=RIVER-1,Reach-1         , 5
Up Type= 0
Dn Type= 3
Dn Slope=.0109
DSS Import GetInterval= 0
DSS Import GetPeak= 0
DSS Import FillOption= 0

--- sinsan-ch.g01 (geometry) ---

Geom Title=Imported Geom 01
Version=Version 3.0.1  Mar 2001

River Reach=RIVER-1         ,Reach-1
Reach XY= 2
              .5             .95              .5             .05

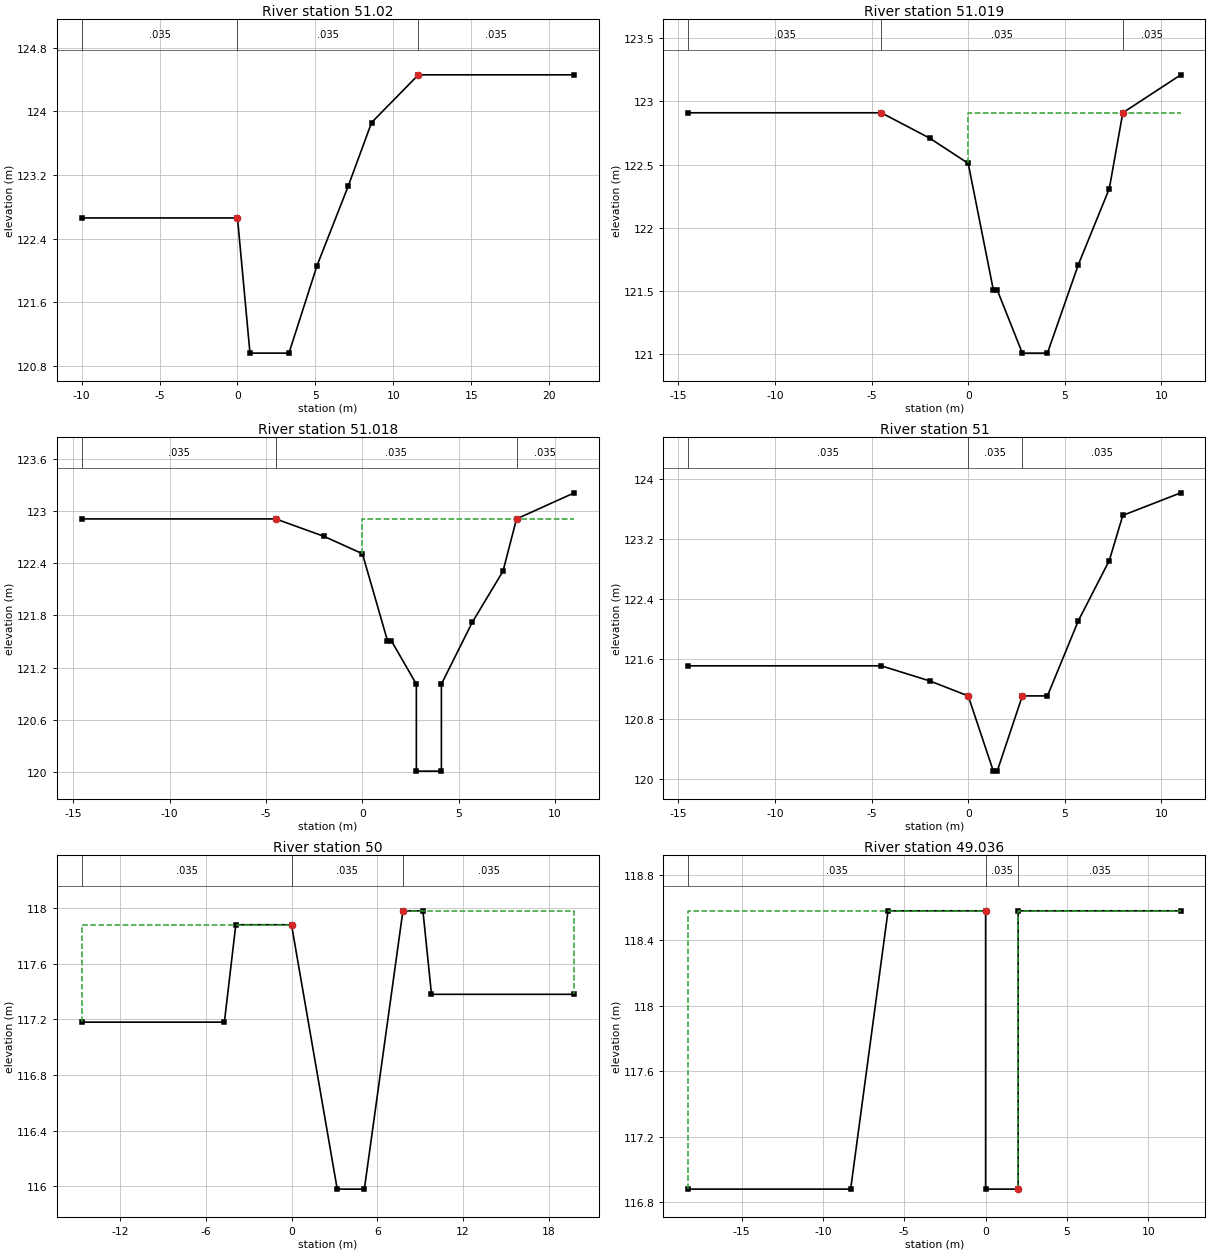
Type RM Length L Ch R = 1 ,51.02   ,20,20,20
#Sta/Elev= 9
     -10  122.66       0  122.66      .8  120.96     3.3  120.96     5.1  122.06
     7.1  123.06     8.6  123.86    11.6  124.46    21.6  124.46
#Mann= 3 , 0 , 0
     -10    .035       0       0    .035       0    11.6    .035       0
#XS Ineff= 2 , 0
               0  122.66    11.6          124.46
Permanent Ineff=
       F       F
Bank Sta=0,11.6
XS Rating Curve= 0
Exp/Cntr=.3,.1

Type RM Length L Ch R = 1 ,51.019  ,1,1,1
#Sta/Elev= 12
   -14.5  122.91    -4.5  122.91      -2  122.71       0  122.51     1.3  121.51
     1.5  121.51     2.8  121.01     4.1  121.01     5.7  121.71     7.3  122.31
       8  122.91      11  123.21
#Mann= 3 , 0 , 0
   -14.5    .035       0    -4.5    .035       0       8    .035       0
#XS Ineff= 2 , 0
       0    -4.5  122.91       8       0  122.91
Permanent Ineff=
       F       F
Bank Sta=-4.5,8
XS Rating Curve= 0
Exp/Cntr=.3,.1

Type RM Length L Ch R = 1 ,51.018  ,18,18,18
#Sta/Elev= 14
  -14.58  122.91    -4.5  122.91      -2  122.71       0  122.51     1.3  121.51
     1.5  121.51     2.8  121.01     2.8  120.01     4.1  120.01     4.1  121.01
     5.7  121.72     7.3  122.31       8  122.91      11  123.21
#Mann= 3 , 0 , 0
  -14.58    .035       0    -4.5    .035       0       8    .035       0
#XS Ineff= 2 , 0
       0    -4.5  122.91       8       0  122.91
Permanent Ineff=
       F       F
Bank Sta=-4.5,8
XS Rating Curve= 0
Exp/Cntr=.3,.1

Type RM Length L Ch R = 1 ,51      ,50,50,50
#Sta/Elev= 12
   -14.5  121.51    -4.5  121.51      -2  121.31       0  121.11     1.3  120.11
     1.5  120.11     2.8  121.11     4.1  121.11     5.7  122.11     7.3  122.91
       8  123.51      11  123.81
#Mann= 3 , 0 , 0
   -14.5    .035       0       0    .035       0     2.8    .035       0
#XS Ineff= 2 , 0
               0  121.11     2.8          121.11
Permanent Ineff=
       F       F
Bank Sta=0,2.8
XS Rating Curve= 0
Exp/Cntr=.3,.1

Type RM Length L Ch R = 1 ,50      ,14,14,14
#Sta/Elev= 10
   -14.7  117.18    -4.7  117.18    -3.9  117.88       0  117.88     3.2  115.98
     5.1  115.98     7.8  117.98     9.2  117.98     9.8  117.38    19.8  117.38
#Mann= 3 , 0 , 0
   -14.7    .035       0       0    .035       0     7.8    .035       0
#XS Ineff= 2 , 0
               0  117.88     7.8          117.98
Permanent Ineff=
       F       F
Bank Sta=0,7.8
XS Rating Curve= 0
Exp/Cntr=.3,.1

Type RM Length L Ch R = 1 ,49.036  ,26,26,26
#Sta/Elev= 8
   -18.3  116.88    -8.3  116.88      -6  118.58       0  118.58       0  116.88
       2  116.88       2  118.58      12  118.58
#Mann= 3 , 0 , 0
   -18.3    .035       0       0    .035       0       2    .035       0
#XS Ineff= 2 , 0
               0  118.58       2          118.58
Permanent Ineff=
       F       F
Bank Sta=0,2
XS Rating Curve= 0
Exp/Cntr=.3,.1

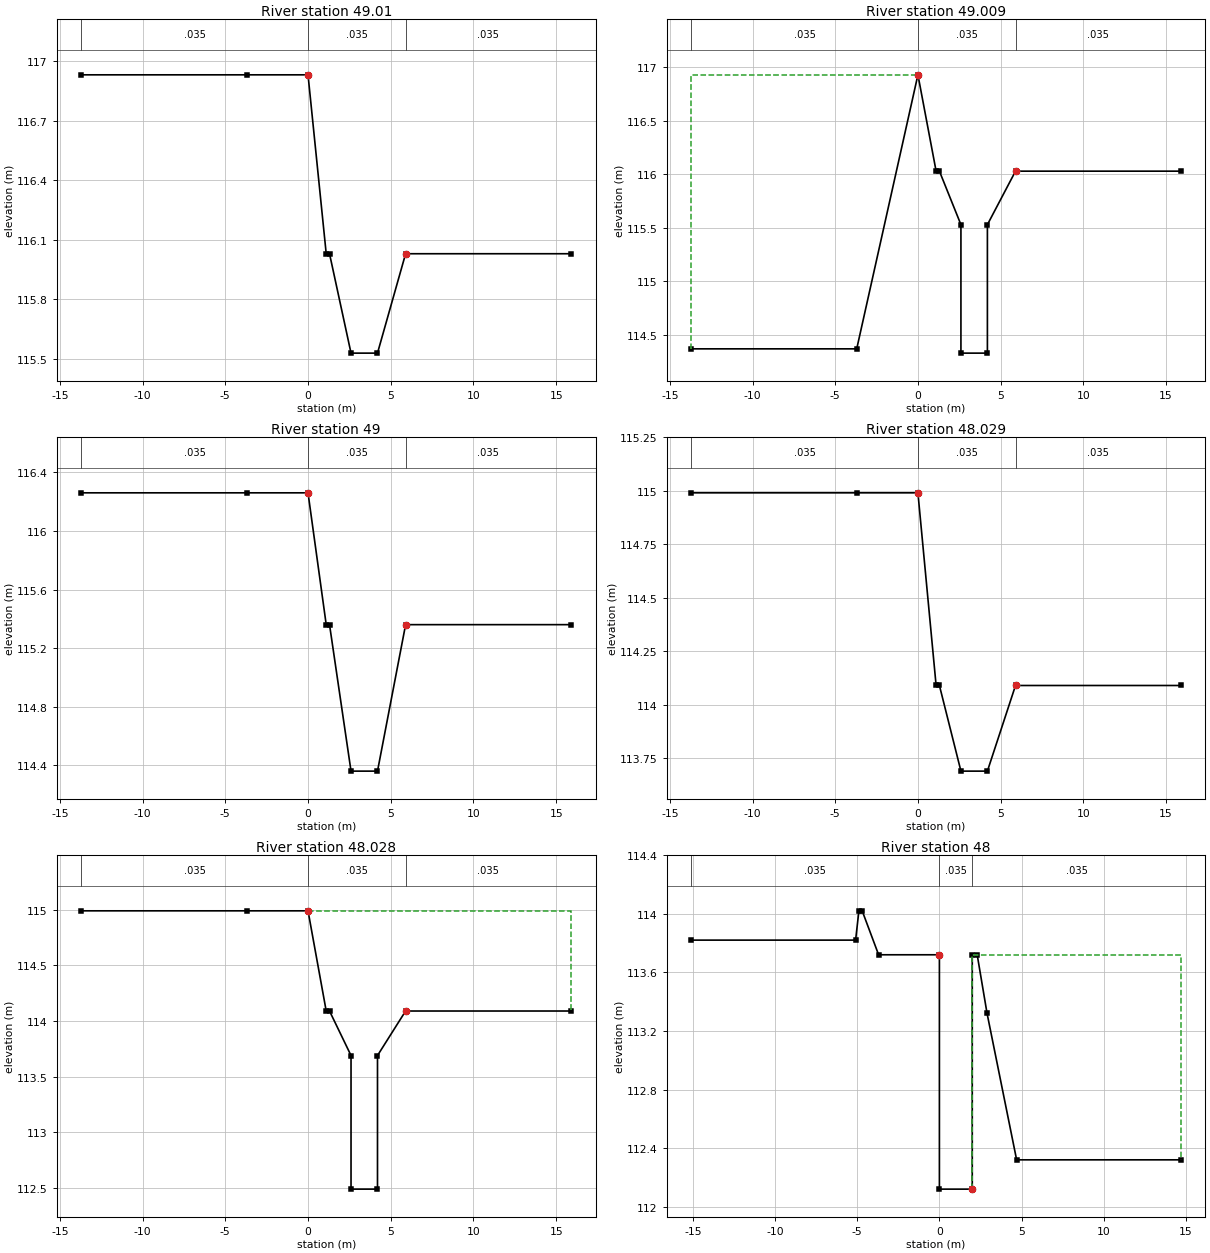
Type RM Length L Ch R = 1 ,49.01   ,1,1,1
#Sta/Elev= 9
   -13.7  116.93    -3.7  116.93       0  116.93     1.1  116.03     1.3  116.03
     2.6  115.53     4.2  115.53     5.9  116.03    15.9  116.03
#Mann= 3 , 0 , 0
   -13.7    .035       0       0    .035       0     5.9    .035       0
#XS Ineff= 2 , 0
               0  116.93     5.9          116.03
Permanent Ineff=
       F       F
Bank Sta=0,5.9
XS Rating Curve= 0
Exp/Cntr=.3,.1

Type RM Length L Ch R = 1 ,49.009  ,9,9,9
#Sta/Elev= 11
   -13.7  114.37    -3.7  114.37       0  116.93     1.1  116.03     1.3  116.03
     2.6  115.53     2.6  114.33     4.2  114.33     4.2  115.53     5.9  116.03
    15.9  116.03
#Mann= 3 , 0 , 0
   -13.7    .035       0       0    .035       0     5.9    .035       0
#XS Ineff= 2 , 0
               0  116.93     5.9          116.03
Permanent Ineff=
       F       F
Bank Sta=0,5.9
XS Rating Curve= 0
Exp/Cntr=.3,.1

Type RM Length L Ch R = 1 ,49      ,21,21,21
#Sta/Elev= 9
   -13.7  116.26    -3.7  116.26       0  116.26     1.1  115.36     1.3  115.36
     2.6  114.36     4.2  114.36     5.9  115.36    15.9  115.36
#Mann= 3 , 0 , 0
   -13.7    .035       0       0    .035       0     5.9    .035       0
#XS Ineff= 2 , 0
               0  116.26     5.9          115.36
Permanent Ineff=
       F       F
Bank Sta=0,5.9
XS Rating Curve= 0
Exp/Cntr=.3,.1

Type RM Length L Ch R = 1 ,48.029  ,1,1,1
#Sta/Elev= 9
   -13.7  114.99    -3.7  114.99       0  114.99     1.1  114.09     1.3  114.09
     2.6  113.69     4.2  113.69     5.9  114.09    15.9  114.09
#Mann= 3 , 0 , 0
   -13.7    .035       0       0    .035       0     5.9    .035       0
#XS Ineff= 2 , 0
               0  114.99     5.9          114.09
Permanent Ineff=
       F       F
Bank Sta=0,5.9
XS Rating Curve= 0
Exp/Cntr=.3,.1

Type RM Length L Ch R = 1 ,48.028  ,28,28,28
#Sta/Elev= 11
   -13.7  114.99    -3.7  114.99       0  114.99     1.1  114.09     1.3  114.09
     2.6  113.69     2.6  112.49     4.2  112.49     4.2  113.69     5.9  114.09
    15.9  114.09
#Mann= 3 , 0 , 0
   -13.7    .035       0       0    .035       0     5.9    .035       0
#XS Ineff= 2 , 0
       0       0  114.99     5.9       0  114.09
Permanent Ineff=
       F       F
Bank Sta=0,5.9
XS Rating Curve= 0
Exp/Cntr=.3,.1

Type RM Length L Ch R = 1 ,48      ,2,2,2
#Sta/Elev= 13
   -15.1  113.82    -5.1  113.82    -4.9  114.02    -4.7  114.02    -3.7  113.72
       0  113.72       0  112.12       2  112.12       2  113.72     2.3  113.72
     2.9  113.32     4.7  112.32    14.7  112.32
#Mann= 3 , 0 , 0
   -15.1    .035       0       0    .035       0       2    .035       0
#XS Ineff= 2 , 0
               0  113.72       2          113.72
Permanent Ineff=
       F       F
Bank Sta=0,2
XS Rating Curve= 0
Exp/Cntr=.3,.1

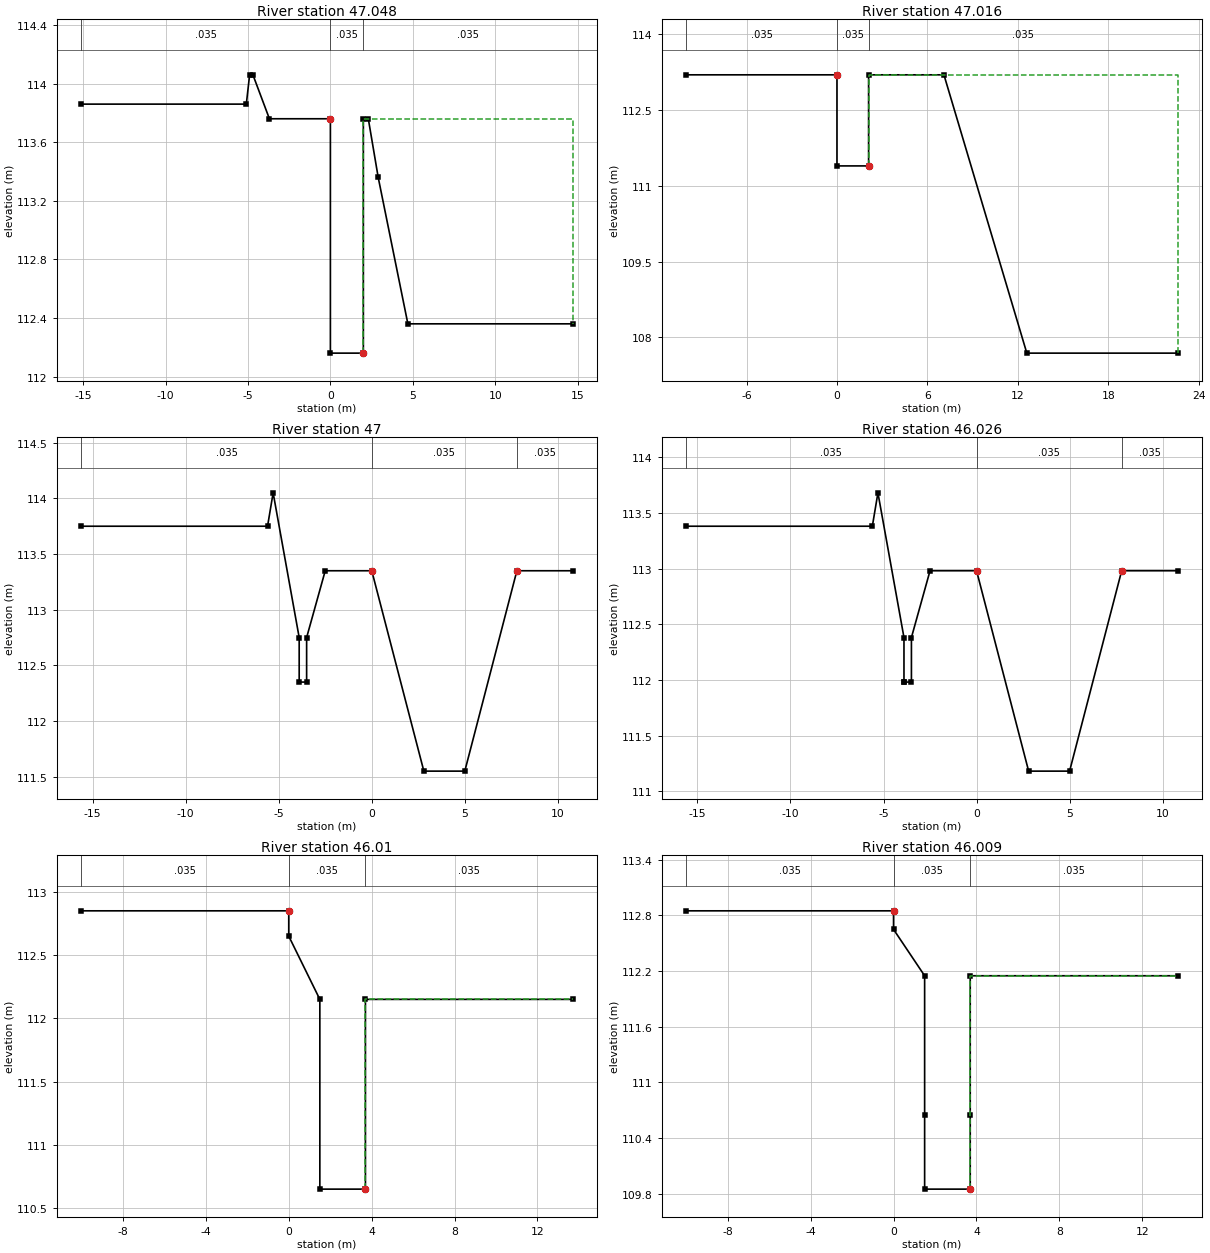
Type RM Length L Ch R = 1 ,47.048  ,32,32,32
#Sta/Elev= 13
   -15.1  113.86    -5.1  113.86    -4.9  114.06    -4.7  114.06    -3.7  113.76
       0  113.76       0  112.16       2  112.16       2  113.76     2.3  113.76
     2.9  113.36     4.7  112.36    14.7  112.36
#Mann= 3 , 0 , 0
   -15.1    .035       0       0    .035       0       2    .035       0
#XS Ineff= 2 , 0
               0  113.76       2          113.76
Permanent Ineff=
       F       F
Bank Sta=0,2
XS Rating Curve= 0
Exp/Cntr=.3,.1

Type RM Length L Ch R = 1 ,47.016  ,16,16,16
#Sta/Elev= 8
     -10  113.19       0  113.19       0  111.39     2.1  111.39     2.1  113.19
     7.1  113.19    12.6  107.69    22.6  107.69
#Mann= 3 , 0 , 0
     -10    .035       0       0    .035       0     2.1    .035       0
#XS Ineff= 2 , 0
               0  113.19     2.1          113.19
Permanent Ineff=
       F       F
Bank Sta=0,2.1
XS Rating Curve= 0
Exp/Cntr=.3,.1

Type RM Length L Ch R = 1 ,47      ,24,24,24
#Sta/Elev= 13
   -15.6  113.75    -5.6  113.75    -5.3  114.05    -3.9  112.75    -3.9  112.35
    -3.5  112.35    -3.5  112.75    -2.5  113.35       0  113.35     2.8  111.55
       5  111.55     7.8  113.35    10.8  113.35
#Mann= 3 , 0 , 0
   -15.6    .035       0       0    .035       0     7.8    .035       0
#XS Ineff= 2 , 0
               0  113.35     7.8          113.35
Permanent Ineff=
       F       F
Bank Sta=0,7.8
XS Rating Curve= 0
Exp/Cntr=.3,.1

Type RM Length L Ch R = 1 ,46.026  ,16,16,16
#Sta/Elev= 14
   -15.6  113.38    -5.6  113.38    -5.3  113.68    -3.9  112.38    -3.9  111.98
    -3.9  111.98    -3.5  111.98    -3.5  112.38    -2.5  112.98       0  112.98
     2.8  111.18       5  111.18     7.8  112.98    10.8  112.98
#Mann= 3 , 0 , 0
   -15.6    .035       0       0    .035       0     7.8    .035       0
#XS Ineff= 2 , 0
               0  112.98     7.8          112.98
Permanent Ineff=
       F       F
Bank Sta=0,7.8
XS Rating Curve= 0
Exp/Cntr=.3,.1

Type RM Length L Ch R = 1 ,46.01   ,1,1,1
#Sta/Elev= 8
     -10  112.85       0  112.85       0  112.65     1.5  112.15     1.5  110.65
     3.7  110.65     3.7  112.15    13.7  112.15
#Mann= 3 , 0 , 0
     -10    .035       0       0    .035       0     3.7    .035       0
#XS Ineff= 2 , 0
               0  112.85     3.7          112.15
Permanent Ineff=
       F       F
Bank Sta=0,3.7
XS Rating Curve= 0
Exp/Cntr=.3,.1

Type RM Length L Ch R = 1 ,46.009  ,9,9,9
#Sta/Elev= 10
     -10  112.85       0  112.85       0  112.65     1.5  112.15     1.5  110.65
     1.5  109.85     3.7  109.85     3.7  110.65     3.7  112.15    13.7  112.15
#Mann= 3 , 0 , 0
     -10    .035       0       0    .035       0     3.7    .035       0
#XS Ineff= 2 , 0
               0  112.85     3.7          112.15
Permanent Ineff=
       F       F
Bank Sta=0,3.7
XS Rating Curve= 0
Exp/Cntr=.3,.1

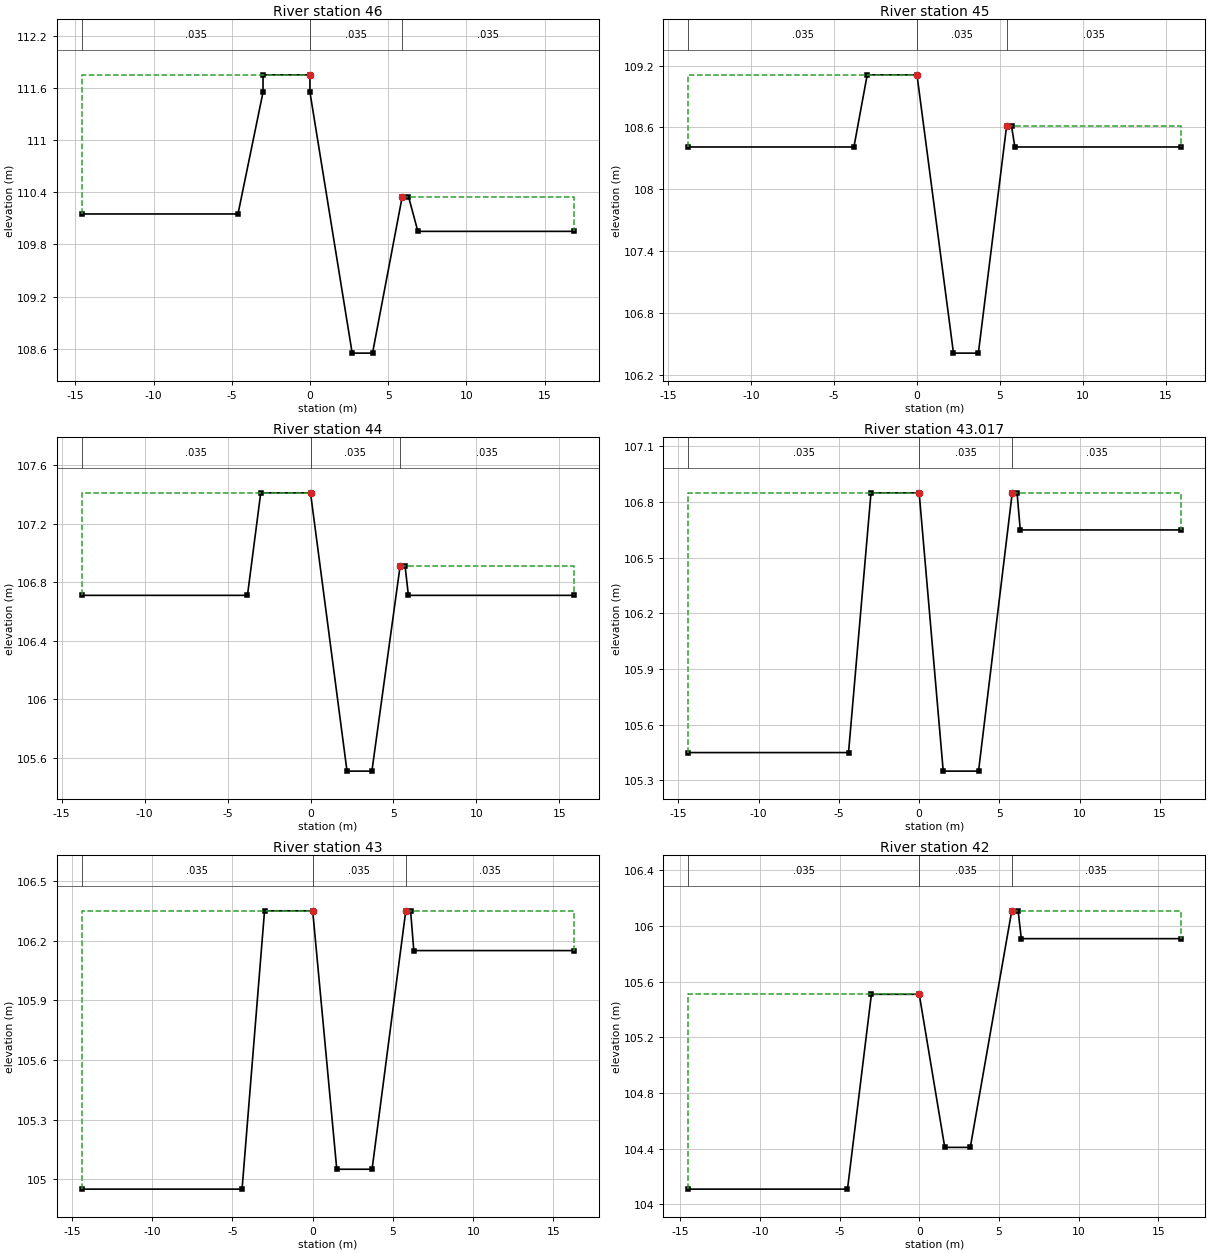
Type RM Length L Ch R = 1 ,46      ,50,50,50
#Sta/Elev= 12
   -14.6  110.15    -4.6  110.15      -3  111.55      -3  111.75       0  111.75
       0  111.55     2.7  108.55       4  108.55     5.9  110.35     6.3  110.35
     6.9  109.95    16.9  109.95
#Mann= 3 , 0 , 0
   -14.6    .035       0       0    .035       0     5.9    .035       0
#XS Ineff= 2 , 0
               0  111.75     5.9          110.35
Permanent Ineff=
       F       F
Bank Sta=0,5.9
XS Rating Curve= 0
Exp/Cntr=.3,.1

Type RM Length L Ch R = 1 ,45      ,50,50,50
#Sta/Elev= 10
   -13.8  108.41    -3.8  108.41      -3  109.11       0  109.11     2.2  106.41
     3.7  106.41     5.4  108.61     5.7  108.61     5.9  108.41    15.9  108.41
#Mann= 3 , 0 , 0
   -13.8    .035       0       0    .035       0     5.4    .035       0
#XS Ineff= 2 , 0
               0  109.11     5.4          108.61
Permanent Ineff=
       F       F
Bank Sta=0,5.4
XS Rating Curve= 0
Exp/Cntr=.3,.1

Type RM Length L Ch R = 1 ,44      ,33,33,33
#Sta/Elev= 10
   -13.8  106.71    -3.8  106.71      -3  107.41       0  107.41     2.2  105.51
     3.7  105.51     5.4  106.91     5.7  106.91     5.9  106.71    15.9  106.71
#Mann= 3 , 0 , 0
   -13.8    .035       0       0    .035       0     5.4    .035       0
#XS Ineff= 2 , 0
               0  107.41     5.4          106.91
Permanent Ineff=
       F       F
Bank Sta=0,5.4
XS Rating Curve= 0
Exp/Cntr=.3,.1

Type RM Length L Ch R = 1 ,43.017  ,17,17,17
#Sta/Elev= 10
   -14.4  105.45    -4.4  105.45      -3  106.85       0  106.85     1.5  105.35
     3.7  105.35     5.8  106.85     6.1  106.85     6.3  106.65    16.3  106.65
#Mann= 3 , 0 , 0
   -14.4    .035       0       0    .035       0     5.8    .035       0
#XS Ineff= 2 , 0
               0  106.85     5.8          106.85
Permanent Ineff=
       F       F
Bank Sta=0,5.8
XS Rating Curve= 0
Exp/Cntr=.3,.1

Type RM Length L Ch R = 1 ,43      ,50,50,50
#Sta/Elev= 10
   -14.4  104.95    -4.4  104.95      -3  106.35       0  106.35     1.5  105.05
     3.7  105.05     5.8  106.35     6.1  106.35     6.3  106.15    16.3  106.15
#Mann= 3 , 0 , 0
   -14.4    .035       0       0    .035       0     5.8    .035       0
#XS Ineff= 2 , 0
               0  106.35     5.8          106.35
Permanent Ineff=
       F       F
Bank Sta=0,5.8
XS Rating Curve= 0
Exp/Cntr=.3,.1

Type RM Length L Ch R = 1 ,42      ,50,50,50
#Sta/Elev= 10
   -14.5  104.11    -4.5  104.11      -3  105.51       0  105.51     1.6  104.41
     3.2  104.41     5.8  106.11     6.2  106.11     6.4  105.91    16.4  105.91
#Mann= 3 , 0 , 0
   -14.5    .035       0       0    .035       0     5.8    .035       0
#XS Ineff= 2 , 0
               0  105.51     5.8          106.11
Permanent Ineff=
       F       F
Bank Sta=0,5.8
XS Rating Curve= 0
Exp/Cntr=.3,.1

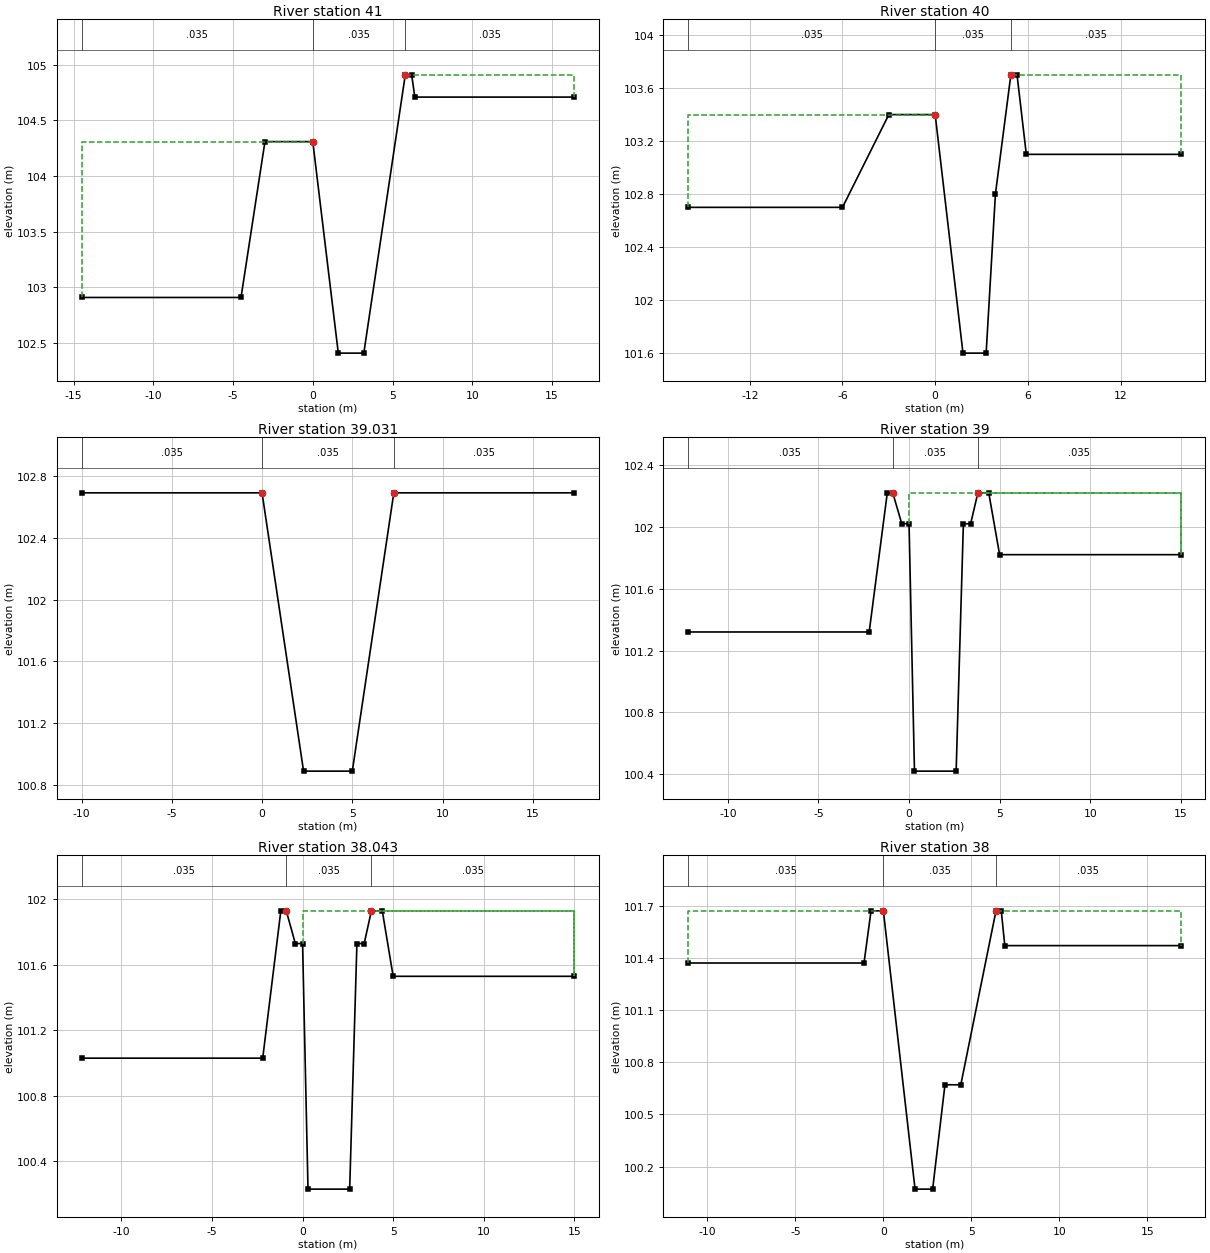
Type RM Length L Ch R = 1 ,41      ,50,50,50
#Sta/Elev= 10
   -14.5  102.91    -4.5  102.91      -3  104.31       0  104.31     1.6  102.41
     3.2  102.41     5.8  104.91     6.2  104.91     6.4  104.71    16.4  104.71
#Mann= 3 , 0 , 0
   -14.5    .035       0       0    .035       0     5.8    .035       0
#XS Ineff= 2 , 0
               0  104.31     5.8          104.91
Permanent Ineff=
       F       F
Bank Sta=0,5.8
XS Rating Curve= 0
Exp/Cntr=.3,.1

Type RM Length L Ch R = 1 ,40      ,19,19,19
#Sta/Elev= 11
     -16   102.7      -6   102.7      -3   103.4       0   103.4     1.8   101.6
     3.3   101.6     3.9   102.8     4.9   103.7     5.3   103.7     5.9   103.1
    15.9   103.1
#Mann= 3 , 0 , 0
     -16    .035       0       0    .035       0     4.9    .035       0
#XS Ineff= 2 , 0
               0   103.4     4.9           103.7
Permanent Ineff=
       F       F
Bank Sta=0,4.9
XS Rating Curve= 0
Exp/Cntr=.3,.1

Type RM Length L Ch R = 1 ,39.031  ,31,31,31
#Sta/Elev= 6
     -10  102.69       0  102.69     2.3  100.89       5  100.89     7.3  102.69
    17.3  102.69
#Mann= 3 , 0 , 0
     -10    .035       0       0    .035       0     7.3    .035       0
#XS Ineff= 2 , 0
               0  102.69     7.3          102.69
Permanent Ineff=
       F       F
Bank Sta=0,7.3
XS Rating Curve= 0
Exp/Cntr=.3,.1

Type RM Length L Ch R = 1 ,39      ,7,7,7
#Sta/Elev= 14
   -12.2  101.32    -2.2  101.32    -1.2  102.22     -.9  102.22     -.4  102.02
       0  102.02      .3  100.42     2.6  100.42       3  102.02     3.4  102.02
     3.8  102.22     4.4  102.22       5  101.82      15  101.82
#Mann= 3 , 0 , 0
   -12.2    .035       0     -.9    .035       0     3.8    .035       0
#XS Ineff= 2 , 0
       0     -.9  102.22     3.8       0  102.22
Permanent Ineff=
       F       F
Bank Sta=-.9,3.8
XS Rating Curve= 0
Exp/Cntr=.3,.1

Type RM Length L Ch R = 1 ,38.043  ,43,43,43
#Sta/Elev= 14
   -12.2  101.03    -2.2  101.03    -1.2  101.93     -.9  101.93     -.4  101.73
       0  101.73      .3  100.23     2.6  100.23       3  101.73     3.4  101.73
     3.8  101.93     4.4  101.93       5  101.53      15  101.53
#Mann= 3 , 0 , 0
   -12.2    .035       0     -.9    .035       0     3.8    .035       0
#XS Ineff= 2 , 0
       0     -.9  101.93     3.8       0  101.93
Permanent Ineff=
       F       F
Bank Sta=-.9,3.8
XS Rating Curve= 0
Exp/Cntr=.3,.1

Type RM Length L Ch R = 1 ,38      ,50,50,50
#Sta/Elev= 12
   -11.1  101.37    -1.1  101.37     -.7  101.67       0  101.67     1.8  100.07
     2.8  100.07     3.5  100.67     4.4  100.67     6.4  101.67     6.7  101.67
     6.9  101.47    16.9  101.47
#Mann= 3 , 0 , 0
   -11.1    .035       0       0    .035       0     6.4    .035       0
#XS Ineff= 2 , 0
               0  101.67     6.4          101.67
Permanent Ineff=
       F       F
Bank Sta=0,6.4
XS Rating Curve= 0
Exp/Cntr=.3,.1

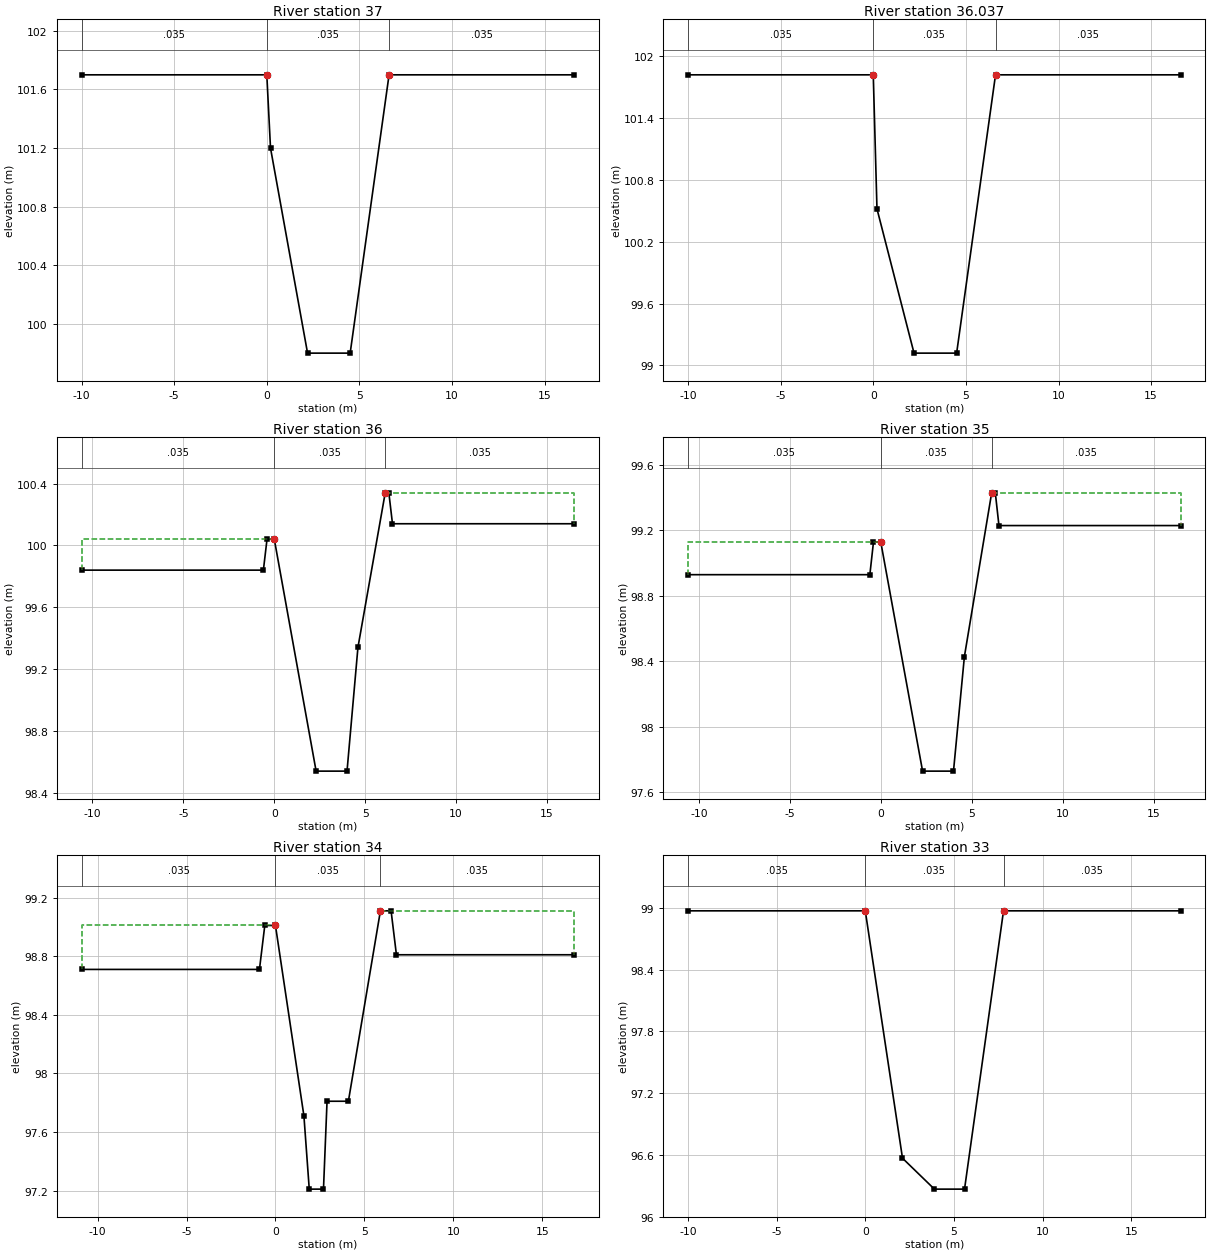
Type RM Length L Ch R = 1 ,37      ,13,13,13
#Sta/Elev= 7
     -10   101.7       0   101.7      .2   101.2     2.2    99.8     4.5    99.8
     6.6   101.7    16.6   101.7
#Mann= 3 , 0 , 0
     -10    .035       0       0    .035       0     6.6    .035       0
#XS Ineff= 2 , 0
               0   101.7     6.6           101.7
Permanent Ineff=
       F       F
Bank Sta=0,6.6
XS Rating Curve= 0
Exp/Cntr=.3,.1

Type RM Length L Ch R = 1 ,36.037  ,37,37,37
#Sta/Elev= 7
     -10  101.82       0  101.82      .2  100.52     2.2   99.12     4.5   99.12
     6.6  101.82    16.6  101.82
#Mann= 3 , 0 , 0
     -10    .035       0       0    .035       0     6.6    .035       0
#XS Ineff= 2 , 0
               0  101.82     6.6          101.82
Permanent Ineff=
       F       F
Bank Sta=0,6.6
XS Rating Curve= 0
Exp/Cntr=.3,.1

Type RM Length L Ch R = 1 ,36      ,50,50,50
#Sta/Elev= 11
   -10.6   99.84     -.6   99.84     -.4  100.04       0  100.04     2.3   98.54
       4   98.54     4.6   99.34     6.1  100.34     6.3  100.34     6.5  100.14
    16.5  100.14
#Mann= 3 , 0 , 0
   -10.6    .035       0       0    .035       0     6.1    .035       0
#XS Ineff= 2 , 0
               0  100.04     6.1          100.34
Permanent Ineff=
       F       F
Bank Sta=0,6.1
XS Rating Curve= 0
Exp/Cntr=.3,.1

Type RM Length L Ch R = 1 ,35      ,25,25,25
#Sta/Elev= 11
   -10.6   98.93     -.6   98.93     -.4   99.13       0   99.13     2.3   97.73
       4   97.73     4.6   98.43     6.1   99.43     6.3   99.43     6.5   99.23
    16.5   99.23
#Mann= 3 , 0 , 0
   -10.6    .035       0       0    .035       0     6.1    .035       0
#XS Ineff= 2 , 0
               0   99.13     6.1           99.43
Permanent Ineff=
       F       F
Bank Sta=0,6.1
XS Rating Curve= 0
Exp/Cntr=.3,.1

Type RM Length L Ch R = 1 ,34      ,50,50,50
#Sta/Elev= 13
   -10.9   98.71     -.9   98.71     -.6   99.01       0   99.01     1.6   97.71
     1.9   97.21     2.7   97.21     2.9   97.81     4.1   97.81     5.9   99.11
     6.5   99.11     6.8   98.81    16.8   98.81
#Mann= 3 , 0 , 0
   -10.9    .035       0       0    .035       0     5.9    .035       0
#XS Ineff= 2 , 0
               0   99.01     5.9           99.11
Permanent Ineff=
       F       F
Bank Sta=0,5.9
XS Rating Curve= 0
Exp/Cntr=.3,.1

Type RM Length L Ch R = 1 ,33      ,7,7,7
#Sta/Elev= 7
     -10   98.97       0   98.97     2.1   96.57     3.9   96.27     5.6   96.27
     7.8   98.97    17.8   98.97
#Mann= 3 , 0 , 0
     -10    .035       0       0    .035       0     7.8    .035       0
#XS Ineff= 2 , 0
               0   98.97     7.8           98.97
Permanent Ineff=
       F       F
Bank Sta=0,7.8
XS Rating Curve= 0
Exp/Cntr=.3,.1

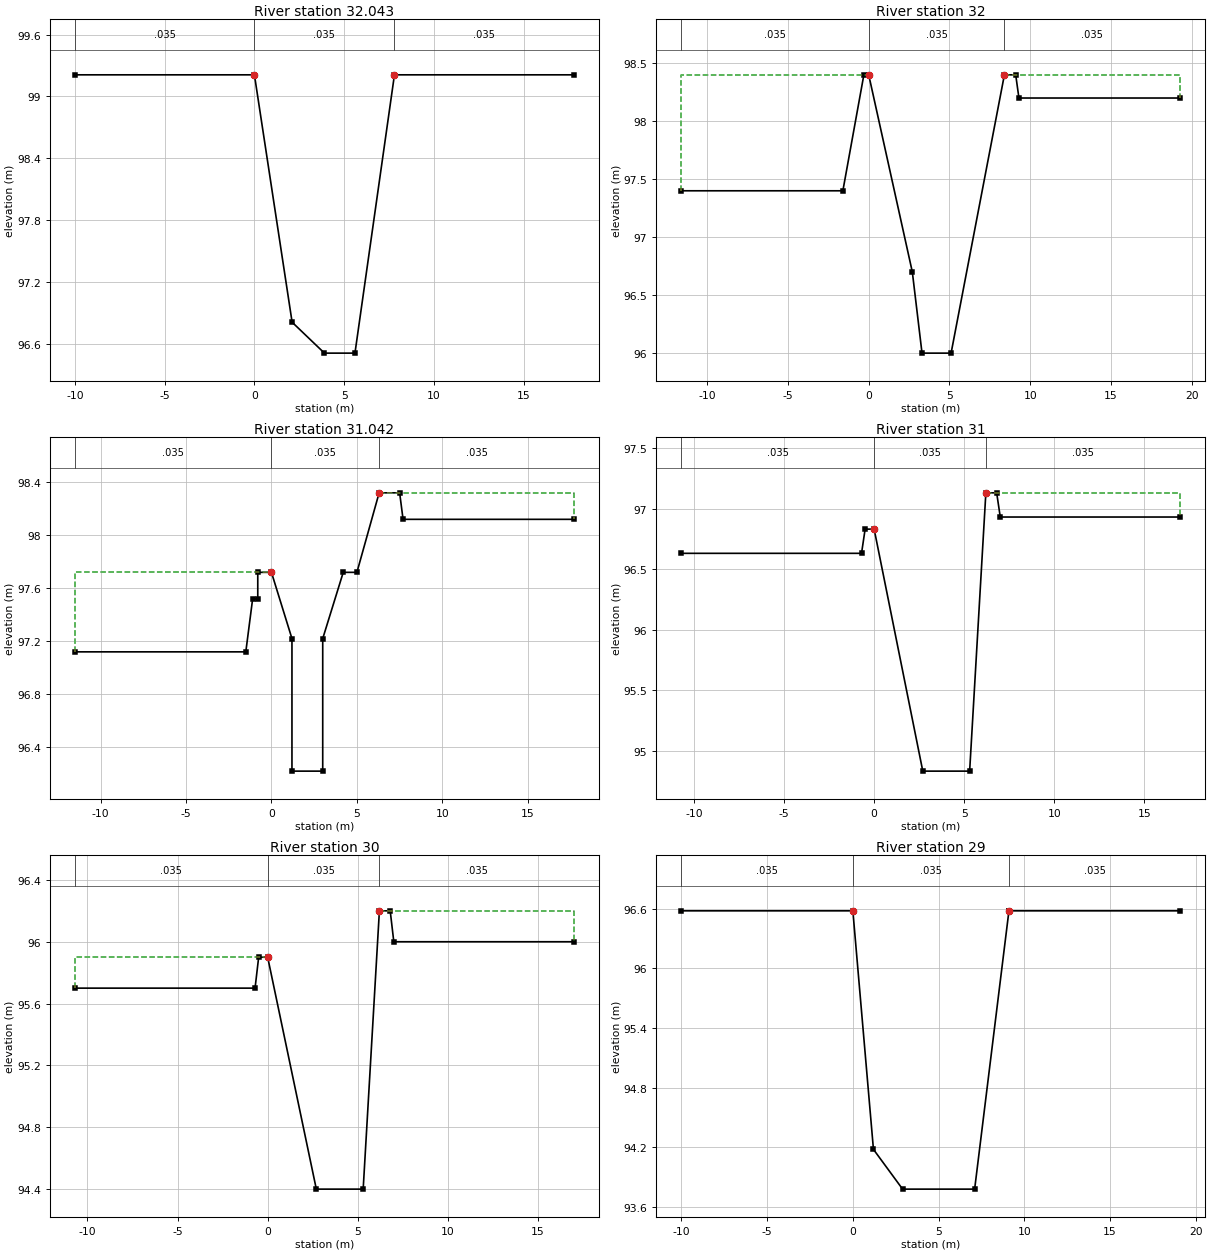
Type RM Length L Ch R = 1 ,32.043  ,43,43,43
#Sta/Elev= 7
     -10   99.21       0   99.21     2.1   96.81     3.9   96.51     5.6   96.51
     7.8   99.21    17.8   99.21
#Mann= 3 , 0 , 0
     -10    .035       0       0    .035       0     7.8    .035       0
#XS Ineff= 2 , 0
               0   99.21     7.8           99.21
Permanent Ineff=
       F       F
Bank Sta=0,7.8
XS Rating Curve= 0
Exp/Cntr=.3,.1

Type RM Length L Ch R = 1 ,32      ,8,8,8
#Sta/Elev= 11
   -11.6    97.4    -1.6    97.4     -.3    98.4       0    98.4     2.7    96.7
     3.3      96     5.1      96     8.4    98.4     9.1    98.4     9.3    98.2
    19.3    98.2
#Mann= 3 , 0 , 0
   -11.6    .035       0       0    .035       0     8.4    .035       0
#XS Ineff= 2 , 0
               0    98.4     8.4            98.4
Permanent Ineff=
       F       F
Bank Sta=0,8.4
XS Rating Curve= 0
Exp/Cntr=.3,.1

Type RM Length L Ch R = 1 ,31.042  ,42,42,42
#Sta/Elev= 16
   -11.5   97.12    -1.5   97.12    -1.1   97.52     -.8   97.52     -.8   97.72
       0   97.72     1.2   97.22     1.2   96.22       3   96.22       3   97.22
     4.2   97.72       5   97.72     6.3   98.32     7.5   98.32     7.7   98.12
    17.7   98.12
#Mann= 3 , 0 , 0
   -11.5    .035       0       0    .035       0     6.3    .035       0
#XS Ineff= 2 , 0
               0   97.72     6.3           98.32
Permanent Ineff=
       F       F
Bank Sta=0,6.3
XS Rating Curve= 0
Exp/Cntr=.3,.1

Type RM Length L Ch R = 1 ,31      ,50,50,50
#Sta/Elev= 10
   -10.7   96.63     -.7   96.63     -.5   96.83       0   96.83     2.7   94.83
     5.3   94.83     6.2   97.13     6.8   97.13       7   96.93      17   96.93
#Mann= 3 , 0 , 0
   -10.7    .035       0       0    .035       0     6.2    .035       0
#XS Ineff= 2 , 0
       0       0   96.83     6.2       0   97.13
Permanent Ineff=
       F       F
Bank Sta=0,6.2
XS Rating Curve= 0
Exp/Cntr=.3,.1

Type RM Length L Ch R = 1 ,30      ,50,50,50
#Sta/Elev= 10
   -10.7    95.7     -.7    95.7     -.5    95.9       0    95.9     2.7    94.4
     5.3    94.4     6.2    96.2     6.8    96.2       7      96      17      96
#Mann= 3 , 0 , 0
   -10.7    .035       0       0    .035       0     6.2    .035       0
#XS Ineff= 2 , 0
               0    95.9     6.2            96.2
Permanent Ineff=
       F       F
Bank Sta=0,6.2
XS Rating Curve= 0
Exp/Cntr=.3,.1

Type RM Length L Ch R = 1 ,29      ,50,50,50
#Sta/Elev= 8
     -10   96.58       0   96.58     1.2   94.18     2.9   93.78     7.1   93.78
     9.1   96.58     9.1   96.58    19.1   96.58
#Mann= 3 , 0 , 0
     -10    .035       0       0    .035       0     9.1    .035       0
#XS Ineff= 2 , 0
               0   96.58     9.1           96.58
Permanent Ineff=
       F       F
Bank Sta=0,9.1
XS Rating Curve= 0
Exp/Cntr=.3,.1