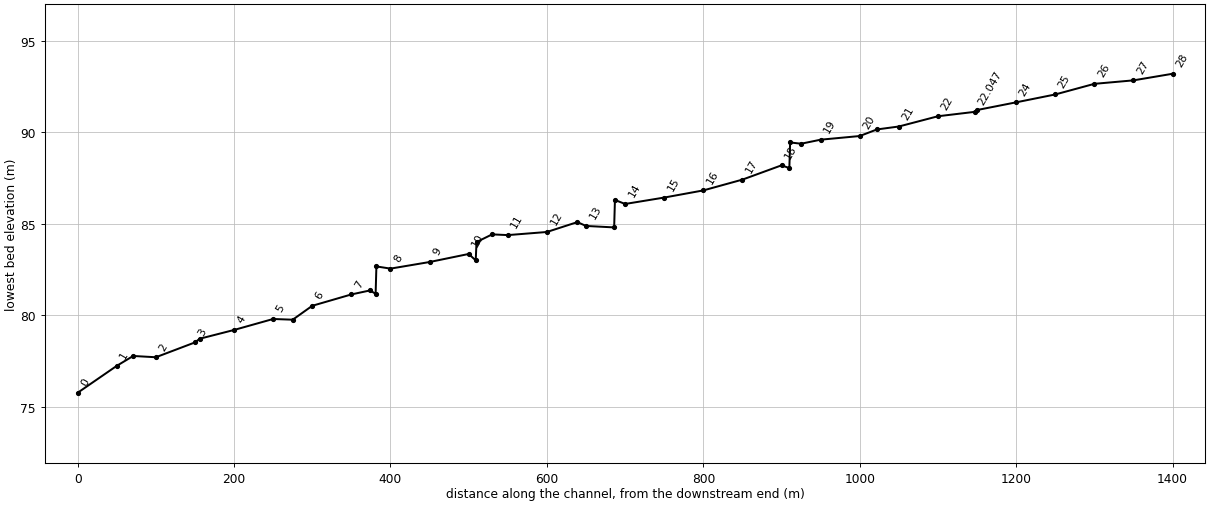
HEC-RAS study sinsan-ch.prj: sinsan-ch

--- sinsan-ch.g01 (geometry) --- (continued)

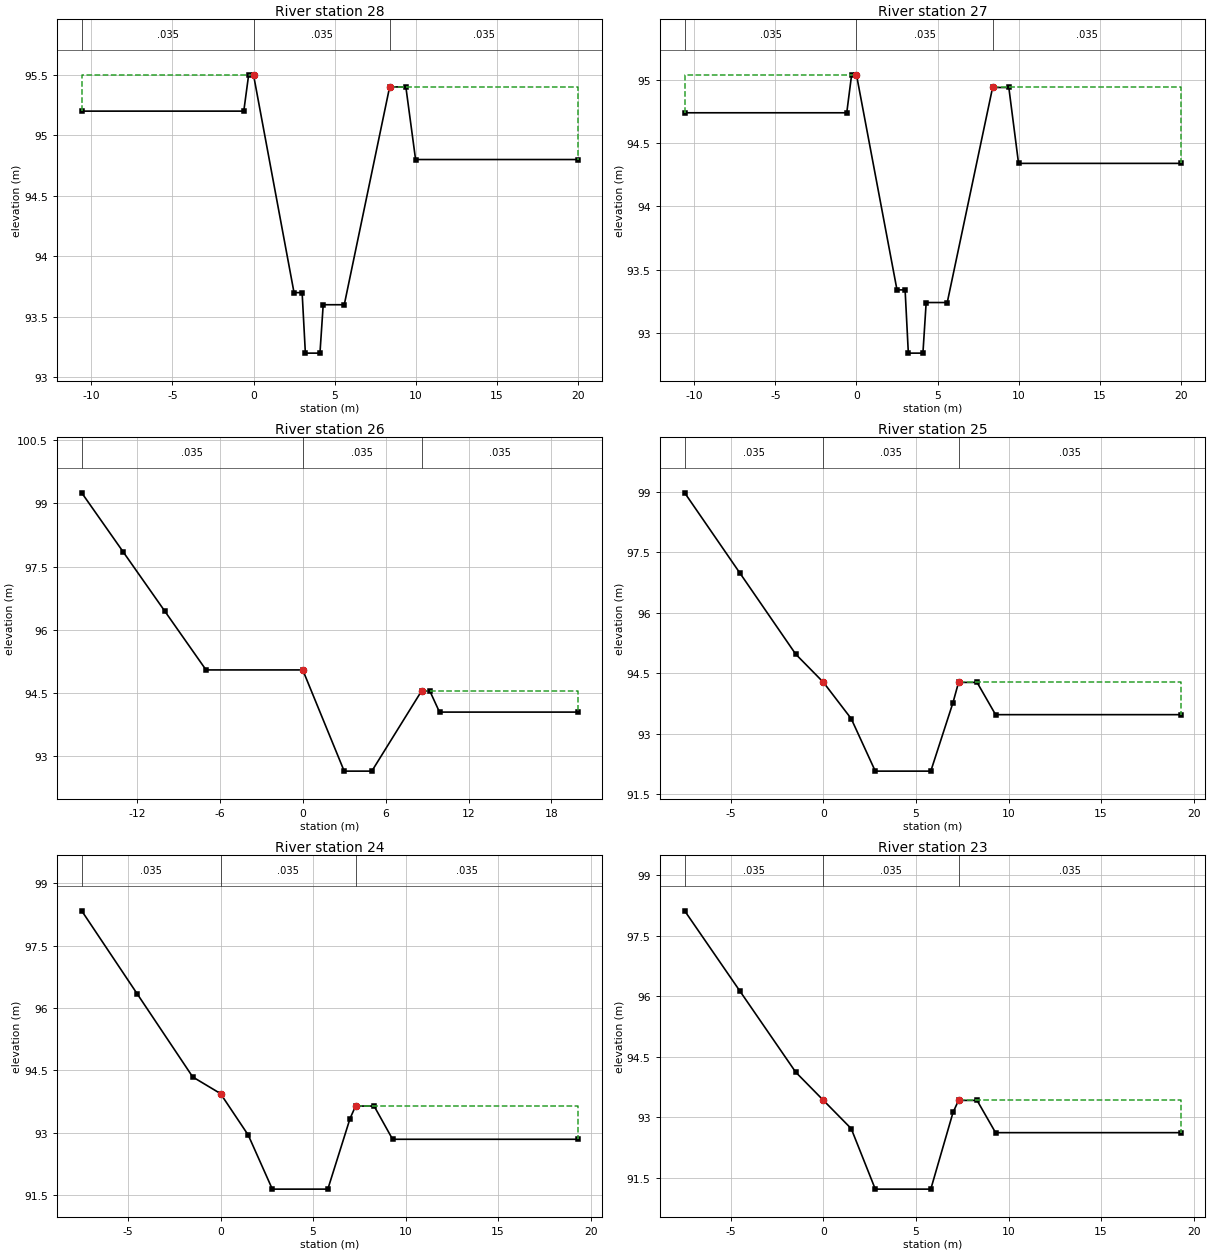
Type RM Length L Ch R = 1 ,28      ,50,50,50
#Sta/Elev= 14
   -10.6    95.2     -.6    95.2     -.3    95.5       0    95.5     2.5    93.7
       3    93.7     3.2    93.2     4.1    93.2     4.3    93.6     5.6    93.6
     8.4    95.4     9.4    95.4      10    94.8      20    94.8
#Mann= 3 , 0 , 0
   -10.6    .035       0       0    .035       0     8.4    .035       0
#XS Ineff= 2 , 0
               0    95.5     8.4            95.4
Permanent Ineff=
       F       F
Bank Sta=0,8.4
XS Rating Curve= 0
Exp/Cntr=.3,.1

Type RM Length L Ch R = 1 ,27      ,50,50,50
#Sta/Elev= 14
   -10.6   94.74     -.6   94.74     -.3   95.04       0   95.04     2.5   93.34
       3   93.34     3.2   92.84     4.1   92.84     4.3   93.24     5.6   93.24
     8.4   94.94     9.4   94.94      10   94.34      20   94.34
#Mann= 3 , 0 , 0
   -10.6    .035       0       0    .035       0     8.4    .035       0
#XS Ineff= 2 , 0
               0   95.04     8.4           94.94
Permanent Ineff=
       F       F
Bank Sta=0,8.4
XS Rating Curve= 0
Exp/Cntr=.3,.1

Type RM Length L Ch R = 1 ,26      ,50,50,50
#Sta/Elev= 11
     -16   99.25     -13   97.85     -10   96.45      -7   95.05       0   95.05
       3   92.65       5   92.65     8.6   94.55     9.2   94.55     9.9   94.05
    19.9   94.05
#Mann= 3 , 0 , 0
     -16    .035       0       0    .035       0     8.6    .035       0
#XS Ineff= 2 , 0
               0   95.05     8.6           94.55
Permanent Ineff=
       F       F
Bank Sta=0,8.6
XS Rating Curve= 0
Exp/Cntr=.3,.1

Type RM Length L Ch R = 1 ,25      ,50,50,50
#Sta/Elev= 12
    -7.5   98.97    -4.5   96.97    -1.5   94.97       0   94.27     1.5   93.37
     2.8   92.07     5.8   92.07       7   93.77     7.3   94.27     8.3   94.27
     9.3   93.47    19.3   93.47
#Mann= 3 , 0 , 0
    -7.5    .035       0       0    .035       0     7.3    .035       0
#XS Ineff= 2 , 0
               0   94.27     7.3           94.27
Permanent Ineff=
       F       F
Bank Sta=0,7.3
XS Rating Curve= 0
Exp/Cntr=.3,.1

Type RM Length L Ch R = 1 ,24      ,50,50,50
#Sta/Elev= 12
    -7.5   98.34    -4.5   96.34    -1.5   94.34       0   93.94     1.5   92.94
     2.8   91.64     5.8   91.64       7   93.34     7.3   93.64     8.3   93.64
     9.3   92.84    19.3   92.84
#Mann= 3 , 0 , 0
    -7.5    .035       0       0    .035       0     7.3    .035       0
#XS Ineff= 2 , 0
               0   93.94     7.3           93.64
Permanent Ineff=
       F       F
Bank Sta=0,7.3
XS Rating Curve= 0
Exp/Cntr=.3,.1

Type RM Length L Ch R = 1 ,23      ,3,3,3
#Sta/Elev= 12
    -7.5   98.12    -4.5   96.12    -1.5   94.12       0   93.42     1.5   92.72
     2.8   91.22     5.8   91.22       7   93.12     7.3   93.42     8.3   93.42
     9.3   92.62    19.3   92.62
#Mann= 3 , 0 , 0
    -7.5    .035       0       0    .035       0     7.3    .035       0
#XS Ineff= 2 , 0
               0   93.42     7.3           93.42
Permanent Ineff=
       F       F
Bank Sta=0,7.3
XS Rating Curve= 0
Exp/Cntr=.3,.1

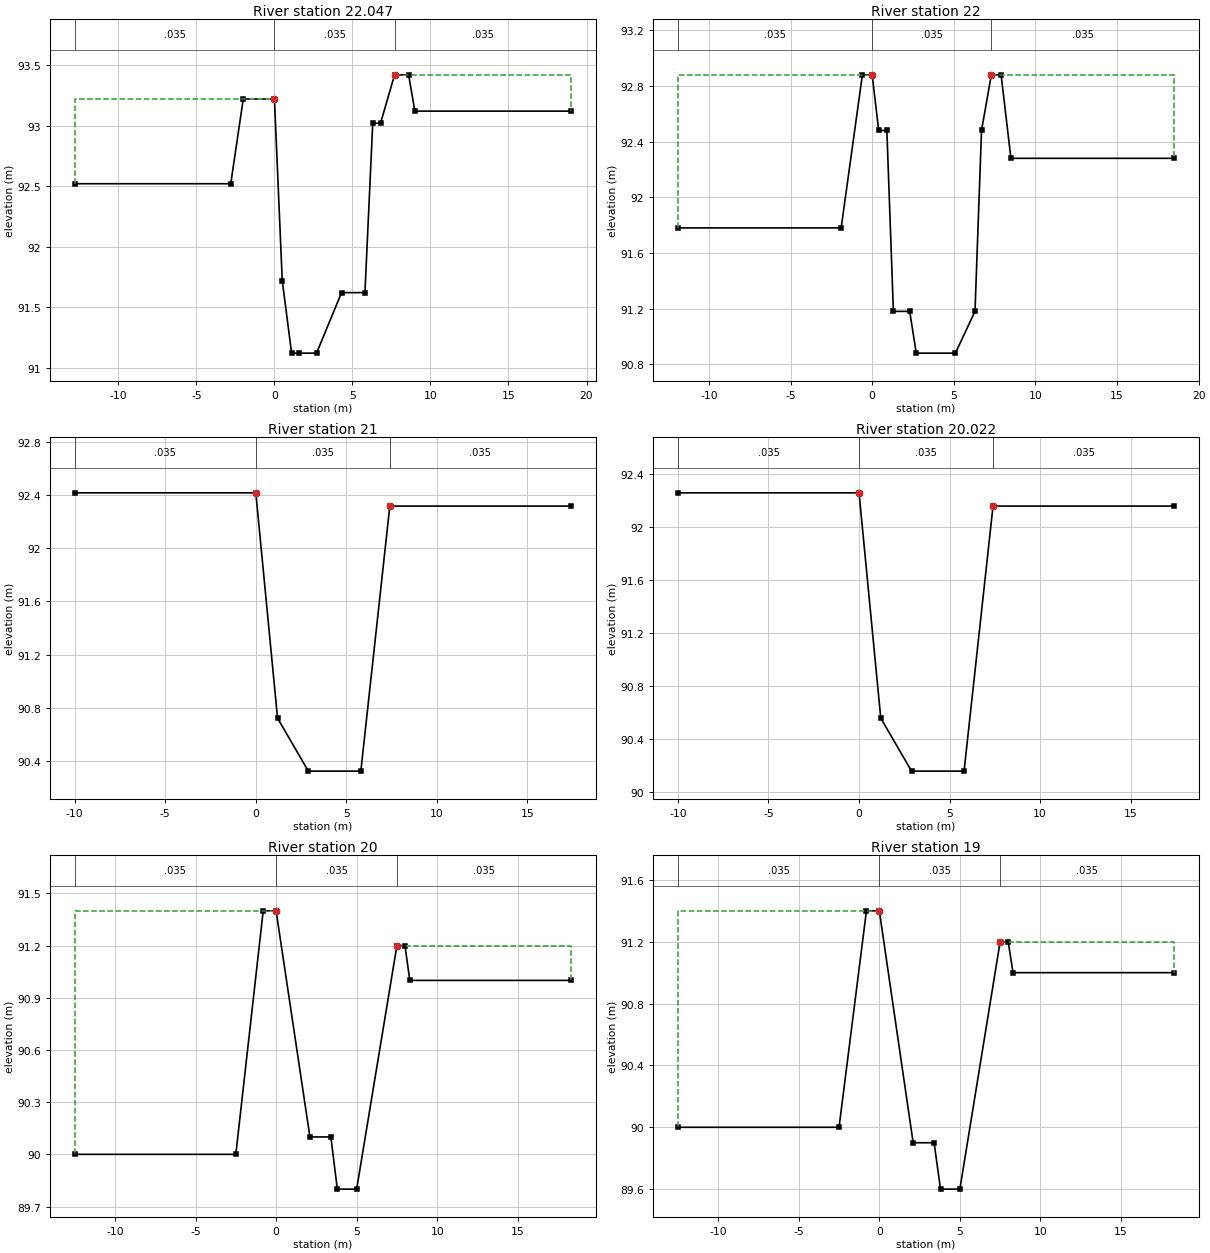
Type RM Length L Ch R = 1 ,22.047  ,47,47,47
#Sta/Elev= 16
   -12.8   92.52    -2.8   92.52      -2   93.22       0   93.22      .5   91.72
     1.1   91.12     1.6   91.12     2.7   91.12     4.3   91.62     5.8   91.62
     6.3   93.02     6.8   93.02     7.7   93.42     8.6   93.42       9   93.12
      19   93.12
#Mann= 3 , 0 , 0
   -12.8    .035       0       0    .035       0     7.7    .035       0
#XS Ineff= 2 , 0
               0   93.22     7.7           93.42
Permanent Ineff=
       F       F
Bank Sta=0,7.7
XS Rating Curve= 0
Exp/Cntr=.3,.1

Type RM Length L Ch R = 1 ,22      ,50,50,50
#Sta/Elev= 16
   -11.9   91.78    -1.9   91.78     -.6   92.88       0   92.88      .4   92.48
      .9   92.48     1.3   91.18     2.3   91.18     2.7   90.88     5.1   90.88
     6.3   91.18     6.7   92.48     7.3   92.88     7.9   92.88     8.5   92.28
    18.5   92.28
#Mann= 3 , 0 , 0
   -11.9    .035       0       0    .035       0     7.3    .035       0
#XS Ineff= 2 , 0
               0   92.88     7.3           92.88
Permanent Ineff=
       F       F
Bank Sta=0,7.3
XS Rating Curve= 0
Exp/Cntr=.3,.1

Type RM Length L Ch R = 1 ,21      ,28,28,28
#Sta/Elev= 7
     -10   92.42       0   92.42     1.2   90.72     2.9   90.32     5.8   90.32
     7.4   92.32    17.4   92.32
#Mann= 3 , 0 , 0
     -10    .035       0       0    .035       0     7.4    .035       0
#XS Ineff= 2 , 0
               0   92.42     7.4           92.32
Permanent Ineff=
       F       F
Bank Sta=0,7.4
XS Rating Curve= 0
Exp/Cntr=.3,.1

Type RM Length L Ch R = 1 ,20.022  ,22,22,22
#Sta/Elev= 7
     -10   92.26       0   92.26     1.2   90.56     2.9   90.16     5.8   90.16
     7.4   92.16    17.4   92.16
#Mann= 3 , 0 , 0
     -10    .035       0       0    .035       0     7.4    .035       0
#XS Ineff= 2 , 0
               0   92.26     7.4           92.16
Permanent Ineff=
       F       F
Bank Sta=0,7.4
XS Rating Curve= 0
Exp/Cntr=.3,.1

Type RM Length L Ch R = 1 ,20      ,50,50,50
#Sta/Elev= 12
   -12.5      90    -2.5      90     -.8    91.4       0    91.4     2.1    90.1
     3.4    90.1     3.8    89.8       5    89.8     7.5    91.2       8    91.2
     8.3      91    18.3      91
#Mann= 3 , 0 , 0
   -12.5    .035       0       0    .035       0     7.5    .035       0
#XS Ineff= 2 , 0
               0    91.4     7.5            91.2
Permanent Ineff=
       F       F
Bank Sta=0,7.5
XS Rating Curve= 0
Exp/Cntr=.3,.1

Type RM Length L Ch R = 1 ,19      ,25,25,25
#Sta/Elev= 12
   -12.5      90    -2.5      90     -.8    91.4       0    91.4     2.1    89.9
     3.4    89.9     3.8    89.6       5    89.6     7.5    91.2       8    91.2
     8.3      91    18.3      91
#Mann= 3 , 0 , 0
   -12.5    .035       0       0    .035       0     7.5    .035       0
#XS Ineff= 2 , 0
               0    91.4     7.5            91.2
Permanent Ineff=
       F       F
Bank Sta=0,7.5
XS Rating Curve= 0
Exp/Cntr=.3,.1

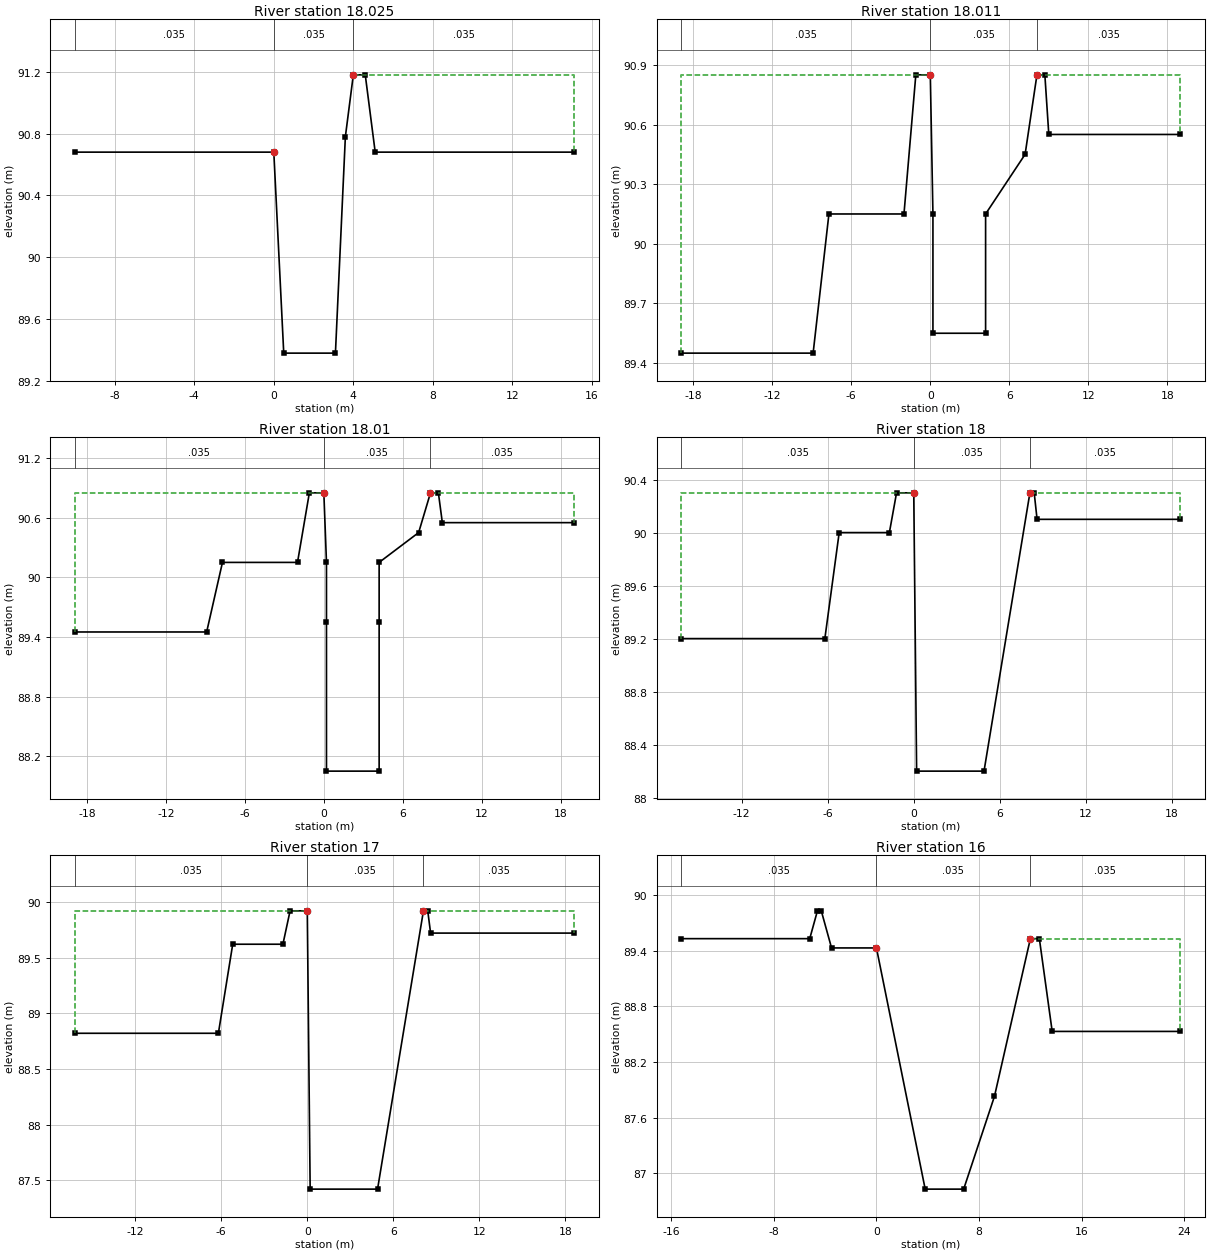
Type RM Length L Ch R = 1 ,18.025  ,14,14,14
#Sta/Elev= 9
     -10   90.68       0   90.68      .5   89.38     3.1   89.38     3.6   90.78
       4   91.18     4.6   91.18     5.1   90.68    15.1   90.68
#Mann= 3 , 0 , 0
     -10    .035       0       0    .035       0       4    .035       0
#XS Ineff= 2 , 0
               0   90.68       4           91.18
Permanent Ineff=
       F       F
Bank Sta=0,4
XS Rating Curve= 0
Exp/Cntr=.3,.1

Type RM Length L Ch R = 1 ,18.011  ,1,1,1
#Sta/Elev= 15
   -18.9   89.45    -8.9   89.45    -7.7   90.15      -2   90.15    -1.1   90.85
       0   90.85      .2   90.15      .2   89.55     4.2   89.55     4.2   90.15
     7.2   90.45     8.1   90.85     8.7   90.85       9   90.55      19   90.55
#Mann= 3 , 0 , 0
   -18.9    .035       0       0    .035       0     8.1    .035       0
#XS Ineff= 2 , 0
               0   90.85     8.1           90.85
Permanent Ineff=
       F       F
Bank Sta=0,8.1
XS Rating Curve= 0
Exp/Cntr=.3,.1

Type RM Length L Ch R = 1 ,18.01   ,10,10,10
#Sta/Elev= 17
   -18.9   89.45    -8.9   89.45    -7.7   90.15      -2   90.15    -1.1   90.85
       0   90.85      .2   90.15      .2   89.55      .2   88.05     4.2   88.05
     4.2   89.55     4.2   90.15     7.2   90.45     8.1   90.85     8.7   90.85
       9   90.55      19   90.55
#Mann= 3 , 0 , 0
   -18.9    .035       0       0    .035       0     8.1    .035       0
#XS Ineff= 2 , 0
               0   90.85     8.1           90.85
Permanent Ineff=
       F       F
Bank Sta=0,8.1
XS Rating Curve= 0
Exp/Cntr=.3,.1

Type RM Length L Ch R = 1 ,18      ,50,50,50
#Sta/Elev= 12
   -16.2    89.2    -6.2    89.2    -5.2      90    -1.7      90    -1.2    90.3
       0    90.3      .2    88.2     4.9    88.2     8.1    90.3     8.4    90.3
     8.6    90.1    18.6    90.1
#Mann= 3 , 0 , 0
   -16.2    .035       0       0    .035       0     8.1    .035       0
#XS Ineff= 2 , 0
               0    90.3     8.1            90.3
Permanent Ineff=
       F       F
Bank Sta=0,8.1
XS Rating Curve= 0
Exp/Cntr=.3,.1

Type RM Length L Ch R = 1 ,17      ,50,50,50
#Sta/Elev= 12
   -16.2   88.82    -6.2   88.82    -5.2   89.62    -1.7   89.62    -1.2   89.92
       0   89.92      .2   87.42     4.9   87.42     8.1   89.92     8.4   89.92
     8.6   89.72    18.6   89.72
#Mann= 3 , 0 , 0
   -16.2    .035       0       0    .035       0     8.1    .035       0
#XS Ineff= 2 , 0
               0   89.92     8.1           89.92
Permanent Ineff=
       F       F
Bank Sta=0,8.1
XS Rating Curve= 0
Exp/Cntr=.3,.1

Type RM Length L Ch R = 1 ,16      ,50,50,50
#Sta/Elev= 13
   -15.2   89.53    -5.2   89.53    -4.6   89.83    -4.3   89.83    -3.5   89.43
       0   89.43     3.8   86.83     6.8   86.83     9.2   87.83      12   89.53
    12.7   89.53    13.7   88.53    23.7   88.53
#Mann= 3 , 0 , 0
   -15.2    .035       0       0    .035       0      12    .035       0
#XS Ineff= 2 , 0
               0   89.43      12           89.53
Permanent Ineff=
       F       F
Bank Sta=0,12
XS Rating Curve= 0
Exp/Cntr=.3,.1

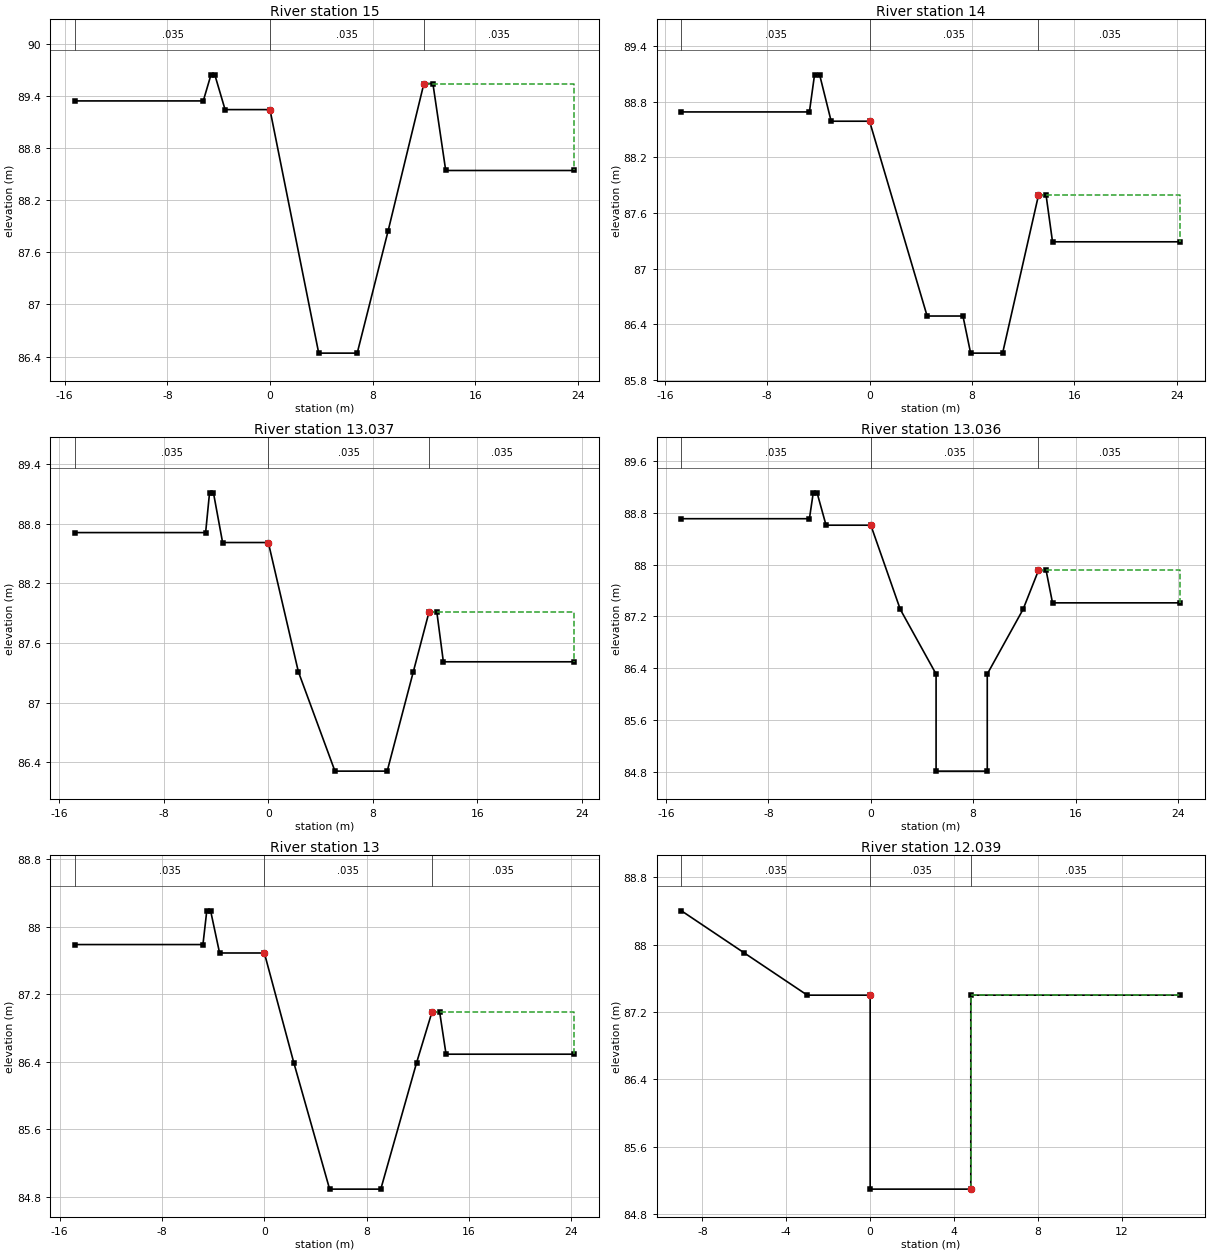
Type RM Length L Ch R = 1 ,15      ,50,50,50
#Sta/Elev= 13
   -15.2   89.34    -5.2   89.34    -4.6   89.64    -4.3   89.64    -3.5   89.24
       0   89.24     3.8   86.44     6.8   86.44     9.2   87.84      12   89.54
    12.7   89.54    13.7   88.54    23.7   88.54
#Mann= 3 , 0 , 0
   -15.2    .035       0       0    .035       0      12    .035       0
#XS Ineff= 2 , 0
               0   89.24      12           89.54
Permanent Ineff=
       F       F
Bank Sta=0,12
XS Rating Curve= 0
Exp/Cntr=.3,.1

Type RM Length L Ch R = 1 ,14      ,13,13,13
#Sta/Elev= 14
   -14.7   88.69    -4.7   88.69    -4.3   89.09    -3.9   89.09      -3   88.59
       0   88.59     4.5   86.49     7.3   86.49     7.9   86.09    10.4   86.09
    13.2   87.79    13.8   87.79    14.3   87.29    24.3   87.29
#Mann= 3 , 0 , 0
   -14.7    .035       0       0    .035       0    13.2    .035       0
#XS Ineff= 2 , 0
               0   88.59    13.2           87.79
Permanent Ineff=
       F       F
Bank Sta=0,13.2
XS Rating Curve= 0
Exp/Cntr=.3,.1

Type RM Length L Ch R = 1 ,13.037  ,1,1,1
#Sta/Elev= 14
   -14.8   88.71    -4.8   88.71    -4.5   89.11    -4.2   89.11    -3.5   88.61
       0   88.61     2.3   87.31     5.1   86.31     9.1   86.31    11.1   87.31
    12.3   87.91    12.9   87.91    13.4   87.41    23.4   87.41
#Mann= 3 , 0 , 0
   -14.8    .035       0       0    .035       0    12.3    .035       0
#XS Ineff= 2 , 0
               0   88.61    12.3           87.91
Permanent Ineff=
       F       F
Bank Sta=0,12.3
XS Rating Curve= 0
Exp/Cntr=.3,.1

Type RM Length L Ch R = 1 ,13.036  ,36,36,36
#Sta/Elev= 16
   -14.8   88.71    -4.8   88.71    -4.5   89.11    -4.2   89.11    -3.5   88.61
       0   88.61     2.3   87.31     5.1   86.31     5.1   84.81     9.1   84.81
     9.1   86.31    11.9   87.31    13.1   87.91    13.7   87.91    14.2   87.41
    24.2   87.41
#Mann= 3 , 0 , 0
   -14.8    .035       0       0    .035       0    13.1    .035       0
#XS Ineff= 2 , 0
               0   88.61    13.1           87.91
Permanent Ineff=
       F       F
Bank Sta=0,13.1
XS Rating Curve= 0
Exp/Cntr=.3,.1

Type RM Length L Ch R = 1 ,13      ,11,11,11
#Sta/Elev= 14
   -14.8   87.79    -4.8   87.79    -4.5   88.19    -4.2   88.19    -3.5   87.69
       0   87.69     2.3   86.39     5.1   84.89     9.1   84.89    11.9   86.39
    13.1   86.99    13.7   86.99    14.2   86.49    24.2   86.49
#Mann= 3 , 0 , 0
   -14.8    .035       0       0    .035       0    13.1    .035       0
#XS Ineff= 2 , 0
               0   87.69    13.1           86.99
Permanent Ineff=
       F       F
Bank Sta=0,13.1
XS Rating Curve= 0
Exp/Cntr=.3,.1

Type RM Length L Ch R = 1 ,12.039  ,39,39,39
#Sta/Elev= 8
      -9    88.4      -6    87.9      -3    87.4       0    87.4       0    85.1
     4.8    85.1     4.8    87.4    14.8    87.4
#Mann= 3 , 0 , 0
      -9    .035       0       0    .035       0     4.8    .035       0
#XS Ineff= 2 , 0
               0    87.4     4.8            87.4
Permanent Ineff=
       F       F
Bank Sta=0,4.8
XS Rating Curve= 0
Exp/Cntr=.3,.1

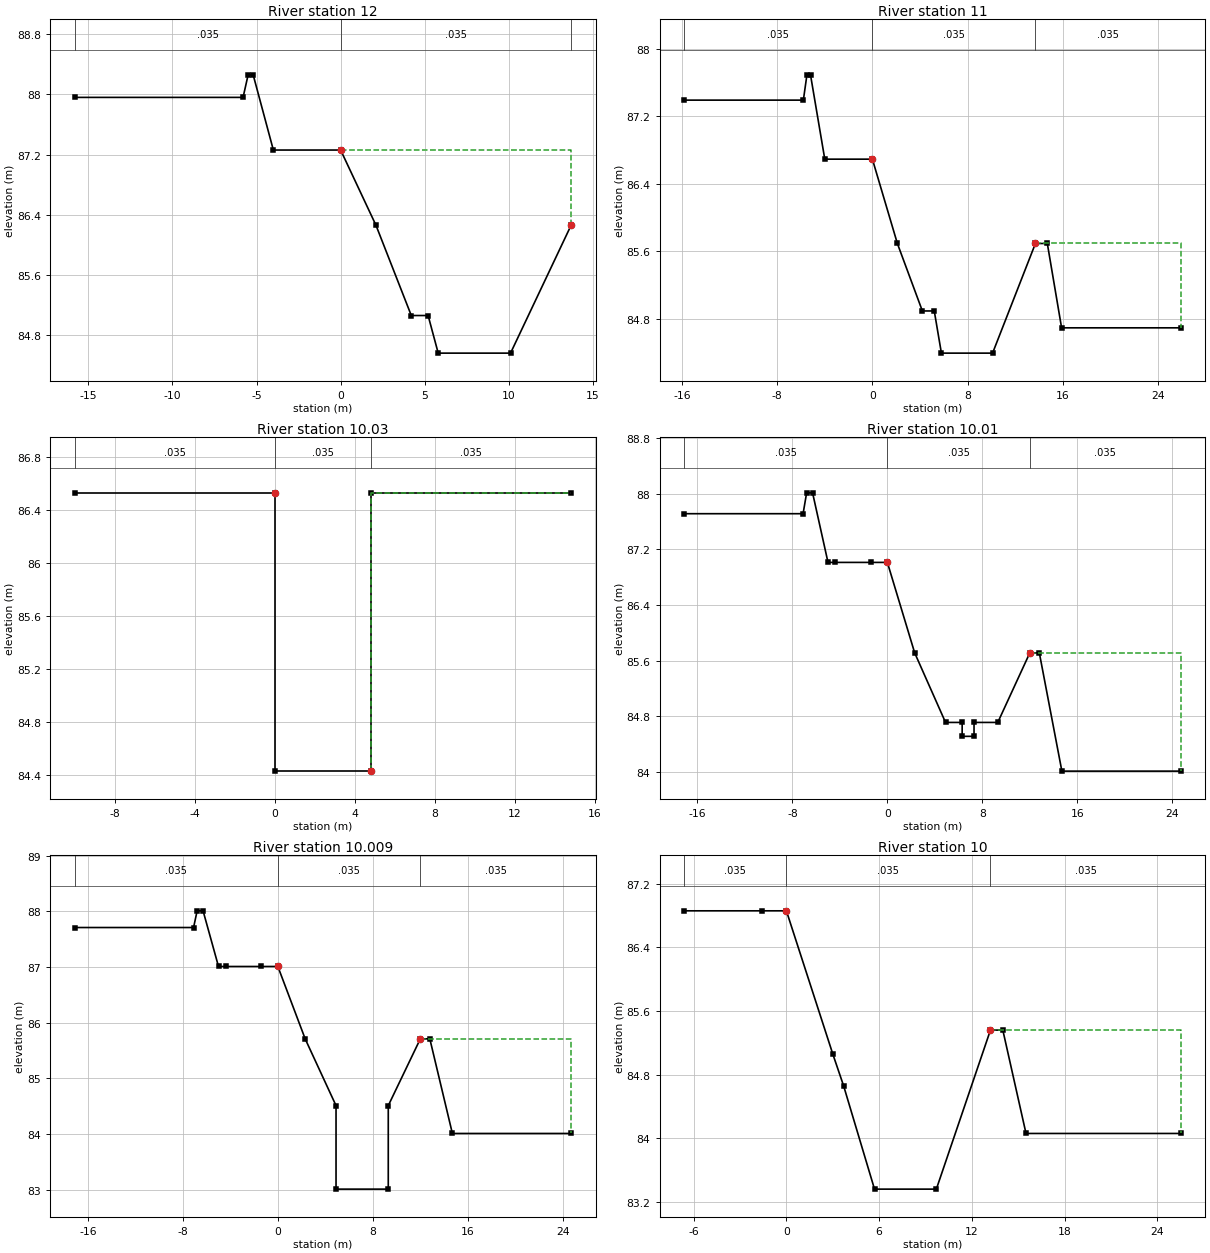
Type RM Length L Ch R = 1 ,12      ,50,50,50
#Sta/Elev= 12
   -15.8   87.96    -5.8   87.96    -5.5   88.26    -5.2   88.26      -4   87.26
       0   87.26     2.1   86.26     4.2   85.06     5.2   85.06     5.8   84.56
    10.1   84.56    13.7   86.26
#Mann= 3 , 0 , 0
   -15.8    .035       0       0    .035       0    13.7    .035       0
#XS Ineff= 2 , 0
       0       0   87.26    13.7       0   86.26
Permanent Ineff=
       F       F
Bank Sta=0,13.7
XS Rating Curve= 0
Exp/Cntr=.3,.1

Type RM Length L Ch R = 1 ,11      ,20,20,20
#Sta/Elev= 15
   -15.8   87.39    -5.8   87.39    -5.5   87.69    -5.2   87.69      -4   86.69
       0   86.69     2.1   85.69     4.2   84.89     5.2   84.89     5.8   84.39
    10.1   84.39    13.7   85.69    14.7   85.69    15.9   84.69    25.9   84.69
#Mann= 3 , 0 , 0
   -15.8    .035       0       0    .035       0    13.7    .035       0
#XS Ineff= 2 , 0
               0   86.69    13.7           85.69
Permanent Ineff=
       F       F
Bank Sta=0,13.7
XS Rating Curve= 0
Exp/Cntr=.3,.1

Type RM Length L Ch R = 1 ,10.03   ,20,20,20
#Sta/Elev= 6
     -10   86.53       0   86.53       0   84.43     4.8   84.43     4.8   86.53
    14.8   86.53
#Mann= 3 , 0 , 0
     -10    .035       0       0    .035       0     4.8    .035       0
#XS Ineff= 2 , 0
               0   86.53     4.8           86.53
Permanent Ineff=
       F       F
Bank Sta=0,4.8
XS Rating Curve= 0
Exp/Cntr=.3,.1

Type RM Length L Ch R = 1 ,10.01   ,1,1,1
#Sta/Elev= 19
   -17.1   87.71    -7.1   87.71    -6.8   88.01    -6.3   88.01      -5   87.01
    -4.4   87.01    -1.4   87.01       0   87.01     2.3   85.71     4.9   84.71
     6.3   84.71     6.3   84.51     7.3   84.51     7.3   84.71     9.3   84.71
      12   85.71    12.8   85.71    14.7   84.01    24.7   84.01
#Mann= 3 , 0 , 0
   -17.1    .035       0       0    .035       0      12    .035       0
#XS Ineff= 2 , 0
               0   87.01      12           85.71
Permanent Ineff=
       F       F
Bank Sta=0,12
XS Rating Curve= 0
Exp/Cntr=.3,.1

Type RM Length L Ch R = 1 ,10.009  ,9,9,9
#Sta/Elev= 17
   -17.1   87.71    -7.1   87.71    -6.8   88.01    -6.3   88.01      -5   87.01
    -4.4   87.01    -1.4   87.01       0   87.01     2.3   85.71     4.9   84.51
     4.9   83.01     9.3   83.01     9.3   84.51      12   85.71    12.8   85.71
    14.7   84.01    24.7   84.01
#Mann= 3 , 0 , 0
   -17.1    .035       0       0    .035       0      12    .035       0
#XS Ineff= 2 , 0
               0   87.01      12           85.71
Permanent Ineff=
       F       F
Bank Sta=0,12
XS Rating Curve= 0
Exp/Cntr=.3,.1

Type RM Length L Ch R = 1 ,10      ,50,50,50
#Sta/Elev= 11
    -6.6   86.86    -1.6   86.86       0   86.86       3   85.06     3.7   84.66
     5.7   83.36     9.7   83.36    13.2   85.36      14   85.36    15.5   84.06
    25.5   84.06
#Mann= 3 , 0 , 0
    -6.6    .035       0       0    .035       0    13.2    .035       0
#XS Ineff= 2 , 0
               0   86.86    13.2           85.36
Permanent Ineff=
       F       F
Bank Sta=0,13.2
XS Rating Curve= 0
Exp/Cntr=.3,.1

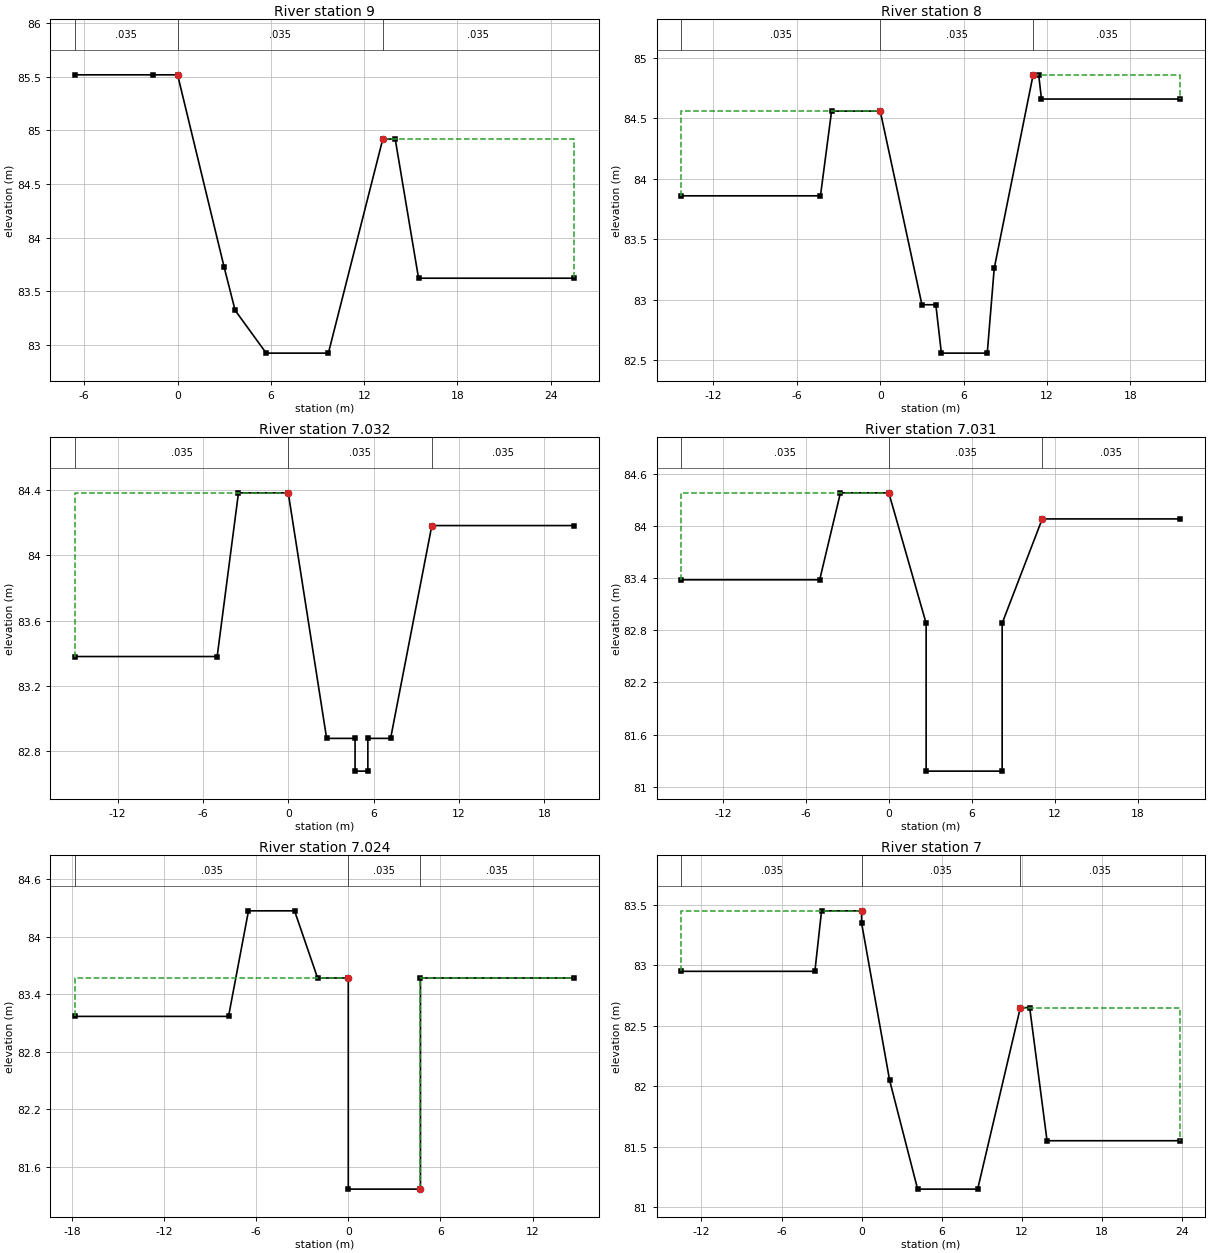
Type RM Length L Ch R = 1 ,9       ,50,50,50
#Sta/Elev= 11
    -6.6   85.52    -1.6   85.52       0   85.52       3   83.72     3.7   83.32
     5.7   82.92     9.7   82.92    13.2   84.92      14   84.92    15.5   83.62
    25.5   83.62
#Mann= 3 , 0 , 0
    -6.6    .035       0       0    .035       0    13.2    .035       0
#XS Ineff= 2 , 0
               0   85.52    13.2           84.92
Permanent Ineff=
       F       F
Bank Sta=0,13.2
XS Rating Curve= 0
Exp/Cntr=.3,.1

Type RM Length L Ch R = 1 ,8       ,18,18,18
#Sta/Elev= 13
   -14.3   83.86    -4.3   83.86    -3.5   84.56       0   84.56       3   82.96
       4   82.96     4.4   82.56     7.7   82.56     8.2   83.26      11   84.86
    11.4   84.86    11.6   84.66    21.6   84.66
#Mann= 3 , 0 , 0
   -14.3    .035       0       0    .035       0      11    .035       0
#XS Ineff= 2 , 0
               0   84.56      11           84.86
Permanent Ineff=
       F       F
Bank Sta=0,11
XS Rating Curve= 0
Exp/Cntr=.3,.1

Type RM Length L Ch R = 1 ,7.032   ,1,1,1
#Sta/Elev= 12
     -15   83.38      -5   83.38    -3.5   84.38       0   84.38     2.7   82.88
     4.7   82.88     4.7   82.68     5.6   82.68     5.6   82.88     7.2   82.88
    10.1   84.18    20.1   84.18
#Mann= 3 , 0 , 0
     -15    .035       0       0    .035       0    10.1    .035       0
#XS Ineff= 2 , 0
               0   84.38    10.1           84.18
Permanent Ineff=
       F       F
Bank Sta=0,10.1
XS Rating Curve= 0
Exp/Cntr=.3,.1

Type RM Length L Ch R = 1 ,7.031   ,7,7,7
#Sta/Elev= 10
     -15   83.38      -5   83.38    -3.5   84.38       0   84.38     2.7   82.88
     2.7   81.18     8.2   81.18     8.2   82.88    11.1   84.08    21.1   84.08
#Mann= 3 , 0 , 0
     -15    .035       0       0    .035       0    11.1    .035       0
#XS Ineff= 2 , 0
               0   84.38    11.1           84.08
Permanent Ineff=
       F       F
Bank Sta=0,11.1
XS Rating Curve= 0
Exp/Cntr=.3,.1

Type RM Length L Ch R = 1 ,7.024   ,24,24,24
#Sta/Elev= 10
   -17.8   83.17    -7.8   83.17    -6.5   84.27    -3.5   84.27      -2   83.57
       0   83.57       0   81.37     4.7   81.37     4.7   83.57    14.7   83.57
#Mann= 3 , 0 , 0
   -17.8    .035       0       0    .035       0     4.7    .035       0
#XS Ineff= 2 , 0
               0   83.57     4.7           83.57
Permanent Ineff=
       F       F
Bank Sta=0,4.7
XS Rating Curve= 0
Exp/Cntr=.3,.1

Type RM Length L Ch R = 1 ,7       ,50,50,50
#Sta/Elev= 12
   -13.5   82.95    -3.5   82.95      -3   83.45       0   83.45       0   83.35
     2.1   82.05     4.2   81.15     8.7   81.15    11.9   82.65    12.6   82.65
    13.9   81.55    23.9   81.55
#Mann= 3 , 0 , 0
   -13.5    .035       0       0    .035       0    11.9    .035       0
#XS Ineff= 2 , 0
               0   83.45    11.9           82.65
Permanent Ineff=
       F       F
Bank Sta=0,11.9
XS Rating Curve= 0
Exp/Cntr=.3,.1

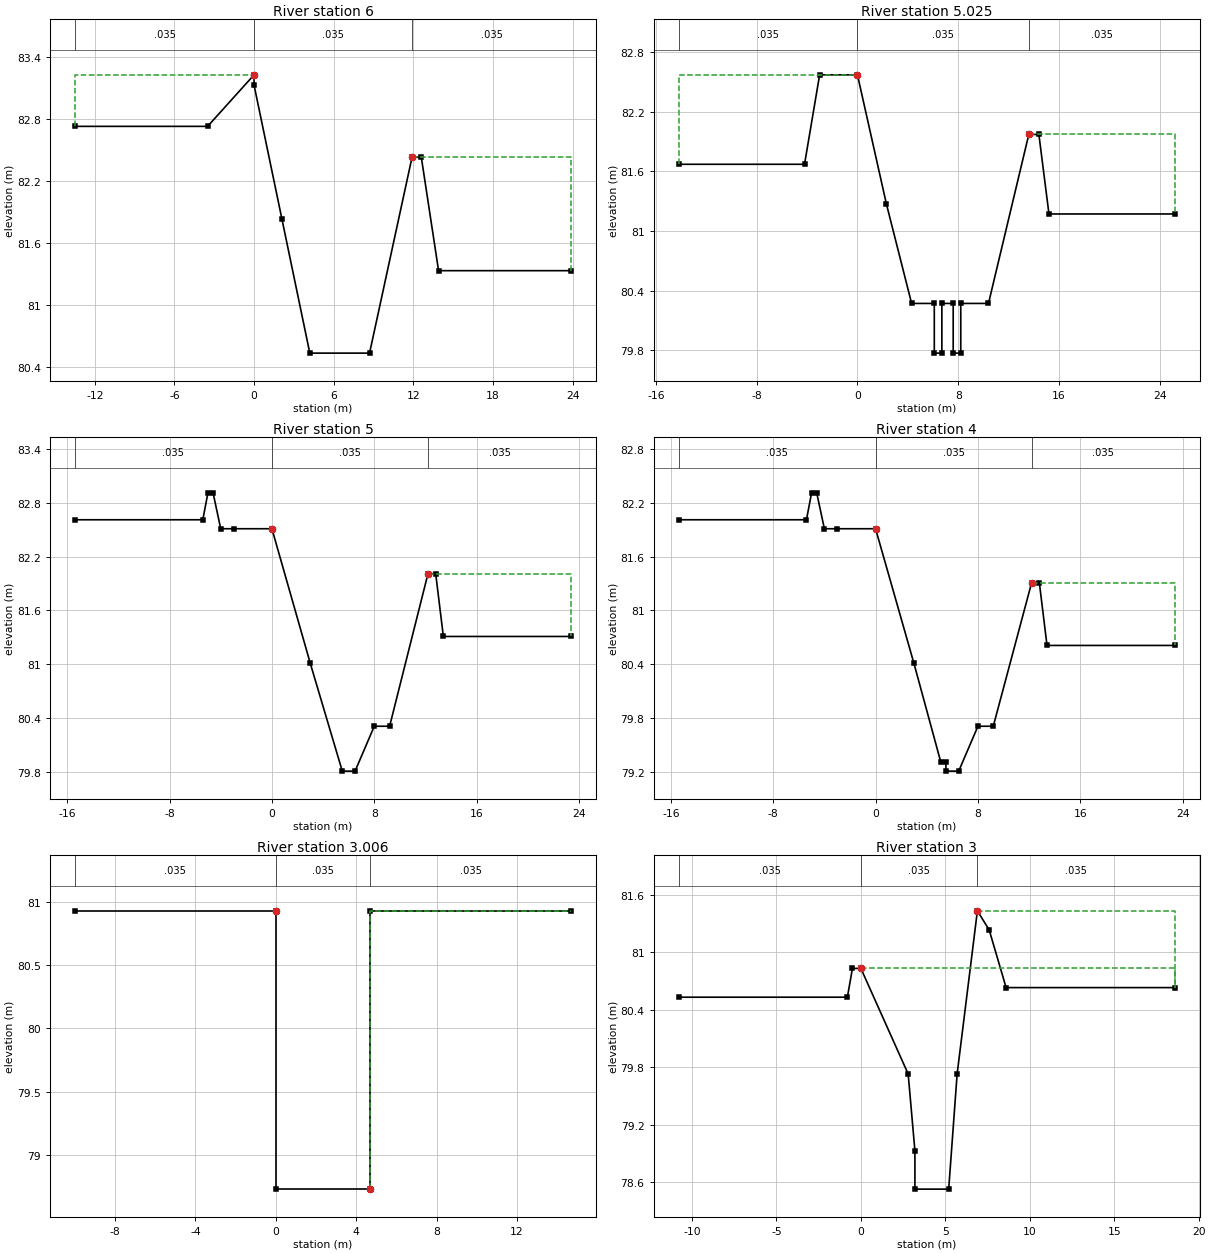
Type RM Length L Ch R = 1 ,6       ,25,25,25
#Sta/Elev= 11
   -13.5   82.73    -3.5   82.73       0   83.23       0   83.13     2.1   81.83
     4.2   80.53     8.7   80.53    11.9   82.43    12.6   82.43    13.9   81.33
    23.9   81.33
#Mann= 3 , 0 , 0
   -13.5    .035       0       0    .035       0    11.9    .035       0
#XS Ineff= 2 , 0
               0   83.23    11.9           82.43
Permanent Ineff=
       F       F
Bank Sta=0,11.9
XS Rating Curve= 0
Exp/Cntr=.3,.1

Type RM Length L Ch R = 1 ,5.025   ,25,25,25
#Sta/Elev= 19
   -14.2   81.67    -4.2   81.67      -3   82.57       0   82.57     2.3   81.27
     4.3   80.27     6.1   80.27     6.1   79.77     6.7   79.77     6.7   80.27
     7.6   80.27     7.6   79.77     8.2   79.77     8.2   80.27    10.4   80.27
    13.6   81.97    14.4   81.97    15.2   81.17    25.2   81.17
#Mann= 3 , 0 , 0
   -14.2    .035       0       0    .035       0    13.6    .035       0
#XS Ineff= 2 , 0
               0   82.57    13.6           81.97
Permanent Ineff=
       F       F
Bank Sta=0,13.6
XS Rating Curve= 0
Exp/Cntr=.3,.1

Type RM Length L Ch R = 1 ,5       ,50,50,50
#Sta/Elev= 16
   -15.4   82.61    -5.4   82.61      -5   82.91    -4.6   82.91      -4   82.51
      -3   82.51       0   82.51       3   81.01     5.5   79.81     6.5   79.81
       8   80.31     9.2   80.31    12.2   82.01    12.8   82.01    13.4   81.31
    23.4   81.31
#Mann= 3 , 0 , 0
   -15.4    .035       0       0    .035       0    12.2    .035       0
#XS Ineff= 2 , 0
               0   82.51    12.2           82.01
Permanent Ineff=
       F       F
Bank Sta=0,12.2
XS Rating Curve= 0
Exp/Cntr=.3,.1

Type RM Length L Ch R = 1 ,4       ,44,44,44
#Sta/Elev= 18
   -15.4   82.01    -5.4   82.01      -5   82.31    -4.6   82.31      -4   81.91
      -3   81.91       0   81.91       3   80.41     5.1   79.31     5.5   79.31
     5.5   79.21     6.5   79.21       8   79.71     9.2   79.71    12.2   81.31
    12.8   81.31    13.4   80.61    23.4   80.61
#Mann= 3 , 0 , 0
   -15.4    .035       0       0    .035       0    12.2    .035       0
#XS Ineff= 2 , 0
               0   81.91    12.2           81.31
Permanent Ineff=
       F       F
Bank Sta=0,12.2
XS Rating Curve= 0
Exp/Cntr=.3,.1

Type RM Length L Ch R = 1 ,3.006   ,6,6,6
#Sta/Elev= 6
     -10   80.93       0   80.93       0   78.73     4.7   78.73     4.7   80.93
    14.7   80.93
#Mann= 3 , 0 , 0
     -10    .035       0       0    .035       0     4.7    .035       0
#XS Ineff= 2 , 0
               0   80.93     4.7           80.93
Permanent Ineff=
       F       F
Bank Sta=0,4.7
XS Rating Curve= 0
Exp/Cntr=.3,.1

Type RM Length L Ch R = 1 ,3       ,50,50,50
#Sta/Elev= 13
   -10.8   80.53     -.8   80.53     -.5   80.83       0   80.83     2.8   79.73
     3.2   78.93     3.2   78.53     5.2   78.53     5.7   79.73     6.9   81.43
     7.6   81.23     8.6   80.63    18.6   80.63
#Mann= 3 , 0 , 0
   -10.8    .035       0       0    .035       0     6.9    .035       0
#XS Ineff= 2 , 0
       0       0   80.83     6.9       0   81.43
Permanent Ineff=
       F       F
Bank Sta=0,6.9
XS Rating Curve= 0
Exp/Cntr=.3,.1

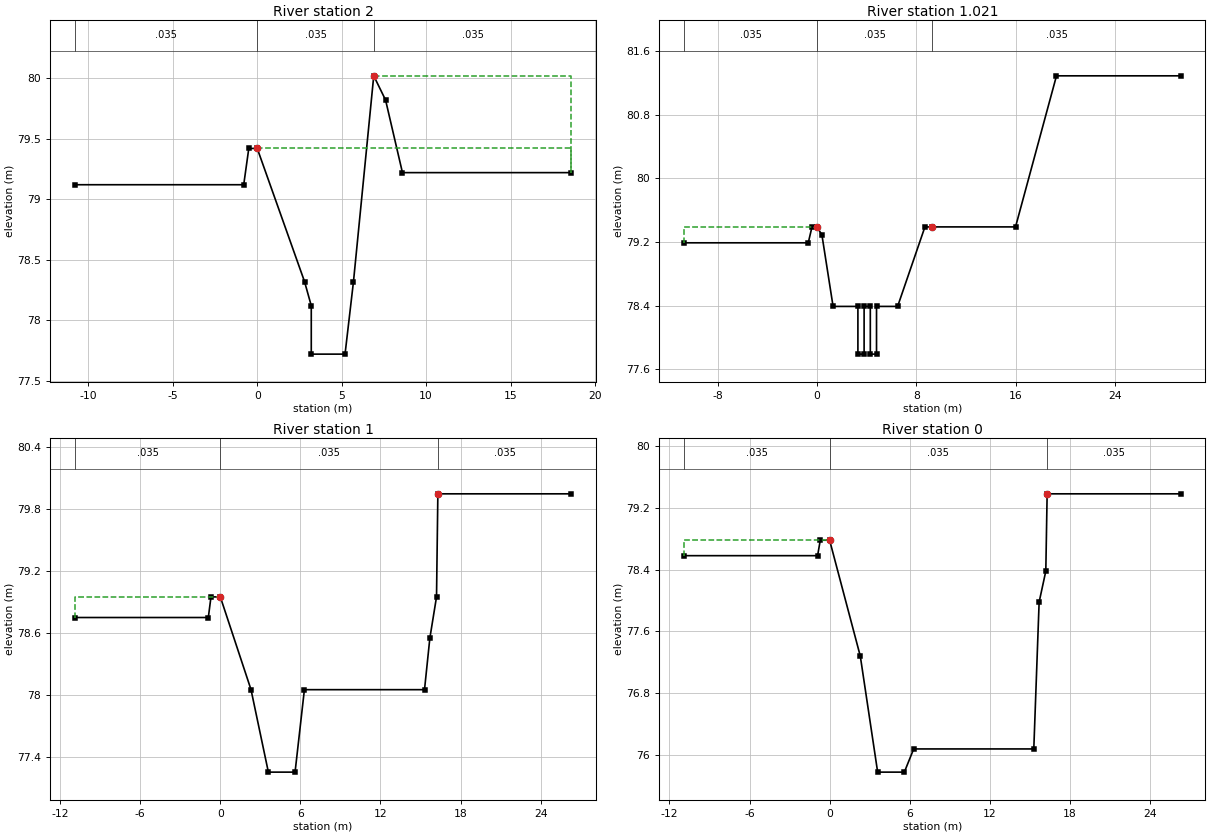
Type RM Length L Ch R = 1 ,2       ,29,29,29
#Sta/Elev= 13
   -10.8   79.12     -.8   79.12     -.5   79.42       0   79.42     2.8   78.32
     3.2   78.12     3.2   77.72     5.2   77.72     5.7   78.32     6.9   80.02
     7.6   79.82     8.6   79.22    18.6   79.22
#Mann= 3 , 0 , 0
   -10.8    .035       0       0    .035       0     6.9    .035       0
#XS Ineff= 2 , 0
       0       0   79.42     6.9       0   80.02
Permanent Ineff=
       F       F
Bank Sta=0,6.9
XS Rating Curve= 0
Exp/Cntr=.3,.1

Type RM Length L Ch R = 1 ,1.021   ,21,21,21
#Sta/Elev= 20
   -10.7   79.19     -.7   79.19     -.4   79.39       0   79.39      .4   79.29
     1.3   78.39     3.3   78.39     3.3   77.79     3.8   77.79     3.8   78.39
     4.3   78.39     4.3   77.79     4.8   77.79     4.8   78.39     6.5   78.39
     8.7   79.39     9.3   79.39      16   79.39    19.3   81.29    29.3   81.29
#Mann= 3 , 0 , 0
   -10.7    .035       0       0    .035       0     9.3    .035       0
#XS Ineff= 2 , 0
               0   79.39     9.3           79.39
Permanent Ineff=
       F       F
Bank Sta=0,9.3
XS Rating Curve= 0
Exp/Cntr=.3,.1

Type RM Length L Ch R = 1 ,1       ,50,50,50
#Sta/Elev= 13
   -10.9   78.75     -.9   78.75     -.7   78.95       0   78.95     2.3   78.05
     3.6   77.25     5.6   77.25     6.3   78.05    15.3   78.05    15.7   78.55
    16.2   78.95    16.3   79.95    26.3   79.95
#Mann= 3 , 0 , 0
   -10.9    .035       0       0    .035       0    16.3    .035       0
#XS Ineff= 2 , 0
               0   78.95    16.3           79.95
Permanent Ineff=
       F       F
Bank Sta=0,16.3
XS Rating Curve= 0
Exp/Cntr=.3,.1

Type RM Length L Ch R = 1 ,0       ,0,0,0
#Sta/Elev= 13
   -10.9   78.58     -.9   78.58     -.7   78.78       0   78.78     2.3   77.28
     3.6   75.78     5.6   75.78     6.3   76.08    15.3   76.08    15.7   77.98
    16.2   78.38    16.3   79.38    26.3   79.38
#Mann= 3 , 0 , 0
   -10.9    .035       0       0    .035       0    16.3    .035       0
#XS Ineff= 2 , 0
               0   78.78    16.3           79.38
Permanent Ineff=
       F       F
Bank Sta=0,16.3
XS Rating Curve= 0
Exp/Cntr=.3,.1

Chan Stop Cuts=-1