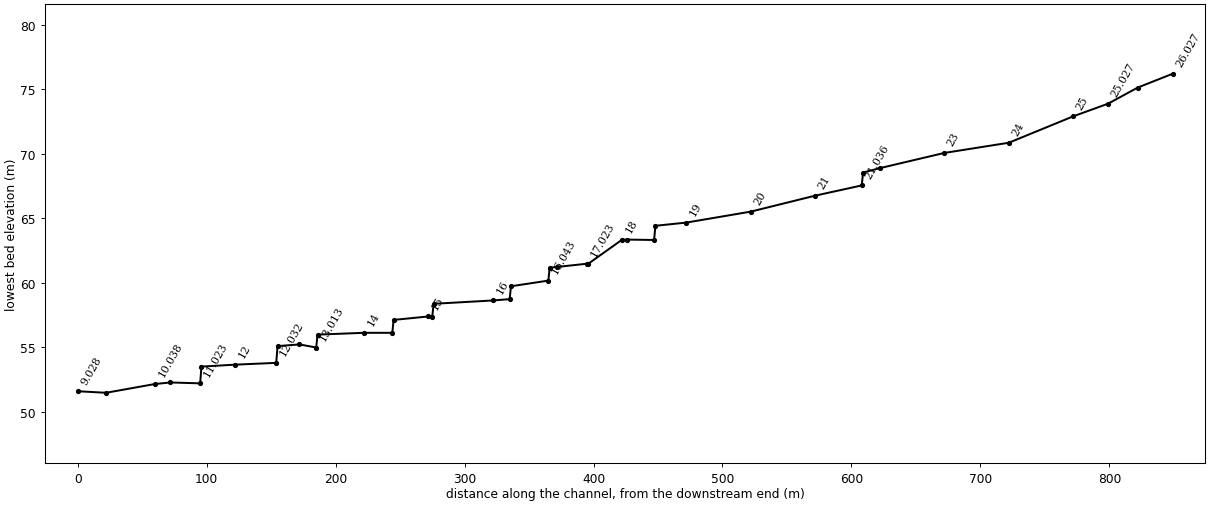
--- ocyerdong-ch.prj (project) ---

Proj Title=ocyerdong-ch
Current Plan=p01
Default Exp/Contr=.3,.1
SI Units
Geom File=g01
Flow File=f01
Plan File=p01
Y Axis Title=Elevation
X Axis Title(PF)=Main Channel Distance
X Axis Title(XS)=Station
BEGIN DESCRIPTION:
           BACK WATER COMPUTATION
      APPLICATION OF HEC-2 BY Samju Construction Engineering
      ocyerdong-ch: 10,20,30,50,80 yr
END DESCRIPTION:
DSS Export Rating Curves= 0
DSS Export Rating Curve Sorted= 0
DSS Export Volume Flow Curves= 0
DXF OffsetX= 0
DXF OffsetY= 0
DXF ScaleX= 1
DXF ScaleY= 10

--- ocyerdong-ch.p01 (plan) ---

Plan Title=Imported Plan 01
Version=Version 3.0.1  Mar 2001
Short Identifier=Imported Pla
Geom File=g01
Flow File=f01
Subcritical Flow
K Sum by GR= 0
Std Step Tol= 0.003
Critical Tol= 0.003
Num of Std Step Trials= 20
Max Error Tol= 0.1
Flow Tol Ratio= 0.001
Split Flow NTrial= 30
Split Flow Tol= 0.02
Split Flow Ratio= 0.02
Log Output Level= 0
Friction Slope Method= 1
Unsteady Friction Slope Method= 2
Parabolic Critical Depth
Global Vel Dist= 0 , 0 , 0
Global Log Level= 0
CheckData=True
Encroach Param=-1 ,0,0, 0
Computation Interval=1HOUR
Output Interval=1HOUR
Run HTab= 0
Run UNet= 0
Run PostProcess= 0
UNET Theta= 1
UNET ZTol= 0.02
UNET ZSATol= 0.1
UNET MxIter= 20
UNET MaxInSteps= 20
UNET DtIC= 0
UNET DtMin= 0
UNET MaxCRTS= 20
UNET WFStab= 2
UNET SFStab= 1
UNET WFX= 1
UNET SFX= 1
UNET Convert EG Bridges=-1
UNET Use Existing IB Tables=-1
Instantaneous Interval=1HOUR
Write IC File= 0
Write Velocity= 0
Write Detailed= 0

--- ocyerdong-ch.f01 (steady flow) ---

Flow Title=Imported Flow 01
Version=Version 3.0.1  Mar 2001
Number of Profiles= 5
Profile Names=PF 1,PF 2,PF 3,PF 4,PF 5
River Rch & RM=RIVER-1,Reach-1         ,26.027
     180     200     220     230     240
Boundary for River Rch & Prof#=RIVER-1,Reach-1         , 1
Up Type= 0
Dn Type= 3
Dn Slope=.0109
Boundary for River Rch & Prof#=RIVER-1,Reach-1         , 2
Up Type= 0
Dn Type= 3
Dn Slope=.0109
Boundary for River Rch & Prof#=RIVER-1,Reach-1         , 3
Up Type= 0
Dn Type= 3
Dn Slope=.0109
Boundary for River Rch & Prof#=RIVER-1,Reach-1         , 4
Up Type= 0
Dn Type= 3
Dn Slope=.0109
Boundary for River Rch & Prof#=RIVER-1,Reach-1         , 5
Up Type= 0
Dn Type= 3
Dn Slope=.0109
DSS Import GetInterval= 0
DSS Import GetPeak= 0
DSS Import FillOption= 0

--- ocyerdong-ch.g01 (geometry) ---

Geom Title=Imported Geom 01
Version=Version 3.0.1  Mar 2001

River Reach=RIVER-1         ,Reach-1
Reach XY= 2
              .5             .95              .5             .05

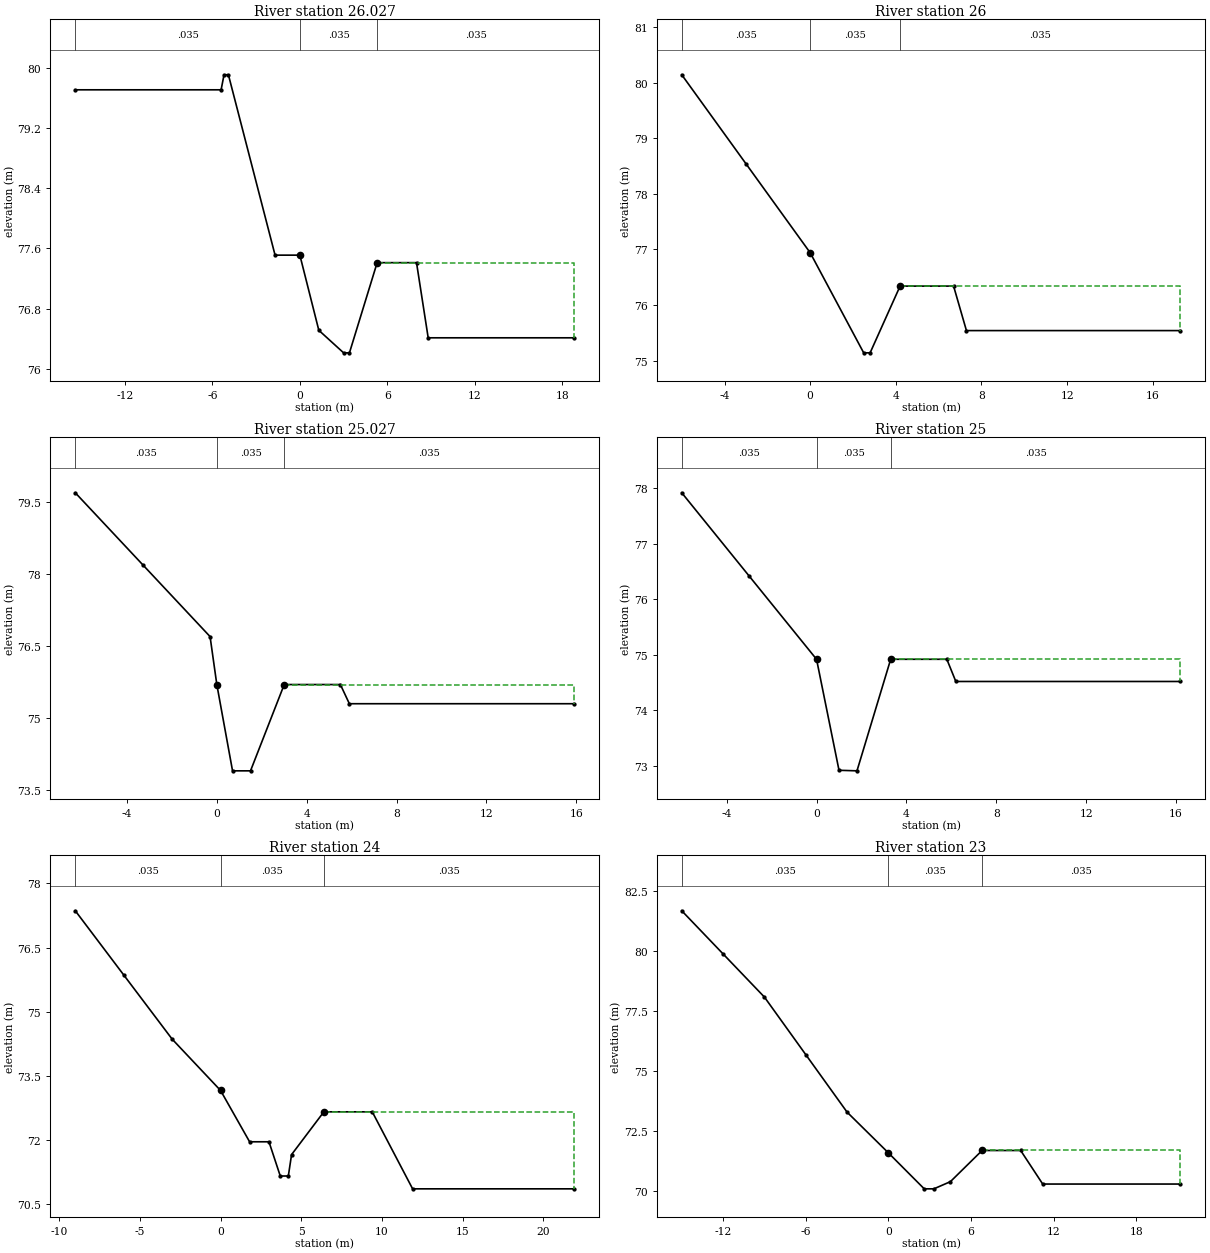
Type RM Length L Ch R = 1 ,26.027  ,27,27,27
#Sta/Elev= 13
   -15.4   79.71    -5.4   79.71    -5.2   79.91    -4.9   79.91    -1.7   77.51
       0   77.51     1.3   76.51       3   76.21     3.4   76.21     5.3   77.41
       8   77.41     8.8   76.41    18.8   76.41
#Mann= 3 , 0 , 0
   -15.4    .035       0       0    .035       0     5.3    .035       0
#XS Ineff= 2 , 0
               0   77.51     5.3           77.41
Permanent Ineff=
       F       F
Bank Sta=0,5.3
XS Rating Curve= 0
Exp/Cntr=.3,.1

Type RM Length L Ch R = 1 ,26      ,23,23,23
#Sta/Elev= 9
      -6   80.14      -3   78.54       0   76.94     2.5   75.14     2.8   75.14
     4.2   76.34     6.7   76.34     7.3   75.54    17.3   75.54
#Mann= 3 , 0 , 0
      -6    .035       0       0    .035       0     4.2    .035       0
#XS Ineff= 2 , 0
               0   76.94     4.2           76.34
Permanent Ineff=
       F       F
Bank Sta=0,4.2
XS Rating Curve= 0
Exp/Cntr=.3,.1

Type RM Length L Ch R = 1 ,25.027  ,27,27,27
#Sta/Elev= 10
    -6.3   79.69    -3.3   78.19     -.3   76.69       0   75.69      .7   73.89
     1.5   73.89       3   75.69     5.5   75.69     5.9   75.29    15.9   75.29
#Mann= 3 , 0 , 0
    -6.3    .035       0       0    .035       0       3    .035       0
#XS Ineff= 2 , 0
               0   75.69       3           75.69
Permanent Ineff=
       F       F
Bank Sta=0,3
XS Rating Curve= 0
Exp/Cntr=.3,.1

Type RM Length L Ch R = 1 ,25      ,50,50,50
#Sta/Elev= 9
      -6   77.92      -3   76.42       0   74.92       1   72.92     1.8   72.91
     3.3   74.92     5.8   74.92     6.2   74.52    16.2   74.52
#Mann= 3 , 0 , 0
      -6    .035       0       0    .035       0     3.3    .035       0
#XS Ineff= 2 , 0
               0   74.92     3.3           74.92
Permanent Ineff=
       F       F
Bank Sta=0,3.3
XS Rating Curve= 0
Exp/Cntr=.3,.1

Type RM Length L Ch R = 1 ,24      ,50,50,50
#Sta/Elev= 13
      -9   77.36      -6   75.86      -3   74.36       0   73.16     1.8   71.96
       3   71.96     3.7   71.16     4.2   71.16     4.4   71.66     6.4   72.66
     9.4   72.66    11.9   70.86    21.9   70.86
#Mann= 3 , 0 , 0
      -9    .035       0       0    .035       0     6.4    .035       0
#XS Ineff= 2 , 0
               0   73.16     6.4           72.66
Permanent Ineff=
       F       F
Bank Sta=0,6.4
XS Rating Curve= 0
Exp/Cntr=.3,.1

Type RM Length L Ch R = 1 ,23      ,50,50,50
#Sta/Elev= 13
     -15   81.67     -12   79.87      -9   78.07      -6   75.67      -3   73.27
       0   71.57     2.6   70.07     3.3   70.07     4.5   70.37     6.8   71.67
     9.6   71.67    11.2   70.27    21.2   70.27
#Mann= 3 , 0 , 0
     -15    .035       0       0    .035       0     6.8    .035       0
#XS Ineff= 2 , 0
               0   71.57     6.8           71.67
Permanent Ineff=
       F       F
Bank Sta=0,6.8
XS Rating Curve= 0
Exp/Cntr=.3,.1

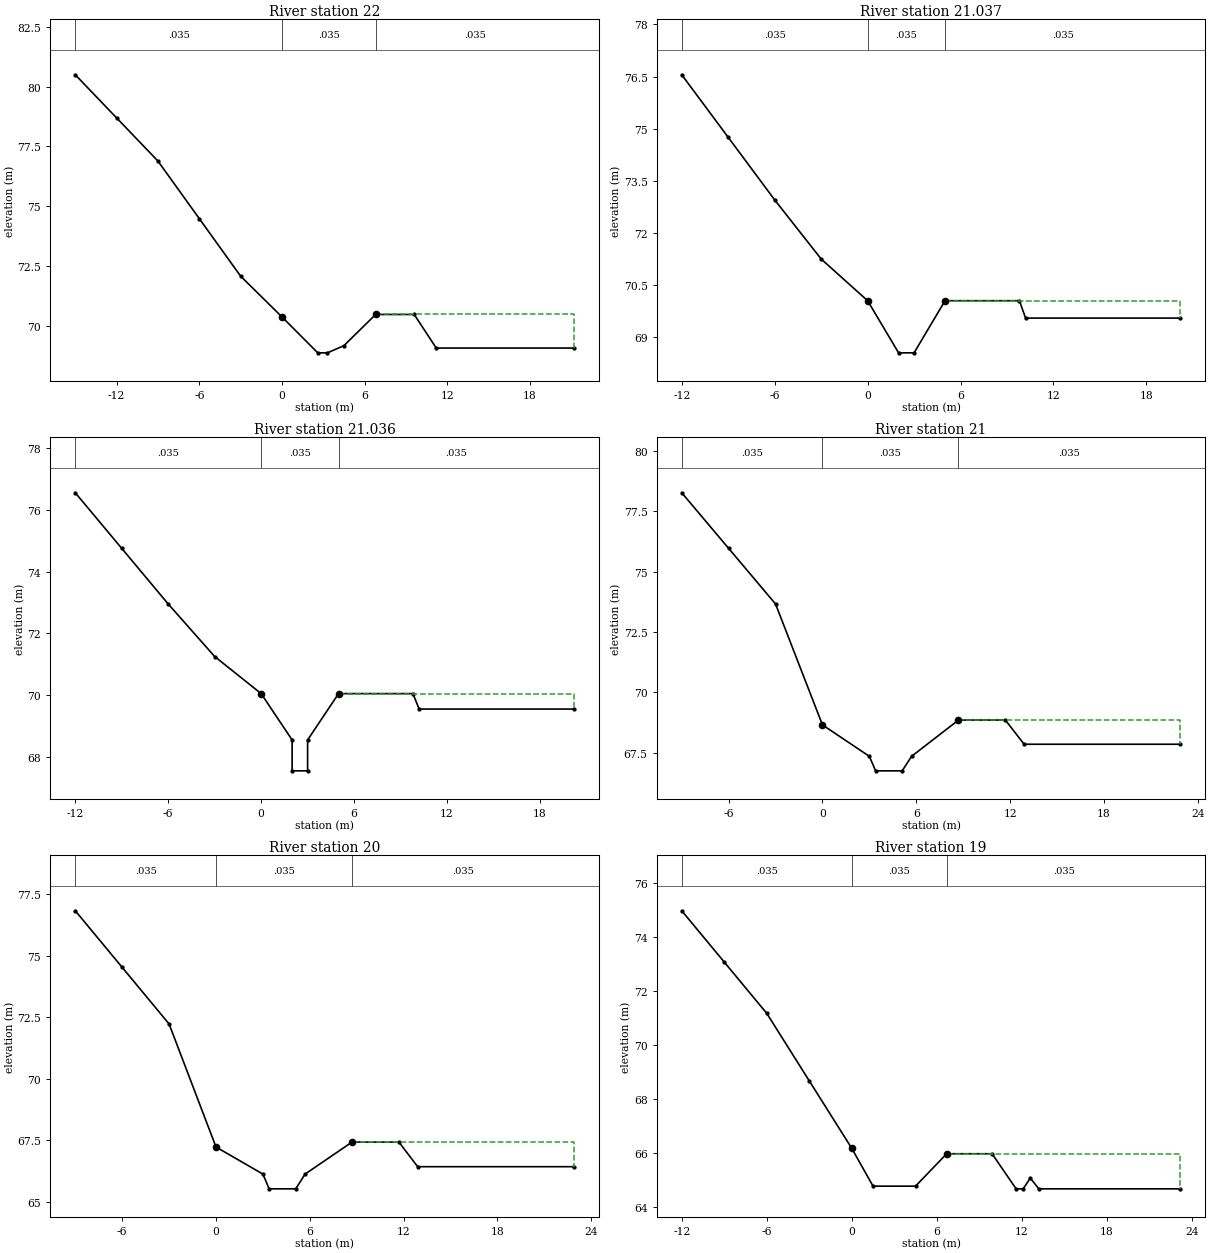
Type RM Length L Ch R = 1 ,22      ,13,13,13
#Sta/Elev= 13
     -15   80.49     -12   78.69      -9   76.89      -6   74.49      -3   72.09
       0   70.39     2.6   68.89     3.3   68.89     4.5   69.19     6.8   70.49
     9.6   70.49    11.2   69.09    21.2   69.09
#Mann= 3 , 0 , 0
     -15    .035       0       0    .035       0     6.8    .035       0
#XS Ineff= 2 , 0
               0   70.39     6.8           70.49
Permanent Ineff=
       F       F
Bank Sta=0,6.8
XS Rating Curve= 0
Exp/Cntr=.3,.1

Type RM Length L Ch R = 1 ,21.037  ,1,1,1
#Sta/Elev= 11
     -12   76.55      -9   74.75      -6   72.95      -3   71.25       0   70.05
       2   68.55       3   68.55       5   70.05     9.8   70.05    10.2   69.55
    20.2   69.55
#Mann= 3 , 0 , 0
     -12    .035       0       0    .035       0       5    .035       0
#XS Ineff= 2 , 0
               0   70.05       5           70.05
Permanent Ineff=
       F       F
Bank Sta=0,5
XS Rating Curve= 0
Exp/Cntr=.3,.1

Type RM Length L Ch R = 1 ,21.036  ,36,36,36
#Sta/Elev= 13
     -12   76.55      -9   74.75      -6   72.95      -3   71.25       0   70.05
       2   68.55       2   67.55       3   67.55       3   68.55       5   70.05
     9.8   70.05    10.2   69.55    20.2   69.55
#Mann= 3 , 0 , 0
     -12    .035       0       0    .035       0       5    .035       0
#XS Ineff= 2 , 0
               0   70.05       5           70.05
Permanent Ineff=
       F       F
Bank Sta=0,5
XS Rating Curve= 0
Exp/Cntr=.3,.1

Type RM Length L Ch R = 1 ,21      ,50,50,50
#Sta/Elev= 12
      -9   78.26      -6   75.96      -3   73.66       0   68.66       3   67.36
     3.4   66.76     5.1   66.76     5.7   67.36     8.7   68.86    11.7   68.86
    12.9   67.86    22.9   67.86
#Mann= 3 , 0 , 0
      -9    .035       0       0    .035       0     8.7    .035       0
#XS Ineff= 2 , 0
               0   68.66     8.7           68.86
Permanent Ineff=
       F       F
Bank Sta=0,8.7
XS Rating Curve= 0
Exp/Cntr=.3,.1

Type RM Length L Ch R = 1 ,20      ,50,50,50
#Sta/Elev= 12
      -9   76.82      -6   74.52      -3   72.22       0   67.22       3   66.12
     3.4   65.52     5.1   65.52     5.7   66.12     8.7   67.42    11.7   67.42
    12.9   66.42    22.9   66.42
#Mann= 3 , 0 , 0
      -9    .035       0       0    .035       0     8.7    .035       0
#XS Ineff= 2 , 0
               0   67.22     8.7           67.42
Permanent Ineff=
       F       F
Bank Sta=0,8.7
XS Rating Curve= 0
Exp/Cntr=.3,.1

Type RM Length L Ch R = 1 ,19      ,24,24,24
#Sta/Elev= 14
     -12   74.97      -9   73.07      -6   71.17      -3   68.67       0   66.17
     1.5   64.77     4.5   64.77     6.7   65.97     9.9   65.97    11.6   64.67
    12.1   64.67    12.6   65.07    13.2   64.67    23.2   64.67
#Mann= 3 , 0 , 0
     -12    .035       0       0    .035       0     6.7    .035       0
#XS Ineff= 2 , 0
               0   66.17     6.7           65.97
Permanent Ineff=
       F       F
Bank Sta=0,6.7
XS Rating Curve= 0
Exp/Cntr=.3,.1

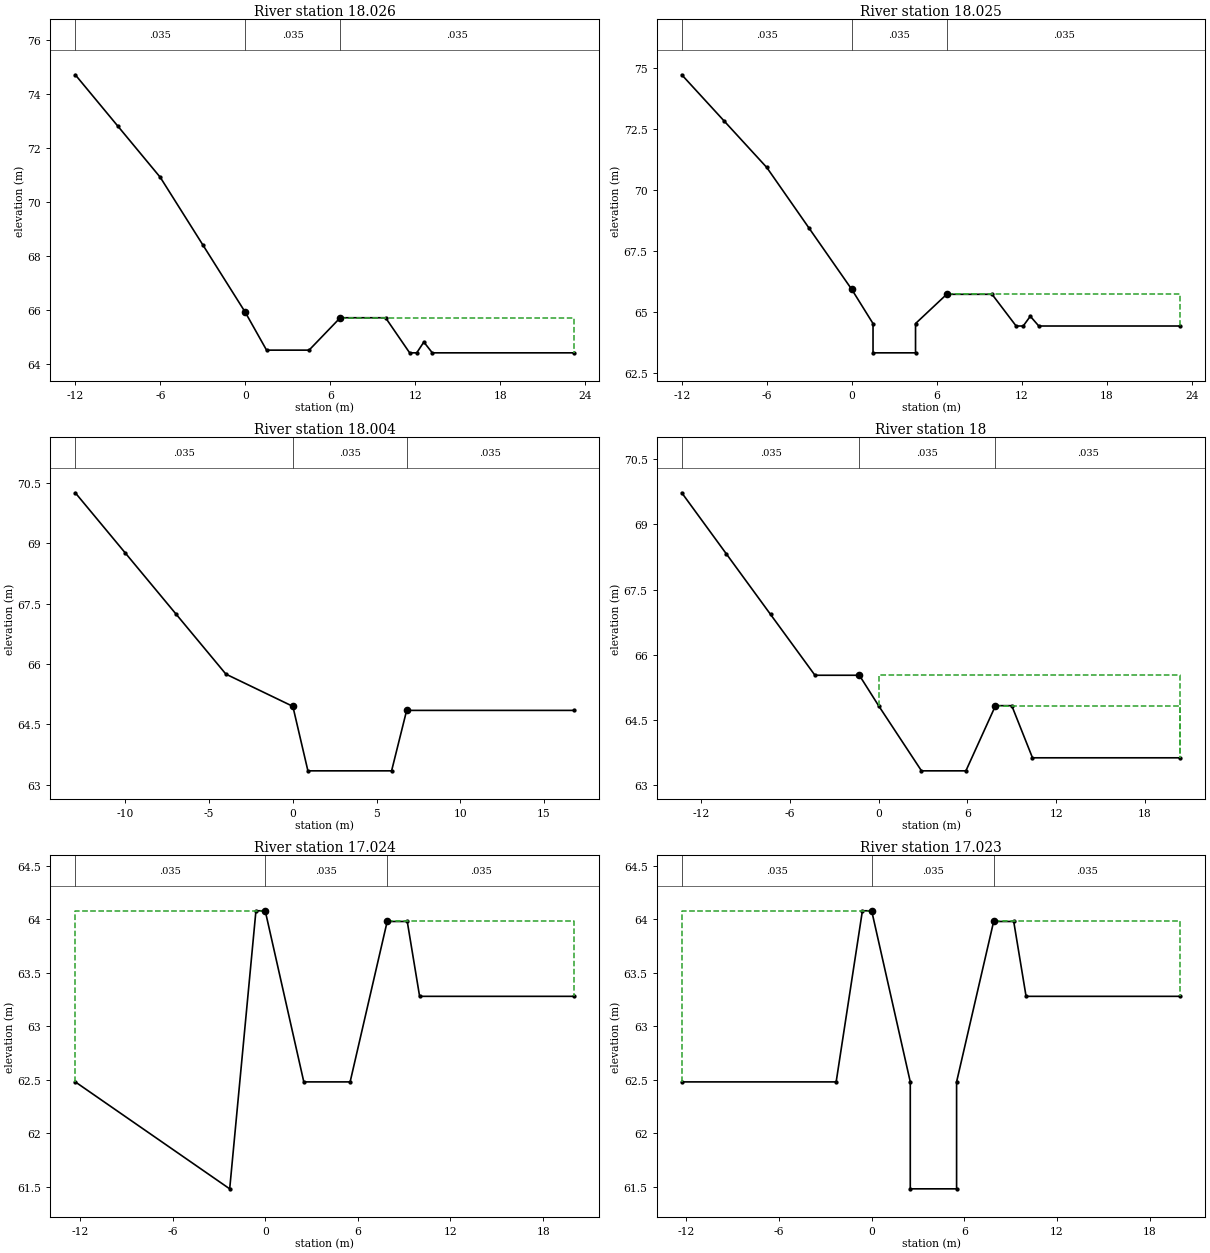
Type RM Length L Ch R = 1 ,18.026  ,1,1,1
#Sta/Elev= 14
     -12   74.72      -9   72.82      -6   70.92      -3   68.42       0   65.92
     1.5   64.52     4.5   64.52     6.7   65.72     9.9   65.72    11.6   64.42
    12.1   64.42    12.6   64.82    13.2   64.42    23.2   64.42
#Mann= 3 , 0 , 0
     -12    .035       0       0    .035       0     6.7    .035       0
#XS Ineff= 2 , 0
               0   65.92     6.7           65.72
Permanent Ineff=
       F       F
Bank Sta=0,6.7
XS Rating Curve= 0
Exp/Cntr=.3,.1

Type RM Length L Ch R = 1 ,18.025  ,21,21,21
#Sta/Elev= 16
     -12   74.72      -9   72.82      -6   70.92      -3   68.42       0   65.92
     1.5   64.52     1.5   63.32     4.5   63.32     4.5   64.52     6.7   65.72
     9.9   65.72    11.6   64.42    12.1   64.42    12.6   64.82    13.2   64.42
    23.2   64.42
#Mann= 3 , 0 , 0
     -12    .035       0       0    .035       0     6.7    .035       0
#XS Ineff= 2 , 0
               0   65.92     6.7           65.72
Permanent Ineff=
       F       F
Bank Sta=0,6.7
XS Rating Curve= 0
Exp/Cntr=.3,.1

Type RM Length L Ch R = 1 ,18.004  ,4,4,4
#Sta/Elev= 9
     -13   70.25     -10   68.75      -7   67.25      -4   65.75       0   64.95
      .9   63.35     5.9   63.35     6.8   64.85    16.8   64.85
#Mann= 3 , 0 , 0
     -13    .035       0       0    .035       0     6.8    .035       0
#XS Ineff= 2 , 0
               0   64.95     6.8           64.85
Permanent Ineff=
       F       F
Bank Sta=0,6.8
XS Rating Curve= 0
Exp/Cntr=.3,.1

Type RM Length L Ch R = 1 ,18      ,26,26,26
#Sta/Elev= 12
   -13.3   69.73   -10.3   68.33    -7.3   66.93    -4.3   65.53    -1.3   65.53
       0   64.83     2.9   63.33     5.9   63.33     7.9   64.83       9   64.83
    10.4   63.63    20.4   63.63
#Mann= 3 , 0 , 0
   -13.3    .035       0    -1.3    .035       0     7.9    .035       0
#XS Ineff= 2 , 0
       0    -1.3   65.53     7.9       0   64.83
Permanent Ineff=
       F       F
Bank Sta=-1.3,7.9
XS Rating Curve= 0
Exp/Cntr=.3,.1

Type RM Length L Ch R = 1 ,17.024  ,1,1,1
#Sta/Elev= 10
   -12.3   62.48    -2.3   61.48     -.6   64.08       0   64.08     2.5   62.48
     5.5   62.48     7.9   63.98     9.2   63.98      10   63.28      20   63.28
#Mann= 3 , 0 , 0
   -12.3    .035       0       0    .035       0     7.9    .035       0
#XS Ineff= 2 , 0
               0   64.08     7.9           63.98
Permanent Ineff=
       F       F
Bank Sta=0,7.9
XS Rating Curve= 0
Exp/Cntr=.3,.1

Type RM Length L Ch R = 1 ,17.023  ,23,23,23
#Sta/Elev= 12
   -12.3   62.48    -2.3   62.48     -.6   64.08       0   64.08     2.5   62.48
     2.5   61.48     5.5   61.48     5.5   62.48     7.9   63.98     9.2   63.98
      10   63.28      20   63.28
#Mann= 3 , 0 , 0
   -12.3    .035       0       0    .035       0     7.9    .035       0
#XS Ineff= 2 , 0
               0   64.08     7.9           63.98
Permanent Ineff=
       F       F
Bank Sta=0,7.9
XS Rating Curve= 0
Exp/Cntr=.3,.1

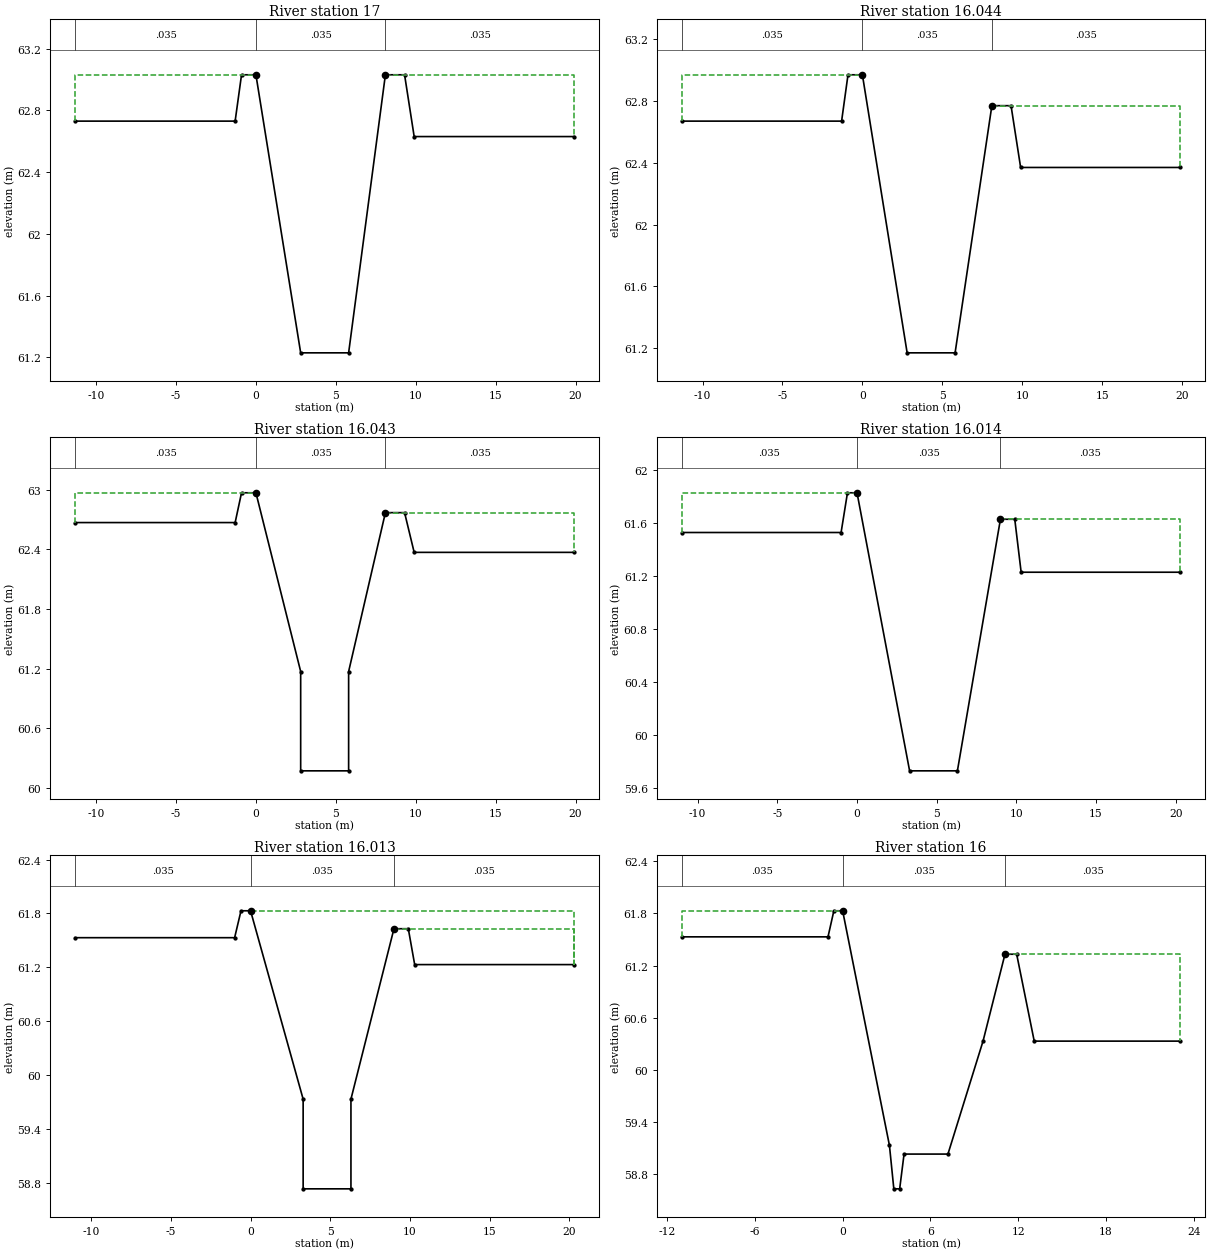
Type RM Length L Ch R = 1 ,17      ,6,6,6
#Sta/Elev= 10
   -11.3   62.73    -1.3   62.73     -.9   63.03       0   63.03     2.8   61.23
     5.8   61.23     8.1   63.03     9.3   63.03     9.9   62.63    19.9   62.63
#Mann= 3 , 0 , 0
   -11.3    .035       0       0    .035       0     8.1    .035       0
#XS Ineff= 2 , 0
               0   63.03     8.1           63.03
Permanent Ineff=
       F       F
Bank Sta=0,8.1
XS Rating Curve= 0
Exp/Cntr=.3,.1

Type RM Length L Ch R = 1 ,16.044  ,1,1,1
#Sta/Elev= 10
   -11.3   62.67    -1.3   62.67     -.9   62.97       0   62.97     2.8   61.17
     5.8   61.17     8.1   62.77     9.3   62.77     9.9   62.37    19.9   62.37
#Mann= 3 , 0 , 0
   -11.3    .035       0       0    .035       0     8.1    .035       0
#XS Ineff= 2 , 0
               0   62.97     8.1           62.77
Permanent Ineff=
       F       F
Bank Sta=0,8.1
XS Rating Curve= 0
Exp/Cntr=.3,.1

Type RM Length L Ch R = 1 ,16.043  ,29,29,29
#Sta/Elev= 12
   -11.3   62.67    -1.3   62.67     -.9   62.97       0   62.97     2.8   61.17
     2.8   60.17     5.8   60.17     5.8   61.17     8.1   62.77     9.3   62.77
     9.9   62.37    19.9   62.37
#Mann= 3 , 0 , 0
   -11.3    .035       0       0    .035       0     8.1    .035       0
#XS Ineff= 2 , 0
               0   62.97     8.1           62.77
Permanent Ineff=
       F       F
Bank Sta=0,8.1
XS Rating Curve= 0
Exp/Cntr=.3,.1

Type RM Length L Ch R = 1 ,16.014  ,1,1,1
#Sta/Elev= 10
     -11   61.53      -1   61.53     -.6   61.83       0   61.83     3.3   59.73
     6.3   59.73       9   61.63     9.9   61.63    10.3   61.23    20.3   61.23
#Mann= 3 , 0 , 0
     -11    .035       0       0    .035       0       9    .035       0
#XS Ineff= 2 , 0
               0   61.83       9           61.63
Permanent Ineff=
       F       F
Bank Sta=0,9
XS Rating Curve= 0
Exp/Cntr=.3,.1

Type RM Length L Ch R = 1 ,16.013  ,13,13,13
#Sta/Elev= 12
     -11   61.53      -1   61.53     -.6   61.83       0   61.83     3.3   59.73
     3.3   58.73     6.3   58.73     6.3   59.73       9   61.63     9.9   61.63
    10.3   61.23    20.3   61.23
#Mann= 3 , 0 , 0
     -11    .035       0       0    .035       0       9    .035       0
#XS Ineff= 2 , 0
       0       0   61.83       9       0   61.63
Permanent Ineff=
       F       F
Bank Sta=0,9
XS Rating Curve= 0
Exp/Cntr=.3,.1

Type RM Length L Ch R = 1 ,16      ,46,46,46
#Sta/Elev= 14
     -11   61.53      -1   61.53     -.6   61.83       0   61.83     3.2   59.13
     3.5   58.63     3.9   58.63     4.2   59.03     7.2   59.03     9.6   60.33
    11.1   61.33    11.9   61.33    13.1   60.33    23.1   60.33
#Mann= 3 , 0 , 0
     -11    .035       0       0    .035       0    11.1    .035       0
#XS Ineff= 2 , 0
               0   61.83    11.1           61.33
Permanent Ineff=
       F       F
Bank Sta=0,11.1
XS Rating Curve= 0
Exp/Cntr=.3,.1

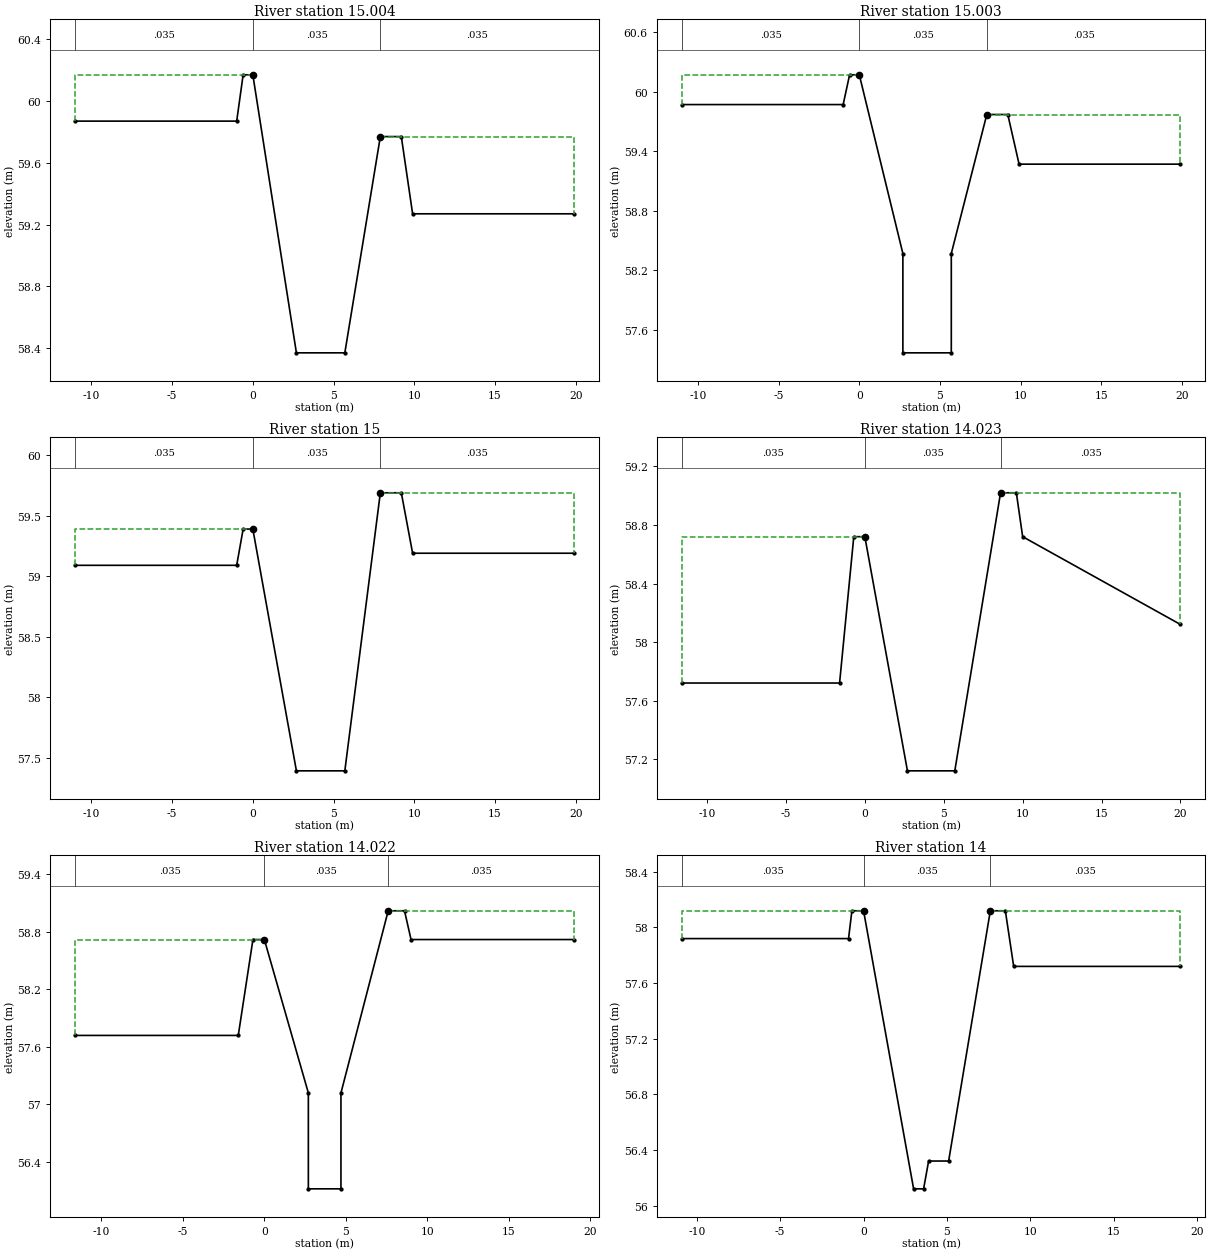
Type RM Length L Ch R = 1 ,15.004  ,1,1,1
#Sta/Elev= 10
     -11   59.87      -1   59.87     -.6   60.17       0   60.17     2.7   58.37
     5.7   58.37     7.9   59.77     9.2   59.77     9.9   59.27    19.9   59.27
#Mann= 3 , 0 , 0
     -11    .035       0       0    .035       0     7.9    .035       0
#XS Ineff= 2 , 0
               0   60.17     7.9           59.77
Permanent Ineff=
       F       F
Bank Sta=0,7.9
XS Rating Curve= 0
Exp/Cntr=.3,.1

Type RM Length L Ch R = 1 ,15.003  ,3,3,3
#Sta/Elev= 12
     -11   59.87      -1   59.87     -.6   60.17       0   60.17     2.7   58.37
     2.7   57.37     5.7   57.37     5.7   58.37     7.9   59.77     9.2   59.77
     9.9   59.27    19.9   59.27
#Mann= 3 , 0 , 0
     -11    .035       0       0    .035       0     7.9    .035       0
#XS Ineff= 2 , 0
               0   60.17     7.9           59.77
Permanent Ineff=
       F       F
Bank Sta=0,7.9
XS Rating Curve= 0
Exp/Cntr=.3,.1

Type RM Length L Ch R = 1 ,15      ,27,27,27
#Sta/Elev= 10
     -11   59.09      -1   59.09     -.6   59.39       0   59.39     2.7   57.39
     5.7   57.39     7.9   59.69     9.2   59.69     9.9   59.19    19.9   59.19
#Mann= 3 , 0 , 0
     -11    .035       0       0    .035       0     7.9    .035       0
#XS Ineff= 2 , 0
               0   59.39     7.9           59.69
Permanent Ineff=
       F       F
Bank Sta=0,7.9
XS Rating Curve= 0
Exp/Cntr=.3,.1

Type RM Length L Ch R = 1 ,14.023  ,1,1,1
#Sta/Elev= 10
   -11.6   57.72    -1.6   57.72     -.7   58.72       0   58.72     2.7   57.12
     5.7   57.12     8.6   59.02     9.6   59.02      10   58.72      20   58.12
#Mann= 3 , 0 , 0
   -11.6    .035       0       0    .035       0     8.6    .035       0
#XS Ineff= 2 , 0
               0   58.72     8.6           59.02
Permanent Ineff=
       F       F
Bank Sta=0,8.6
XS Rating Curve= 0
Exp/Cntr=.3,.1

Type RM Length L Ch R = 1 ,14.022  ,22,22,22
#Sta/Elev= 12
   -11.6   57.72    -1.6   57.72     -.7   58.72       0   58.72     2.7   57.12
     2.7   56.12     4.7   56.12     4.7   57.12     7.6   59.02     8.6   59.02
       9   58.72      19   58.72
#Mann= 3 , 0 , 0
   -11.6    .035       0       0    .035       0     7.6    .035       0
#XS Ineff= 2 , 0
               0   58.72     7.6           59.02
Permanent Ineff=
       F       F
Bank Sta=0,7.6
XS Rating Curve= 0
Exp/Cntr=.3,.1

Type RM Length L Ch R = 1 ,14      ,36,36,36
#Sta/Elev= 12
   -10.9   57.92     -.9   57.92     -.7   58.12       0   58.12       3   56.12
     3.6   56.12     3.9   56.32     5.1   56.32     7.6   58.12     8.5   58.12
       9   57.72      19   57.72
#Mann= 3 , 0 , 0
   -10.9    .035       0       0    .035       0     7.6    .035       0
#XS Ineff= 2 , 0
               0   58.12     7.6           58.12
Permanent Ineff=
       F       F
Bank Sta=0,7.6
XS Rating Curve= 0
Exp/Cntr=.3,.1

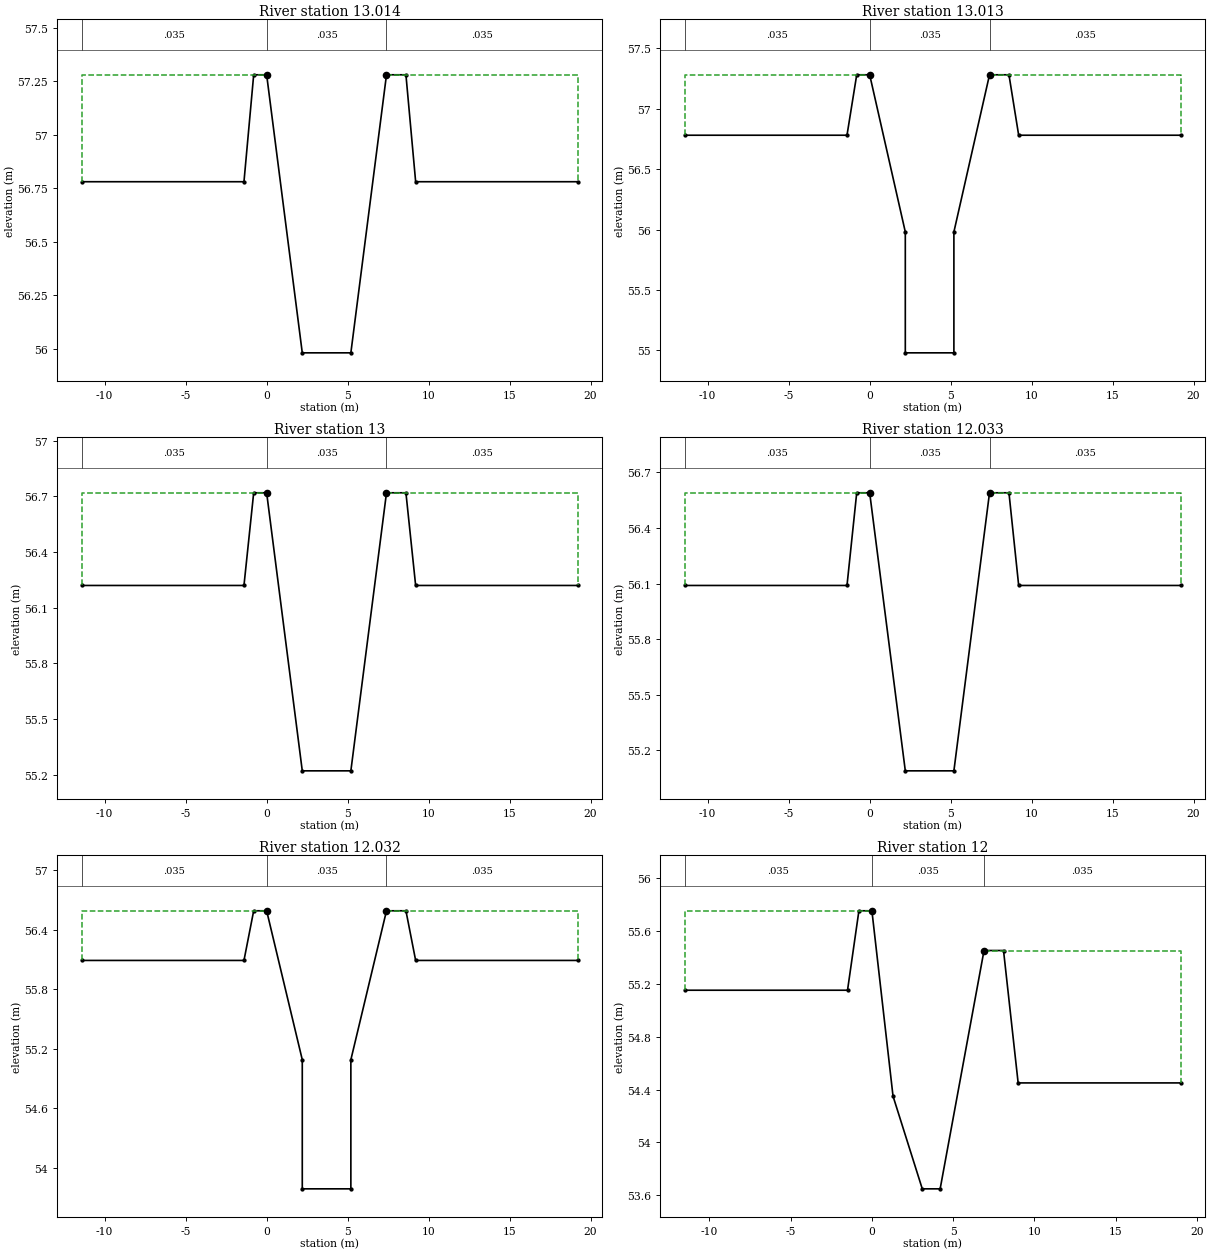
Type RM Length L Ch R = 1 ,13.014  ,1,1,1
#Sta/Elev= 10
   -11.4   56.78    -1.4   56.78     -.8   57.28       0   57.28     2.2   55.98
     5.2   55.98     7.4   57.28     8.6   57.28     9.2   56.78    19.2   56.78
#Mann= 3 , 0 , 0
   -11.4    .035       0       0    .035       0     7.4    .035       0
#XS Ineff= 2 , 0
               0   57.28     7.4           57.28
Permanent Ineff=
       F       F
Bank Sta=0,7.4
XS Rating Curve= 0
Exp/Cntr=.3,.1

Type RM Length L Ch R = 1 ,13.013  ,13,13,13
#Sta/Elev= 12
   -11.4   56.78    -1.4   56.78     -.8   57.28       0   57.28     2.2   55.98
     2.2   54.98     5.2   54.98     5.2   55.98     7.4   57.28     8.6   57.28
     9.2   56.78    19.2   56.78
#Mann= 3 , 0 , 0
   -11.4    .035       0       0    .035       0     7.4    .035       0
#XS Ineff= 2 , 0
               0   57.28     7.4           57.28
Permanent Ineff=
       F       F
Bank Sta=0,7.4
XS Rating Curve= 0
Exp/Cntr=.3,.1

Type RM Length L Ch R = 1 ,13      ,17,17,17
#Sta/Elev= 10
   -11.4   56.22    -1.4   56.22     -.8   56.72       0   56.72     2.2   55.22
     5.2   55.22     7.4   56.72     8.6   56.72     9.2   56.22    19.2   56.22
#Mann= 3 , 0 , 0
   -11.4    .035       0       0    .035       0     7.4    .035       0
#XS Ineff= 2 , 0
               0   56.72     7.4           56.72
Permanent Ineff=
       F       F
Bank Sta=0,7.4
XS Rating Curve= 0
Exp/Cntr=.3,.1

Type RM Length L Ch R = 1 ,12.033  ,1,1,1
#Sta/Elev= 10
   -11.4   56.09    -1.4   56.09     -.8   56.59       0   56.59     2.2   55.09
     5.2   55.09     7.4   56.59     8.6   56.59     9.2   56.09    19.2   56.09
#Mann= 3 , 0 , 0
   -11.4    .035       0       0    .035       0     7.4    .035       0
#XS Ineff= 2 , 0
               0   56.59     7.4           56.59
Permanent Ineff=
       F       F
Bank Sta=0,7.4
XS Rating Curve= 0
Exp/Cntr=.3,.1

Type RM Length L Ch R = 1 ,12.032  ,32,32,32
#Sta/Elev= 12
   -11.4   56.09    -1.4   56.09     -.8   56.59       0   56.59     2.2   55.09
     2.2   53.79     5.2   53.79     5.2   55.09     7.4   56.59     8.6   56.59
     9.2   56.09    19.2   56.09
#Mann= 3 , 0 , 0
   -11.4    .035       0       0    .035       0     7.4    .035       0
#XS Ineff= 2 , 0
               0   56.59     7.4           56.59
Permanent Ineff=
       F       F
Bank Sta=0,7.4
XS Rating Curve= 0
Exp/Cntr=.3,.1

Type RM Length L Ch R = 1 ,12      ,26,26,26
#Sta/Elev= 11
   -11.5   55.15    -1.5   55.15     -.8   55.75       0   55.75     1.3   54.35
     3.1   53.65     4.2   53.65     6.9   55.45     8.1   55.45       9   54.45
      19   54.45
#Mann= 3 , 0 , 0
   -11.5    .035       0       0    .035       0     6.9    .035       0
#XS Ineff= 2 , 0
               0   55.75     6.9           55.45
Permanent Ineff=
       F       F
Bank Sta=0,6.9
XS Rating Curve= 0
Exp/Cntr=.3,.1

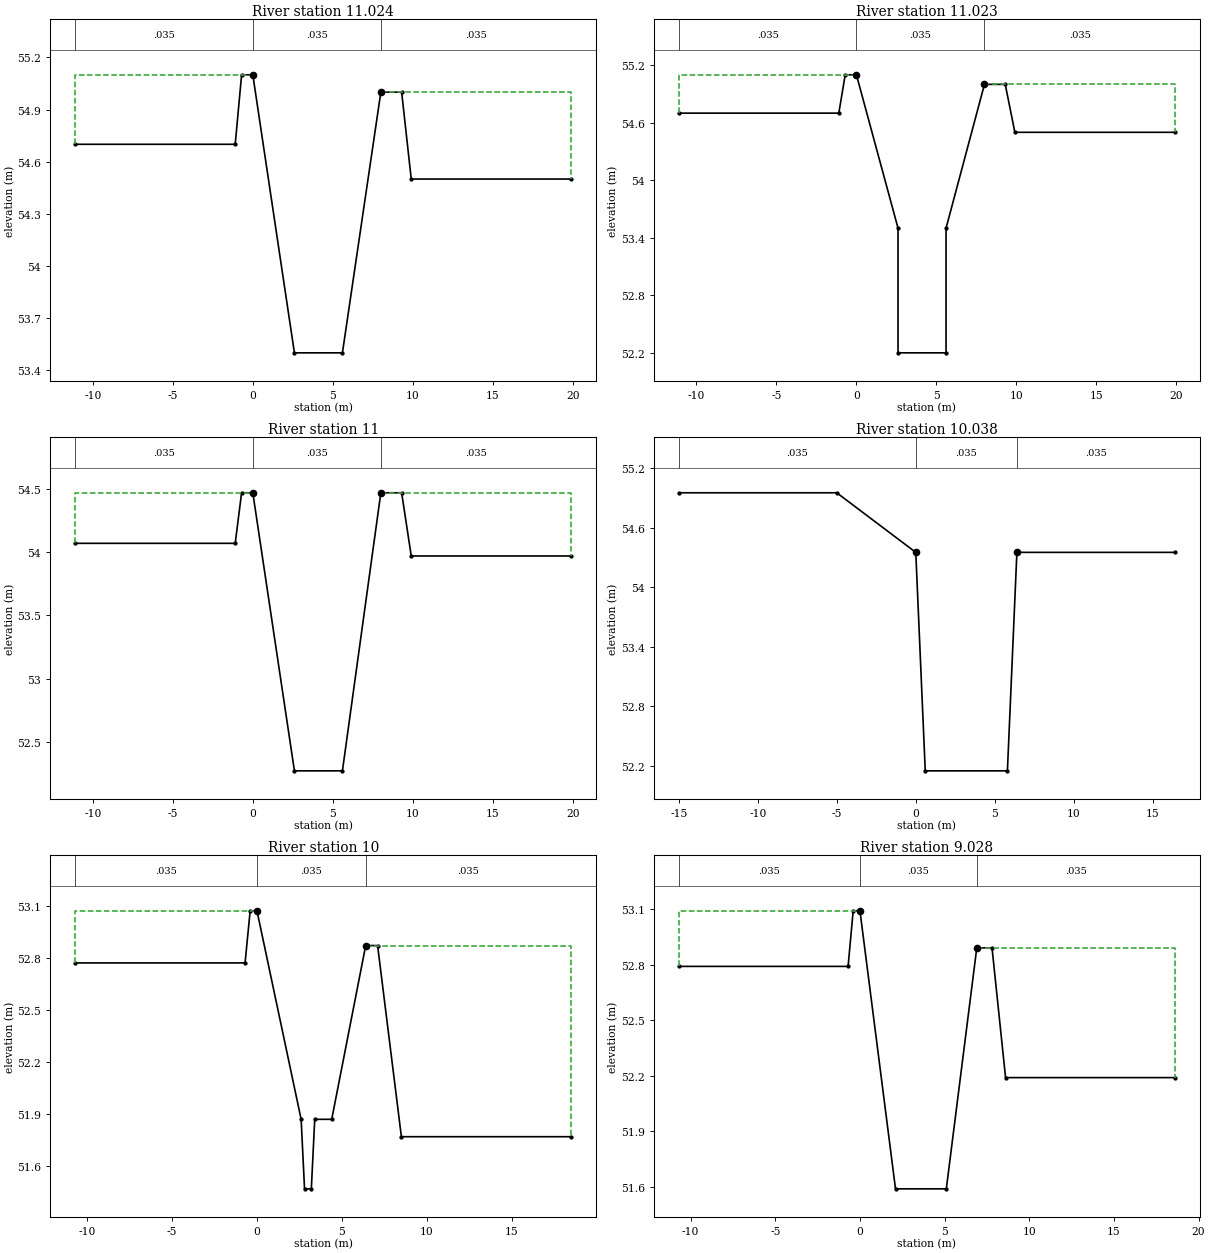
Type RM Length L Ch R = 1 ,11.024  ,1,1,1
#Sta/Elev= 10
   -11.1    54.7    -1.1    54.7     -.7    55.1       0    55.1     2.6    53.5
     5.6    53.5       8      55     9.3      55     9.9    54.5    19.9    54.5
#Mann= 3 , 0 , 0
   -11.1    .035       0       0    .035       0       8    .035       0
#XS Ineff= 2 , 0
               0    55.1       8              55
Permanent Ineff=
       F       F
Bank Sta=0,8
XS Rating Curve= 0
Exp/Cntr=.3,.1

Type RM Length L Ch R = 1 ,11.023  ,23,23,23
#Sta/Elev= 12
   -11.1    54.7    -1.1    54.7     -.7    55.1       0    55.1     2.6    53.5
     2.6    52.2     5.6    52.2     5.6    53.5       8      55     9.3      55
     9.9    54.5    19.9    54.5
#Mann= 3 , 0 , 0
   -11.1    .035       0       0    .035       0       8    .035       0
#XS Ineff= 2 , 0
               0    55.1       8              55
Permanent Ineff=
       F       F
Bank Sta=0,8
XS Rating Curve= 0
Exp/Cntr=.3,.1

Type RM Length L Ch R = 1 ,11      ,12,12,12
#Sta/Elev= 10
   -11.1   54.07    -1.1   54.07     -.7   54.47       0   54.47     2.6   52.27
     5.6   52.27       8   54.47     9.3   54.47     9.9   53.97    19.9   53.97
#Mann= 3 , 0 , 0
   -11.1    .035       0       0    .035       0       8    .035       0
#XS Ineff= 2 , 0
               0   54.47       8           54.47
Permanent Ineff=
       F       F
Bank Sta=0,8
XS Rating Curve= 0
Exp/Cntr=.3,.1

Type RM Length L Ch R = 1 ,10.038  ,38,38,38
#Sta/Elev= 7
     -15   54.95      -5   54.95       0   54.35      .6   52.15     5.8   52.15
     6.4   54.35    16.4   54.35
#Mann= 3 , 0 , 0
     -15    .035       0       0    .035       0     6.4    .035       0
#XS Ineff= 2 , 0
               0   54.35     6.4           54.35
Permanent Ineff=
       F       F
Bank Sta=0,6.4
XS Rating Curve= 0
Exp/Cntr=.3,.1

Type RM Length L Ch R = 1 ,10      ,22,22,22
#Sta/Elev= 13
   -10.7   52.77     -.7   52.77     -.4   53.07       0   53.07     2.6   51.87
     2.8   51.47     3.2   51.47     3.4   51.87     4.4   51.87     6.4   52.87
     7.1   52.87     8.5   51.77    18.5   51.77
#Mann= 3 , 0 , 0
   -10.7    .035       0       0    .035       0     6.4    .035       0
#XS Ineff= 2 , 0
               0   53.07     6.4           52.87
Permanent Ineff=
       F       F
Bank Sta=0,6.4
XS Rating Curve= 0
Exp/Cntr=.3,.1

Type RM Length L Ch R = 1 ,9.028   ,1,1,1
#Sta/Elev= 10
   -10.7   52.79     -.7   52.79     -.4   53.09       0   53.09     2.1   51.59
     5.1   51.59     6.9   52.89     7.8   52.89     8.6   52.19    18.6   52.19
#Mann= 3 , 0 , 0
   -10.7    .035       0       0    .035       0     6.9    .035       0
#XS Ineff= 2 , 0
               0   53.09     6.9           52.89
Permanent Ineff=
       F       F
Bank Sta=0,6.9
XS Rating Curve= 0
Exp/Cntr=.3,.1