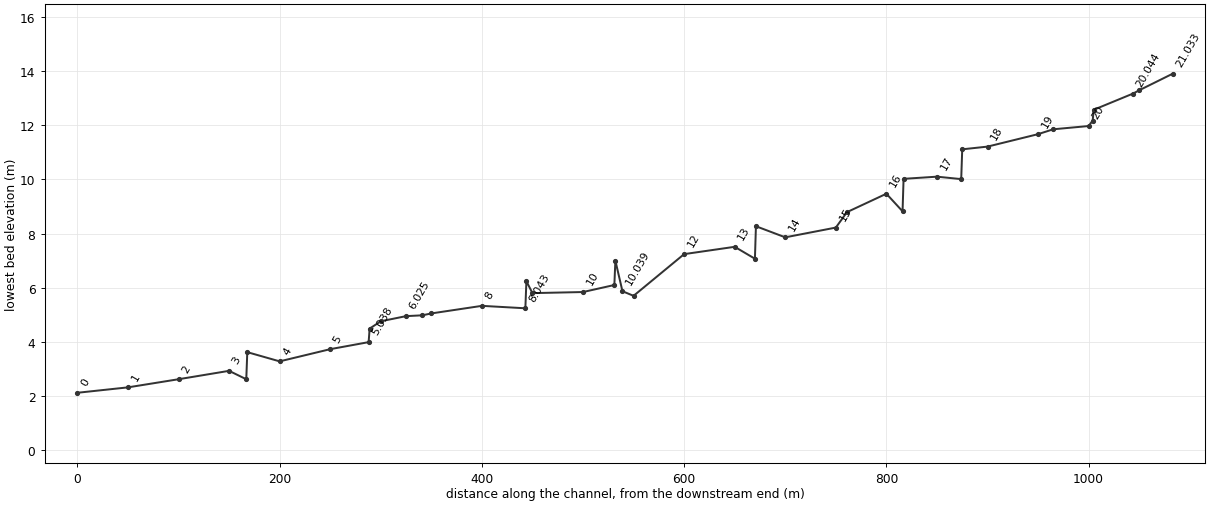
--- BUDEUL.prj (project) ---

Proj Title=BUDEUL
Current Plan=p01
Default Exp/Contr=.3,.1
SI Units
Geom File=g01
Flow File=f01
Plan File=p01
Y Axis Title=Elevation
X Axis Title(PF)=Main Channel Distance
X Axis Title(XS)=Station
BEGIN DESCRIPTION:
           BACK WATER COMPUTATION
      APPLICATION OF HEC-2 BY Samju Construction Engineering
      BURDEUL-STREEM : 30 YR
END DESCRIPTION:
DSS Export Rating Curves= 0
DSS Export Rating Curve Sorted= 0
DSS Export Volume Flow Curves= 0
DXF OffsetX= 0
DXF OffsetY= 0
DXF ScaleX= 1
DXF ScaleY= 10

--- BUDEUL.p01 (plan) ---

Plan Title=Imported Plan 01
Version=Version 3.0.1  Mar 2001
Short Identifier=Imported Pla
Geom File=g01
Flow File=f01
Subcritical Flow
K Sum by GR= 0
Std Step Tol= 0.003
Critical Tol= 0.003
Num of Std Step Trials= 20
Max Error Tol= 0.1
Flow Tol Ratio= 0.001
Split Flow NTrial= 30
Split Flow Tol= 0.02
Split Flow Ratio= 0.02
Log Output Level= 0
Friction Slope Method= 1
Unsteady Friction Slope Method= 2
Parabolic Critical Depth
Global Vel Dist= 0 , 0 , 0
Global Log Level= 0
CheckData=True
Encroach Param=-1 ,0,0, 0
Computation Interval=1HOUR
Output Interval=1HOUR
Run HTab= 0
Run UNet= 0
Run PostProcess= 0
UNET Theta= 1
UNET ZTol= 0.02
UNET ZSATol= 0.1
UNET MxIter= 20
UNET MaxInSteps= 20
UNET DtIC= 0
UNET DtMin= 0
UNET MaxCRTS= 20
UNET WFStab= 2
UNET SFStab= 1
UNET WFX= 1
UNET SFX= 1
UNET Convert EG Bridges=-1
UNET Use Existing IB Tables=-1
Instantaneous Interval=1HOUR
Write IC File= 0
Write Velocity= 0
Write Detailed= 0

--- BUDEUL.f01 (steady flow) ---

Flow Title=Imported Flow 01
Version=Version 3.0.1  Mar 2001
Number of Profiles= 1
Profile Names=PF 1
River Rch & RM=RIVER-1,Reach-1         ,21.033
      75
Boundary for River Rch & Prof#=RIVER-1,Reach-1         , 1
Up Type= 0
Dn Type= 3
Dn Slope=.0109
DSS Import GetInterval= 0
DSS Import GetPeak= 0
DSS Import FillOption= 0

--- BUDEUL.g01 (geometry) ---

Geom Title=Imported Geom 01
Version=Version 3.0.1  Mar 2001

River Reach=RIVER-1         ,Reach-1
Reach XY= 2
              .5             .95              .5             .05

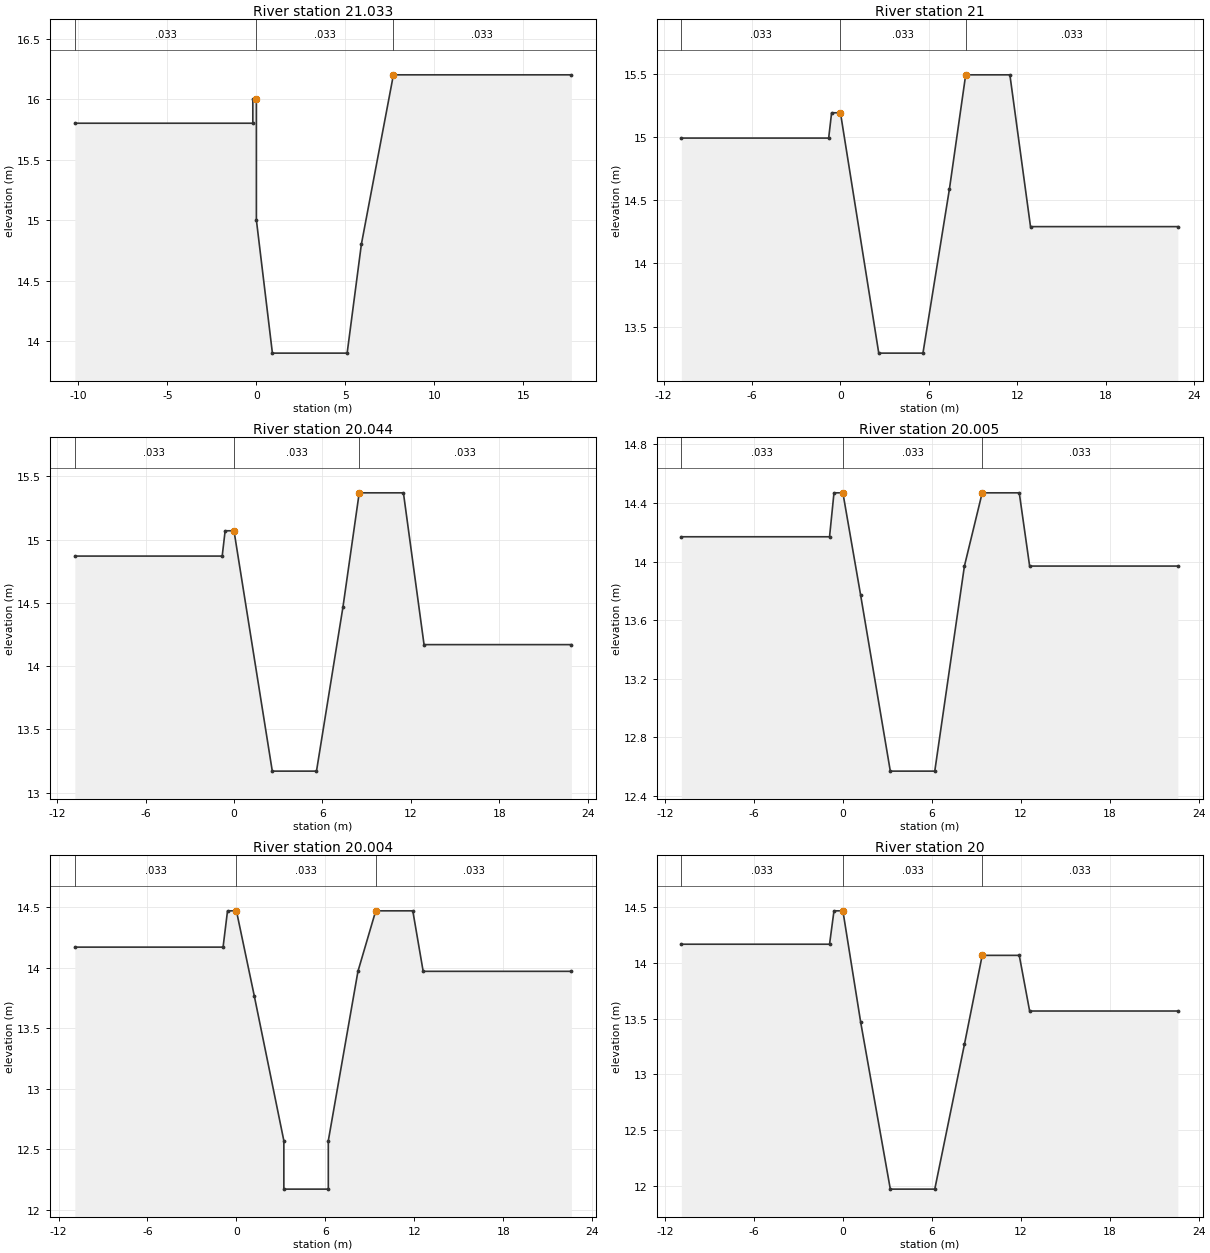
Type RM Length L Ch R = 1 ,21.033  ,33,33,33
#Sta/Elev= 10
   -10.2    15.8     -.2    15.8     -.2      16       0      16       0      15
      .9    13.9     5.1    13.9     5.9    14.8     7.7    16.2    17.7    16.2
#Mann= 3 , 0 , 0
   -10.2    .033       0       0    .033       0     7.7    .033       0
Bank Sta=0,7.7
XS Rating Curve= 0
Exp/Cntr=.3,.1

Type RM Length L Ch R = 1 ,21      ,6,6,6
#Sta/Elev= 11
   -10.8   14.99     -.8   14.99     -.6   15.19       0   15.19     2.6   13.29
     5.6   13.29     7.4   14.59     8.5   15.49    11.5   15.49    12.9   14.29
    22.9   14.29
#Mann= 3 , 0 , 0
   -10.8    .033       0       0    .033       0     8.5    .033       0
Bank Sta=0,8.5
XS Rating Curve= 0
Exp/Cntr=.3,.1

Type RM Length L Ch R = 1 ,20.044  ,39,39,39
#Sta/Elev= 11
   -10.8   14.87     -.8   14.87     -.6   15.07       0   15.07     2.6   13.17
     5.6   13.17     7.4   14.47     8.5   15.37    11.5   15.37    12.9   14.17
    22.9   14.17
#Mann= 3 , 0 , 0
   -10.8    .033       0       0    .033       0     8.5    .033       0
Bank Sta=0,8.5
XS Rating Curve= 0
Exp/Cntr=.3,.1

Type RM Length L Ch R = 1 ,20.005  ,1,1,1
#Sta/Elev= 12
   -10.9   14.17     -.9   14.17     -.6   14.47       0   14.47     1.2   13.77
     3.2   12.57     6.2   12.57     8.2   13.97     9.4   14.47    11.9   14.47
    12.6   13.97    22.6   13.97
#Mann= 3 , 0 , 0
   -10.9    .033       0       0    .033       0     9.4    .033       0
Bank Sta=0,9.4
XS Rating Curve= 0
Exp/Cntr=.3,.1

Type RM Length L Ch R = 1 ,20.004  ,4,4,4
#Sta/Elev= 14
   -10.9   14.17     -.9   14.17     -.6   14.47       0   14.47     1.2   13.77
     3.2   12.57     3.2   12.17     6.2   12.17     6.2   12.57     8.2   13.97
     9.4   14.47    11.9   14.47    12.6   13.97    22.6   13.97
#Mann= 3 , 0 , 0
   -10.9    .033       0       0    .033       0     9.4    .033       0
Bank Sta=0,9.4
XS Rating Curve= 0
Exp/Cntr=.3,.1

Type RM Length L Ch R = 1 ,20      ,35,35,35
#Sta/Elev= 12
   -10.9   14.17     -.9   14.17     -.6   14.47       0   14.47     1.2   13.47
     3.2   11.97     6.2   11.97     8.2   13.27     9.4   14.07    11.9   14.07
    12.6   13.57    22.6   13.57
#Mann= 3 , 0 , 0
   -10.9    .033       0       0    .033       0     9.4    .033       0
Bank Sta=0,9.4
XS Rating Curve= 0
Exp/Cntr=.3,.1

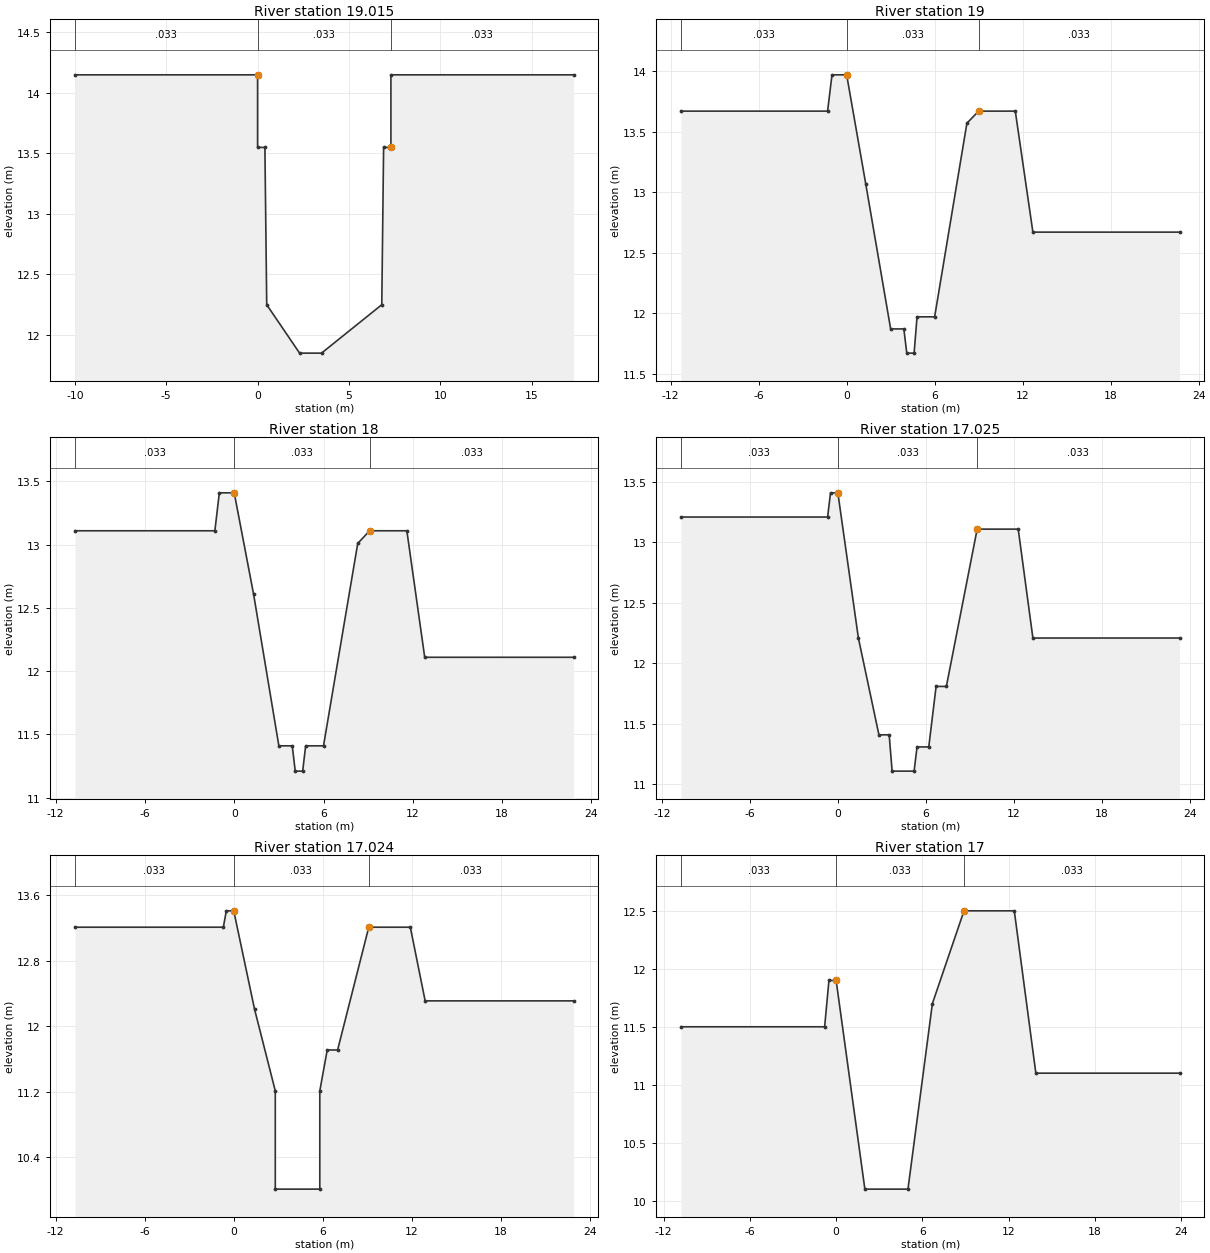
Type RM Length L Ch R = 1 ,19.015  ,15,15,15
#Sta/Elev= 12
     -10   14.15       0   14.15       0   13.55      .4   13.55      .5   12.25
     2.3   11.85     3.5   11.85     6.8   12.25     6.9   13.55     7.3   13.55
     7.3   14.15    17.3   14.15
#Mann= 3 , 0 , 0
     -10    .033       0       0    .033       0     7.3    .033       0
Bank Sta=0,7.3
XS Rating Curve= 0
Exp/Cntr=.3,.1

Type RM Length L Ch R = 1 ,19      ,50,50,50
#Sta/Elev= 16
   -11.3   13.67    -1.3   13.67      -1   13.97       0   13.97     1.3   13.07
       3   11.87     3.9   11.87     4.1   11.67     4.6   11.67     4.8   11.97
       6   11.97     8.2   13.57       9   13.67    11.5   13.67    12.7   12.67
    22.7   12.67
#Mann= 3 , 0 , 0
   -11.3    .033       0       0    .033       0       9    .033       0
Bank Sta=0,9
XS Rating Curve= 0
Exp/Cntr=.3,.1

Type RM Length L Ch R = 1 ,18      ,25,25,25
#Sta/Elev= 16
   -10.7   13.11    -1.3   13.11      -1   13.41       0   13.41     1.3   12.61
       3   11.41     3.9   11.41     4.1   11.21     4.6   11.21     4.8   11.41
       6   11.41     8.3   13.01     9.1   13.11    11.6   13.11    12.8   12.11
    22.8   12.11
#Mann= 3 , 0 , 0
   -10.7    .033       0       0    .033       0     9.1    .033       0
Bank Sta=0,9.1
XS Rating Curve= 0
Exp/Cntr=.3,.1

Type RM Length L Ch R = 1 ,17.025  ,1,1,1
#Sta/Elev= 17
   -10.7   13.21     -.7   13.21     -.5   13.41       0   13.41     1.4   12.21
     2.8   11.41     3.5   11.41     3.7   11.11     5.2   11.11     5.4   11.31
     6.2   11.31     6.7   11.81     7.4   11.81     9.5   13.11    12.3   13.11
    13.3   12.21    23.3   12.21
#Mann= 3 , 0 , 0
   -10.7    .033       0       0    .033       0     9.5    .033       0
Bank Sta=0,9.5
XS Rating Curve= 0
Exp/Cntr=.3,.1

Type RM Length L Ch R = 1 ,17.024  ,24,24,24
#Sta/Elev= 15
   -10.7   13.21     -.7   13.21     -.5   13.41       0   13.41     1.4   12.21
     2.8   11.21     2.8   10.01     5.8   10.01     5.8   11.21     6.3   11.71
       7   11.71     9.1   13.21    11.9   13.21    12.9   12.31    22.9   12.31
#Mann= 3 , 0 , 0
   -10.7    .033       0       0    .033       0     9.1    .033       0
Bank Sta=0,9.1
XS Rating Curve= 0
Exp/Cntr=.3,.1

Type RM Length L Ch R = 1 ,17      ,33,33,33
#Sta/Elev= 11
   -10.8    11.5     -.8    11.5     -.5    11.9       0    11.9       2    10.1
       5    10.1     6.7    11.7     8.9    12.5    12.4    12.5    13.9    11.1
    23.9    11.1
#Mann= 3 , 0 , 0
   -10.8    .033       0       0    .033       0     8.9    .033       0
Bank Sta=0,8.9
XS Rating Curve= 0
Exp/Cntr=.3,.1

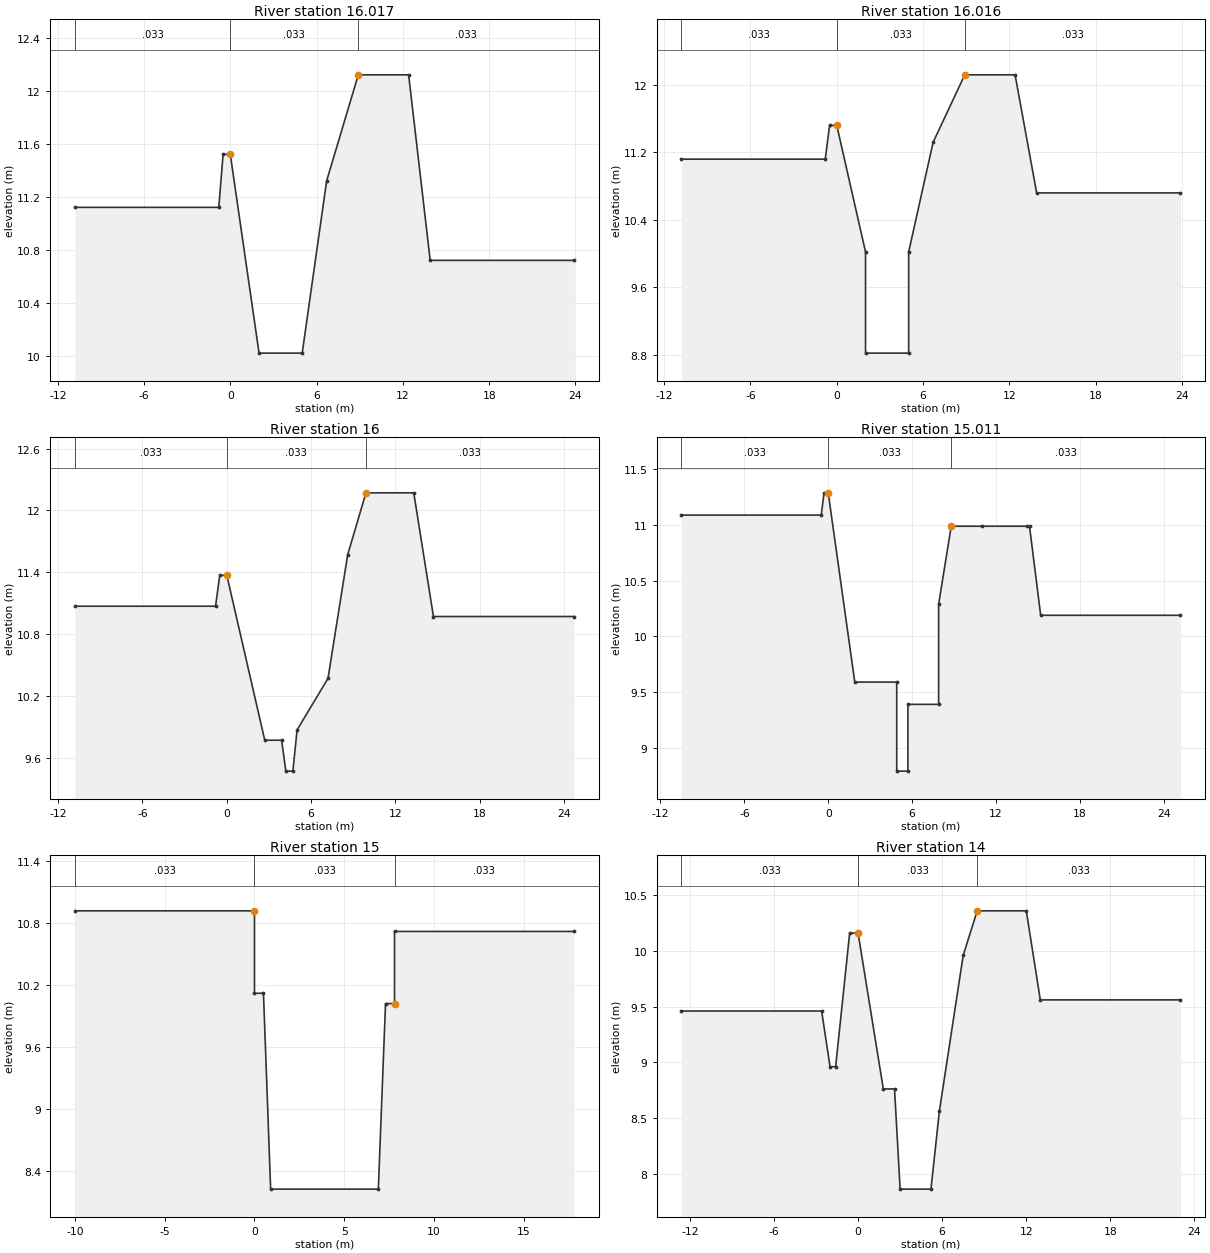
Type RM Length L Ch R = 1 ,16.017  ,1,1,1
#Sta/Elev= 11
   -10.8   11.12     -.8   11.12     -.5   11.52       0   11.52       2   10.02
       5   10.02     6.7   11.32     8.9   12.12    12.4   12.12    13.9   10.72
    23.9   10.72
#Mann= 3 , 0 , 0
   -10.8    .033       0       0    .033       0     8.9    .033       0
Bank Sta=0,8.9
XS Rating Curve= 0
Exp/Cntr=.3,.1

Type RM Length L Ch R = 1 ,16.016  ,16,16,16
#Sta/Elev= 13
   -10.8   11.12     -.8   11.12     -.5   11.52       0   11.52       2   10.02
       2    8.82       5    8.82       5   10.02     6.7   11.32     8.9   12.12
    12.4   12.12    13.9   10.72    23.9   10.72
#Mann= 3 , 0 , 0
   -10.8    .033       0       0    .033       0     8.9    .033       0
Bank Sta=0,8.9
XS Rating Curve= 0
Exp/Cntr=.3,.1

Type RM Length L Ch R = 1 ,16      ,39,39,39
#Sta/Elev= 15
   -10.8   11.07     -.8   11.07     -.5   11.37       0   11.37     2.7    9.77
     3.9    9.77     4.2    9.47     4.7    9.47       5    9.87     7.2   10.37
     8.6   11.57     9.9   12.17    13.3   12.17    14.7   10.97    24.7   10.97
#Mann= 3 , 0 , 0
   -10.8    .033       0       0    .033       0     9.9    .033       0
Bank Sta=0,9.9
XS Rating Curve= 0
Exp/Cntr=.3,.1

Type RM Length L Ch R = 1 ,15.011  ,11,11,11
#Sta/Elev= 17
   -10.5   11.09     -.5   11.09     -.3   11.29       0   11.29     1.9    9.59
     4.9    9.59     4.9    8.79     5.7    8.79     5.7    9.39     7.9    9.39
     7.9   10.29     8.8   10.99      11   10.99    14.2   10.99    14.4   10.99
    15.2   10.19    25.2   10.19
#Mann= 3 , 0 , 0
   -10.5    .033       0       0    .033       0     8.8    .033       0
Bank Sta=0,8.8
XS Rating Curve= 0
Exp/Cntr=.3,.1

Type RM Length L Ch R = 1 ,15      ,50,50,50
#Sta/Elev= 10
     -10   10.92       0   10.92       0   10.12      .5   10.12      .9    8.22
     6.9    8.22     7.3   10.02     7.8   10.02     7.8   10.72    17.8   10.72
#Mann= 3 , 0 , 0
     -10    .033       0       0    .033       0     7.8    .033       0
Bank Sta=0,7.8
XS Rating Curve= 0
Exp/Cntr=.3,.1

Type RM Length L Ch R = 1 ,14      ,29,29,29
#Sta/Elev= 16
   -12.6    9.46    -2.6    9.46      -2    8.96    -1.6    8.96     -.6   10.16
       0   10.16     1.8    8.76     2.6    8.76       3    7.86     5.2    7.86
     5.8    8.56     7.5    9.96     8.5   10.36      12   10.36      13    9.56
      23    9.56
#Mann= 3 , 0 , 0
   -12.6    .033       0       0    .033       0     8.5    .033       0
Bank Sta=0,8.5
XS Rating Curve= 0
Exp/Cntr=.3,.1

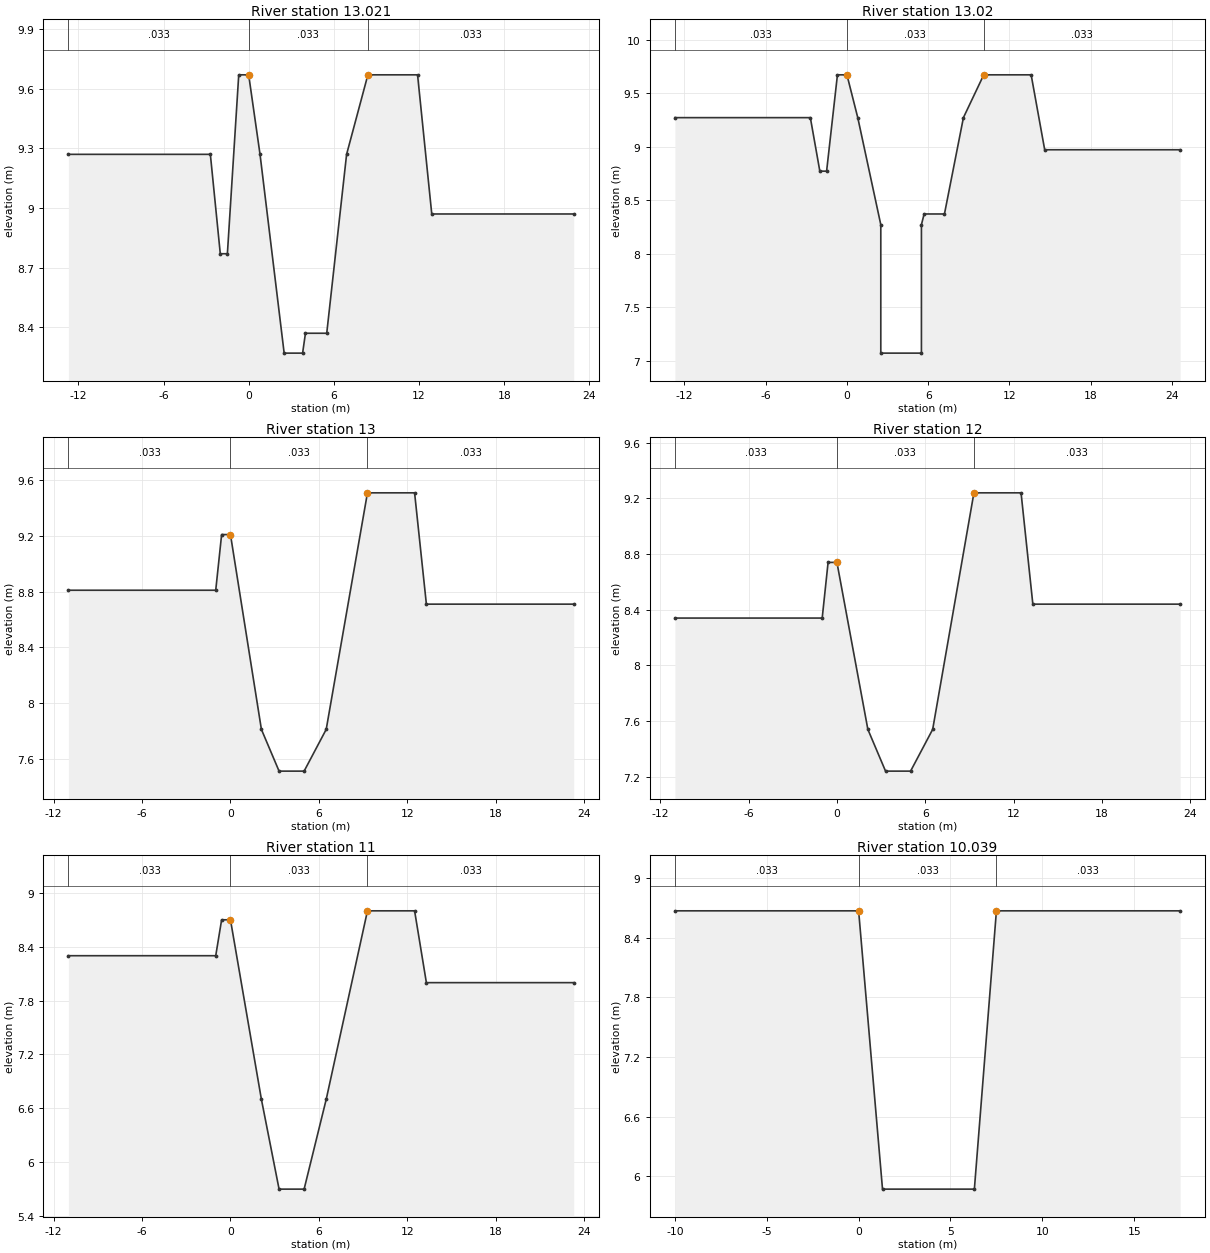
Type RM Length L Ch R = 1 ,13.021  ,1,1,1
#Sta/Elev= 16
   -12.7    9.27    -2.7    9.27      -2    8.77    -1.5    8.77     -.7    9.67
       0    9.67      .8    9.27     2.5    8.27     3.8    8.27       4    8.37
     5.5    8.37     6.9    9.27     8.4    9.67    11.9    9.67    12.9    8.97
    22.9    8.97
#Mann= 3 , 0 , 0
   -12.7    .033       0       0    .033       0     8.4    .033       0
Bank Sta=0,8.4
XS Rating Curve= 0
Exp/Cntr=.3,.1

Type RM Length L Ch R = 1 ,13.02   ,20,20,20
#Sta/Elev= 18
   -12.7    9.27    -2.7    9.27      -2    8.77    -1.5    8.77     -.7    9.67
       0    9.67      .8    9.27     2.5    8.27     2.5    7.07     5.5    7.07
     5.5    8.27     5.7    8.37     7.2    8.37     8.6    9.27    10.1    9.67
    13.6    9.67    14.6    8.97    24.6    8.97
#Mann= 3 , 0 , 0
   -12.7    .033       0       0    .033       0    10.1    .033       0
Bank Sta=0,10.1
XS Rating Curve= 0
Exp/Cntr=.3,.1

Type RM Length L Ch R = 1 ,13      ,50,50,50
#Sta/Elev= 12
     -11    8.81      -1    8.81     -.6    9.21       0    9.21     2.1    7.81
     3.3    7.51       5    7.51     6.5    7.81     9.3    9.51    12.5    9.51
    13.3    8.71    23.3    8.71
#Mann= 3 , 0 , 0
     -11    .033       0       0    .033       0     9.3    .033       0
Bank Sta=0,9.3
XS Rating Curve= 0
Exp/Cntr=.3,.1

Type RM Length L Ch R = 1 ,12      ,50,50,50
#Sta/Elev= 12
     -11    8.34      -1    8.34     -.6    8.74       0    8.74     2.1    7.54
     3.3    7.24       5    7.24     6.5    7.54     9.3    9.24    12.5    9.24
    13.3    8.44    23.3    8.44
#Mann= 3 , 0 , 0
     -11    .033       0       0    .033       0     9.3    .033       0
Bank Sta=0,9.3
XS Rating Curve= 0
Exp/Cntr=.3,.1

Type RM Length L Ch R = 1 ,11      ,11,11,11
#Sta/Elev= 12
     -11     8.3      -1     8.3     -.6     8.7       0     8.7     2.1     6.7
     3.3     5.7       5     5.7     6.5     6.7     9.3     8.8    12.5     8.8
    13.3       8    23.3       8
#Mann= 3 , 0 , 0
     -11    .033       0       0    .033       0     9.3    .033       0
Bank Sta=0,9.3
XS Rating Curve= 0
Exp/Cntr=.3,.1

Type RM Length L Ch R = 1 ,10.039  ,7,7,7
#Sta/Elev= 6
     -10    8.67       0    8.67     1.3    5.87     6.3    5.87     7.5    8.67
    17.5    8.67
#Mann= 3 , 0 , 0
     -10    .033       0       0    .033       0     7.5    .033       0
Bank Sta=0,7.5
XS Rating Curve= 0
Exp/Cntr=.3,.1

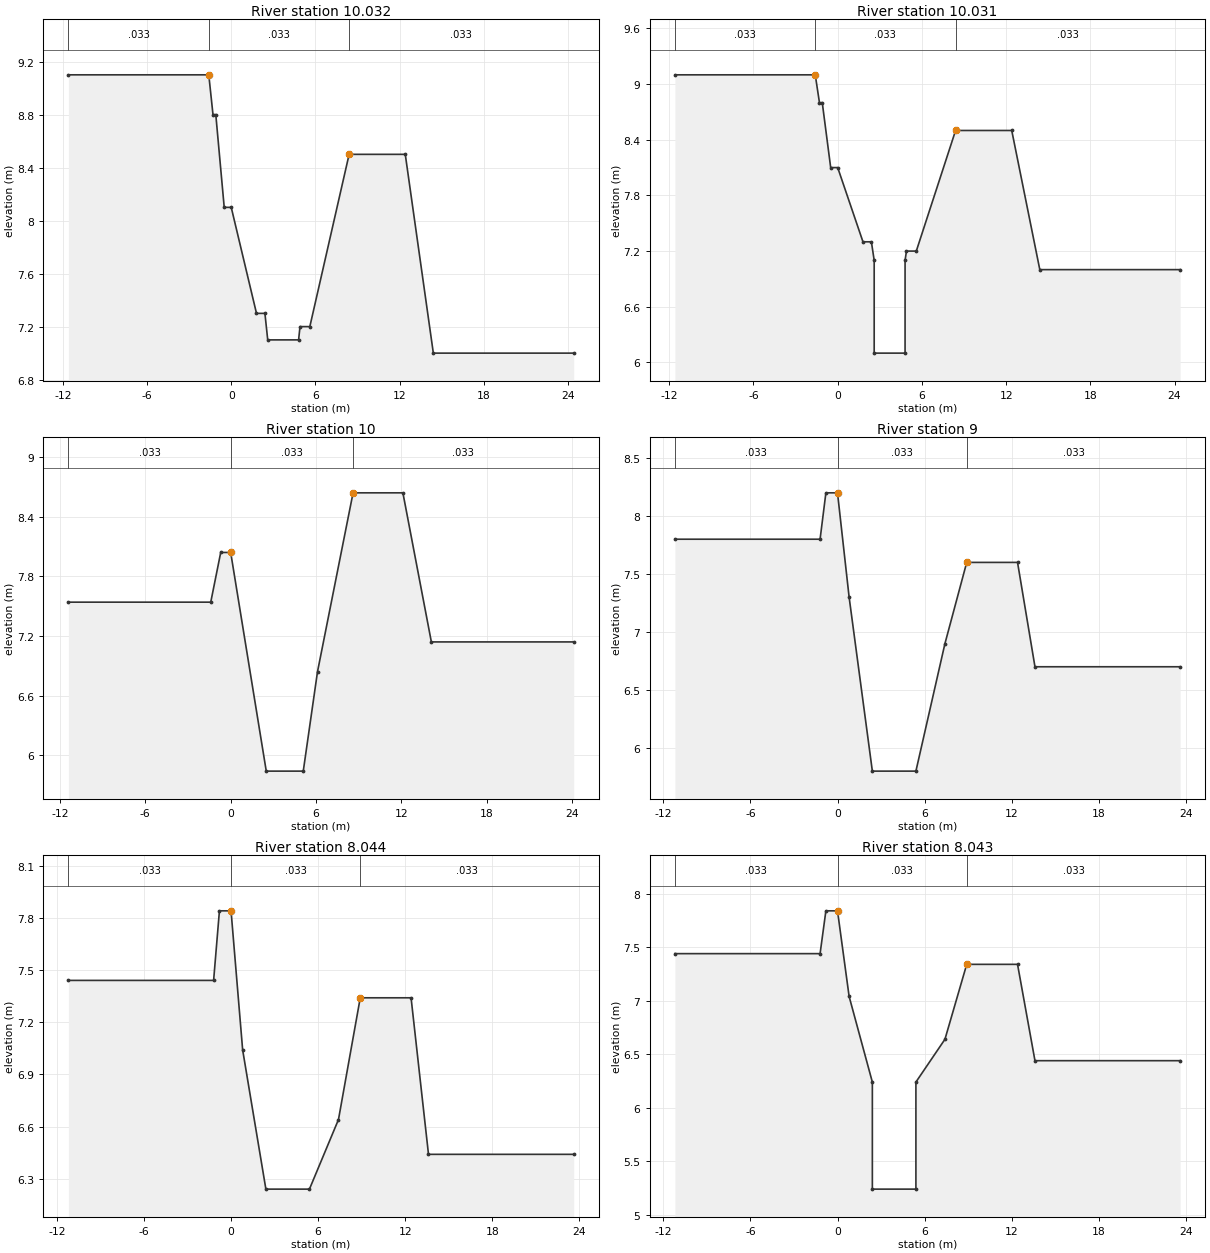
Type RM Length L Ch R = 1 ,10.032  ,1,1,1
#Sta/Elev= 16
   -11.6     9.1    -1.6     9.1    -1.3     8.8    -1.1     8.8     -.5     8.1
       0     8.1     1.8     7.3     2.4     7.3     2.6     7.1     4.8     7.1
     4.9     7.2     5.6     7.2     8.4     8.5    12.4     8.5    14.4       7
    24.4       7
#Mann= 3 , 0 , 0
   -11.6    .033       0    -1.6    .033       0     8.4    .033       0
Bank Sta=-1.6,8.4
XS Rating Curve= 0
Exp/Cntr=.3,.1

Type RM Length L Ch R = 1 ,10.031  ,31,31,31
#Sta/Elev= 18
   -11.6     9.1    -1.6     9.1    -1.3     8.8    -1.1     8.8     -.5     8.1
       0     8.1     1.8     7.3     2.4     7.3     2.6     7.1     2.6     6.1
     4.8     6.1     4.8     7.1     4.9     7.2     5.6     7.2     8.4     8.5
    12.4     8.5    14.4       7    24.4       7
#Mann= 3 , 0 , 0
   -11.6    .033       0    -1.6    .033       0     8.4    .033       0
Bank Sta=-1.6,8.4
XS Rating Curve= 0
Exp/Cntr=.3,.1

Type RM Length L Ch R = 1 ,10      ,50,50,50
#Sta/Elev= 11
   -11.4    7.54    -1.4    7.54     -.7    8.04       0    8.04     2.5    5.84
     5.1    5.84     6.1    6.84     8.6    8.64    12.1    8.64    14.1    7.14
    24.1    7.14
#Mann= 3 , 0 , 0
   -11.4    .033       0       0    .033       0     8.6    .033       0
Bank Sta=0,8.6
XS Rating Curve= 0
Exp/Cntr=.3,.1

Type RM Length L Ch R = 1 ,9       ,6,6,6
#Sta/Elev= 12
   -11.2     7.8    -1.2     7.8     -.8     8.2       0     8.2      .8     7.3
     2.4     5.8     5.4     5.8     7.4     6.9     8.9     7.6    12.4     7.6
    13.6     6.7    23.6     6.7
#Mann= 3 , 0 , 0
   -11.2    .033       0       0    .033       0     8.9    .033       0
Bank Sta=0,8.9
XS Rating Curve= 0
Exp/Cntr=.3,.1

Type RM Length L Ch R = 1 ,8.044   ,1,1,1
#Sta/Elev= 12
   -11.2    7.44    -1.2    7.44     -.8    7.84       0    7.84      .8    7.04
     2.4    6.24     5.4    6.24     7.4    6.64     8.9    7.34    12.4    7.34
    13.6    6.44    23.6    6.44
#Mann= 3 , 0 , 0
   -11.2    .033       0       0    .033       0     8.9    .033       0
Bank Sta=0,8.9
XS Rating Curve= 0
Exp/Cntr=.3,.1

Type RM Length L Ch R = 1 ,8.043   ,43,43,43
#Sta/Elev= 14
   -11.2    7.44    -1.2    7.44     -.8    7.84       0    7.84      .8    7.04
     2.4    6.24     2.4    5.24     5.4    5.24     5.4    6.24     7.4    6.64
     8.9    7.34    12.4    7.34    13.6    6.44    23.6    6.44
#Mann= 3 , 0 , 0
   -11.2    .033       0       0    .033       0     8.9    .033       0
Bank Sta=0,8.9
XS Rating Curve= 0
Exp/Cntr=.3,.1

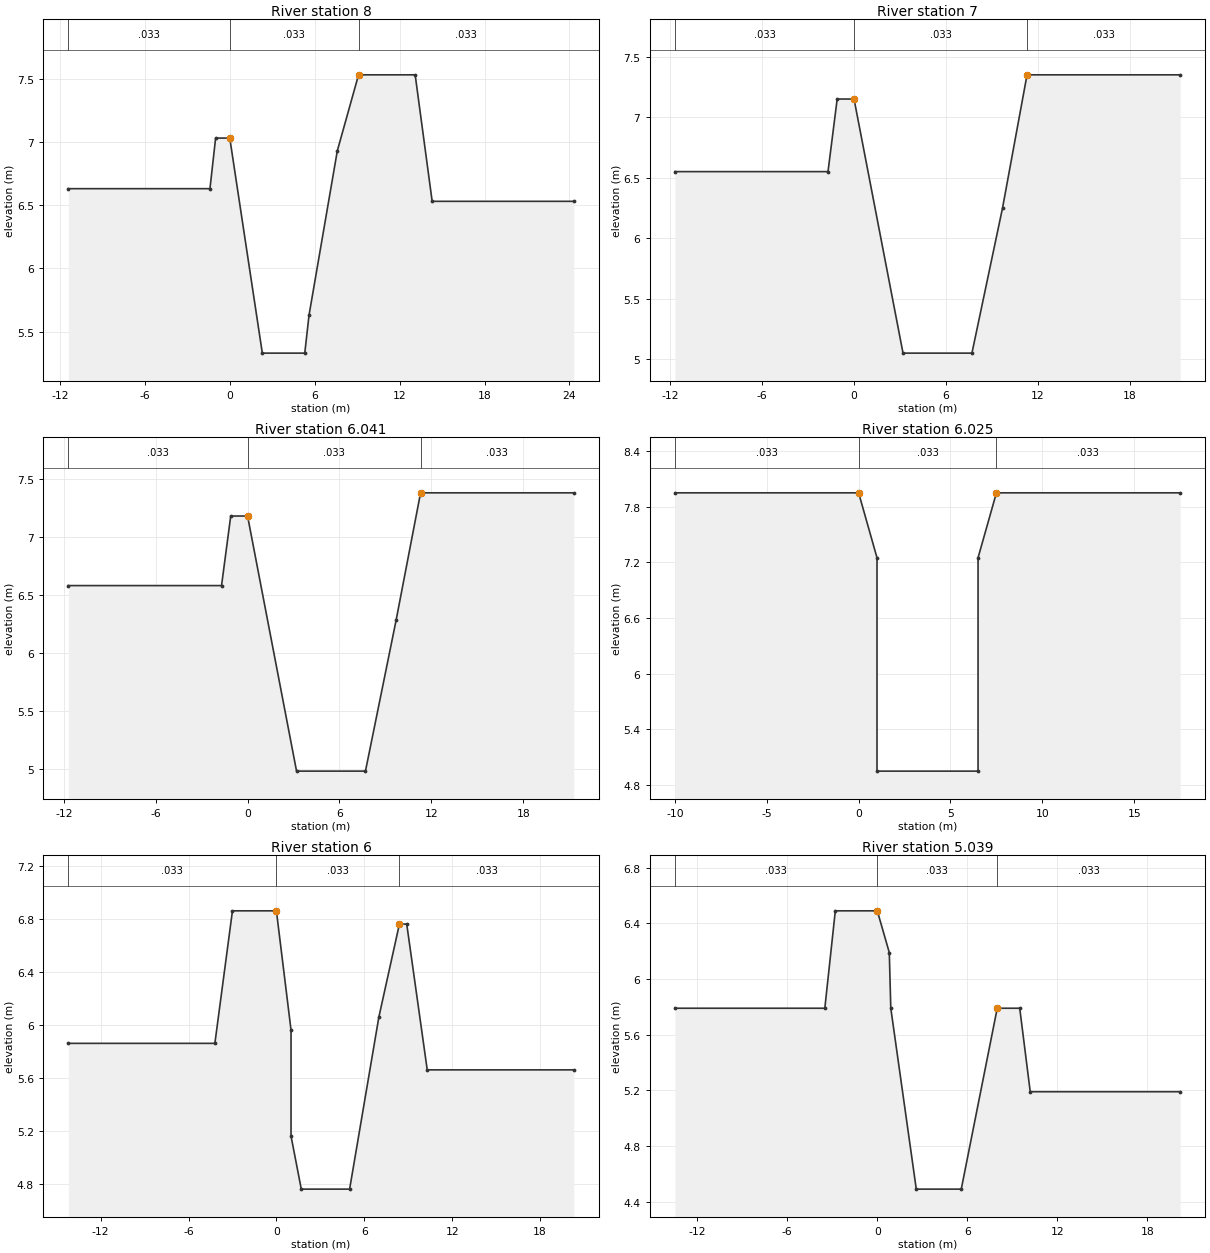
Type RM Length L Ch R = 1 ,8       ,50,50,50
#Sta/Elev= 12
   -11.4    6.63    -1.4    6.63      -1    7.03       0    7.03     2.3    5.33
     5.3    5.33     5.6    5.63     7.6    6.93     9.1    7.53    13.1    7.53
    14.3    6.53    24.3    6.53
#Mann= 3 , 0 , 0
   -11.4    .033       0       0    .033       0     9.1    .033       0
Bank Sta=0,9.1
XS Rating Curve= 0
Exp/Cntr=.3,.1

Type RM Length L Ch R = 1 ,7       ,9,9,9
#Sta/Elev= 9
   -11.7    6.55    -1.7    6.55    -1.1    7.15       0    7.15     3.2    5.05
     7.7    5.05     9.7    6.25    11.3    7.35    21.3    7.35
#Mann= 3 , 0 , 0
   -11.7    .033       0       0    .033       0    11.3    .033       0
Bank Sta=0,11.3
XS Rating Curve= 0
Exp/Cntr=.3,.1

Type RM Length L Ch R = 1 ,6.041   ,16,16,16
#Sta/Elev= 9
   -11.7    6.58    -1.7    6.58    -1.1    7.18       0    7.18     3.2    4.98
     7.7    4.98     9.7    6.28    11.3    7.38    21.3    7.38
#Mann= 3 , 0 , 0
   -11.7    .033       0       0    .033       0    11.3    .033       0
Bank Sta=0,11.3
XS Rating Curve= 0
Exp/Cntr=.3,.1

Type RM Length L Ch R = 1 ,6.025   ,25,25,25
#Sta/Elev= 8
     -10    7.95       0    7.95       1    7.25       1    4.95     6.5    4.95
     6.5    7.25     7.5    7.95    17.5    7.95
#Mann= 3 , 0 , 0
     -10    .033       0       0    .033       0     7.5    .033       0
Bank Sta=0,7.5
XS Rating Curve= 0
Exp/Cntr=.3,.1

Type RM Length L Ch R = 1 ,6       ,11,11,11
#Sta/Elev= 13
   -14.2    5.86    -4.2    5.86      -3    6.86       0    6.86       1    5.96
       1    5.16     1.7    4.76       5    4.76       7    6.06     8.4    6.76
     8.9    6.76    10.3    5.66    20.3    5.66
#Mann= 3 , 0 , 0
   -14.2    .033       0       0    .033       0     8.4    .033       0
Bank Sta=0,8.4
XS Rating Curve= 0
Exp/Cntr=.3,.1

Type RM Length L Ch R = 1 ,5.039   ,1,1,1
#Sta/Elev= 12
   -13.5    5.79    -3.5    5.79    -2.8    6.49       0    6.49      .8    6.19
      .9    5.79     2.6    4.49     5.6    4.49       8    5.79     9.5    5.79
    10.2    5.19    20.2    5.19
#Mann= 3 , 0 , 0
   -13.5    .033       0       0    .033       0       8    .033       0
Bank Sta=0,8
XS Rating Curve= 0
Exp/Cntr=.3,.1

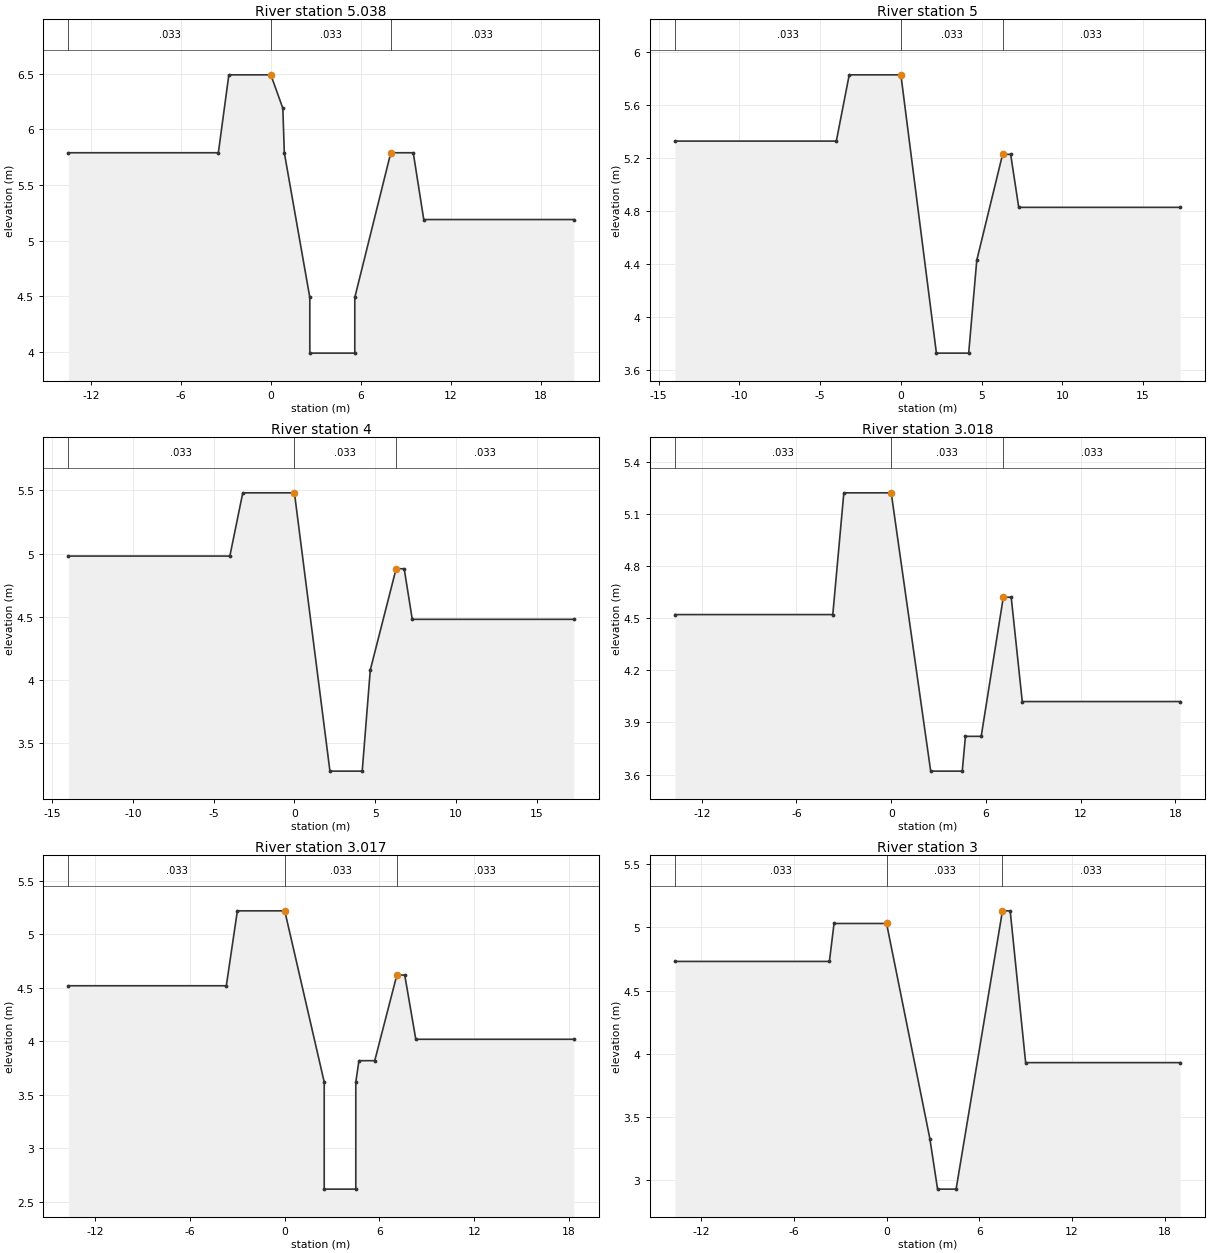
Type RM Length L Ch R = 1 ,5.038   ,38,38,38
#Sta/Elev= 14
   -13.5    5.79    -3.5    5.79    -2.8    6.49       0    6.49      .8    6.19
      .9    5.79     2.6    4.49     2.6    3.99     5.6    3.99     5.6    4.49
       8    5.79     9.5    5.79    10.2    5.19    20.2    5.19
#Mann= 3 , 0 , 0
   -13.5    .033       0       0    .033       0       8    .033       0
Bank Sta=0,8
XS Rating Curve= 0
Exp/Cntr=.3,.1

Type RM Length L Ch R = 1 ,5       ,50,50,50
#Sta/Elev= 11
     -14    5.33      -4    5.33    -3.2    5.83       0    5.83     2.2    3.73
     4.2    3.73     4.7    4.43     6.3    5.23     6.8    5.23     7.3    4.83
    17.3    4.83
#Mann= 3 , 0 , 0
     -14    .033       0       0    .033       0     6.3    .033       0
Bank Sta=0,6.3
XS Rating Curve= 0
Exp/Cntr=.3,.1

Type RM Length L Ch R = 1 ,4       ,32,32,32
#Sta/Elev= 11
     -14    4.98      -4    4.98    -3.2    5.48       0    5.48     2.2    3.28
     4.2    3.28     4.7    4.08     6.3    4.88     6.8    4.88     7.3    4.48
    17.3    4.48
#Mann= 3 , 0 , 0
     -14    .033       0       0    .033       0     6.3    .033       0
Bank Sta=0,6.3
XS Rating Curve= 0
Exp/Cntr=.3,.1

Type RM Length L Ch R = 1 ,3.018   ,1,1,1
#Sta/Elev= 12
   -13.7    4.52    -3.7    4.52      -3    5.22       0    5.22     2.5    3.62
     4.5    3.62     4.7    3.82     5.7    3.82     7.1    4.62     7.6    4.62
     8.3    4.02    18.3    4.02
#Mann= 3 , 0 , 0
   -13.7    .033       0       0    .033       0     7.1    .033       0
Bank Sta=0,7.1
XS Rating Curve= 0
Exp/Cntr=.3,.1

Type RM Length L Ch R = 1 ,3.017   ,17,17,17
#Sta/Elev= 14
   -13.7    4.52    -3.7    4.52      -3    5.22       0    5.22     2.5    3.62
     2.5    2.62     4.5    2.62     4.5    3.62     4.7    3.82     5.7    3.82
     7.1    4.62     7.6    4.62     8.3    4.02    18.3    4.02
#Mann= 3 , 0 , 0
   -13.7    .033       0       0    .033       0     7.1    .033       0
Bank Sta=0,7.1
XS Rating Curve= 0
Exp/Cntr=.3,.1

Type RM Length L Ch R = 1 ,3       ,50,50,50
#Sta/Elev= 11
   -13.7    4.73    -3.7    4.73    -3.4    5.03       0    5.03     2.8    3.33
     3.3    2.93     4.5    2.93     7.5    5.13       8    5.13       9    3.93
      19    3.93
#Mann= 3 , 0 , 0
   -13.7    .033       0       0    .033       0     7.5    .033       0
Bank Sta=0,7.5
XS Rating Curve= 0
Exp/Cntr=.3,.1

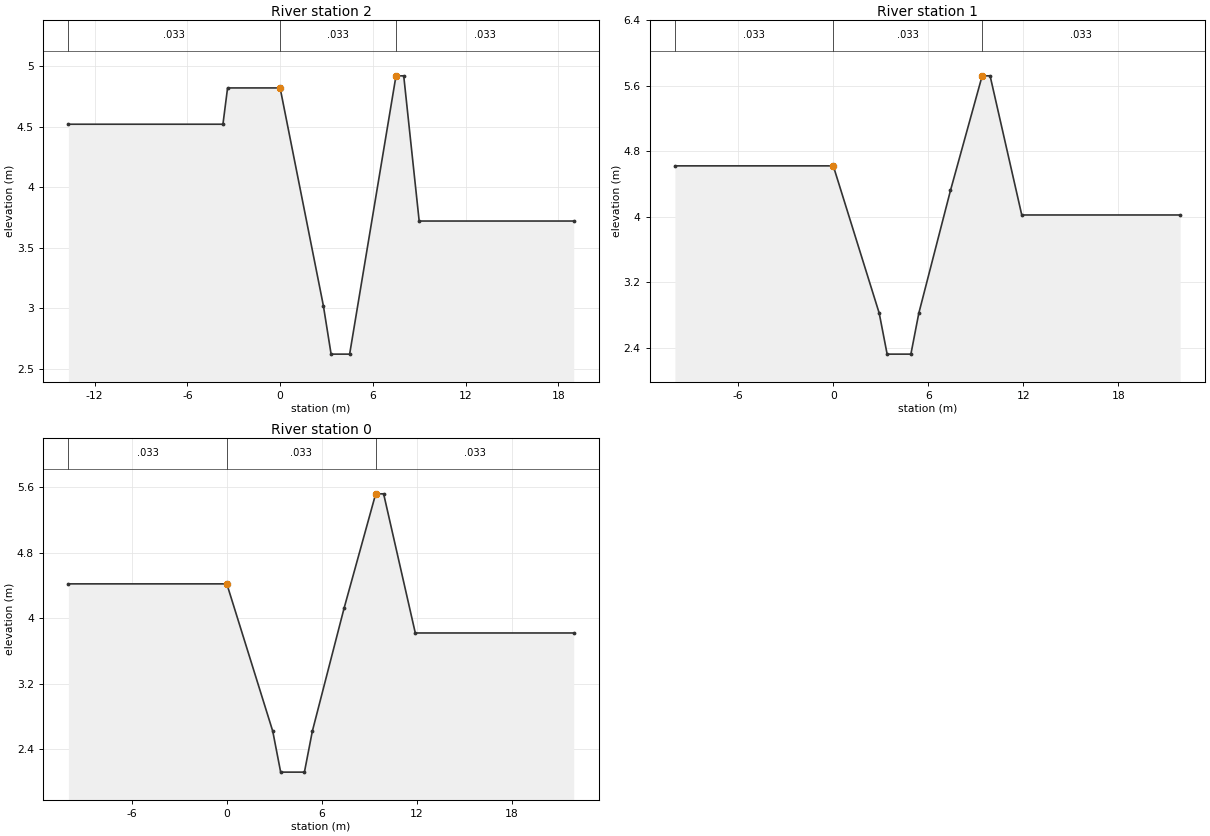
Type RM Length L Ch R = 1 ,2       ,50,50,50
#Sta/Elev= 11
   -13.7    4.52    -3.7    4.52    -3.4    4.82       0    4.82     2.8    3.02
     3.3    2.62     4.5    2.62     7.5    4.92       8    4.92       9    3.72
      19    3.72
#Mann= 3 , 0 , 0
   -13.7    .033       0       0    .033       0     7.5    .033       0
Bank Sta=0,7.5
XS Rating Curve= 0
Exp/Cntr=.3,.1

Type RM Length L Ch R = 1 ,1       ,50,50,50
#Sta/Elev= 11
     -10    4.62       0    4.62     2.9    2.82     3.4    2.32     4.9    2.32
     5.4    2.82     7.4    4.32     9.4    5.72     9.9    5.72    11.9    4.02
    21.9    4.02
#Mann= 3 , 0 , 0
     -10    .033       0       0    .033       0     9.4    .033       0
Bank Sta=0,9.4
XS Rating Curve= 0
Exp/Cntr=.3,.1

Type RM Length L Ch R = 1 ,0       ,0,0,0
#Sta/Elev= 11
     -10    4.42       0    4.42     2.9    2.62     3.4    2.12     4.9    2.12
     5.4    2.62     7.4    4.12     9.4    5.52     9.9    5.52    11.9    3.82
    21.9    3.82
#Mann= 3 , 0 , 0
     -10    .033       0       0    .033       0     9.4    .033       0
Bank Sta=0,9.4
XS Rating Curve= 0
Exp/Cntr=.3,.1

Chan Stop Cuts=-1