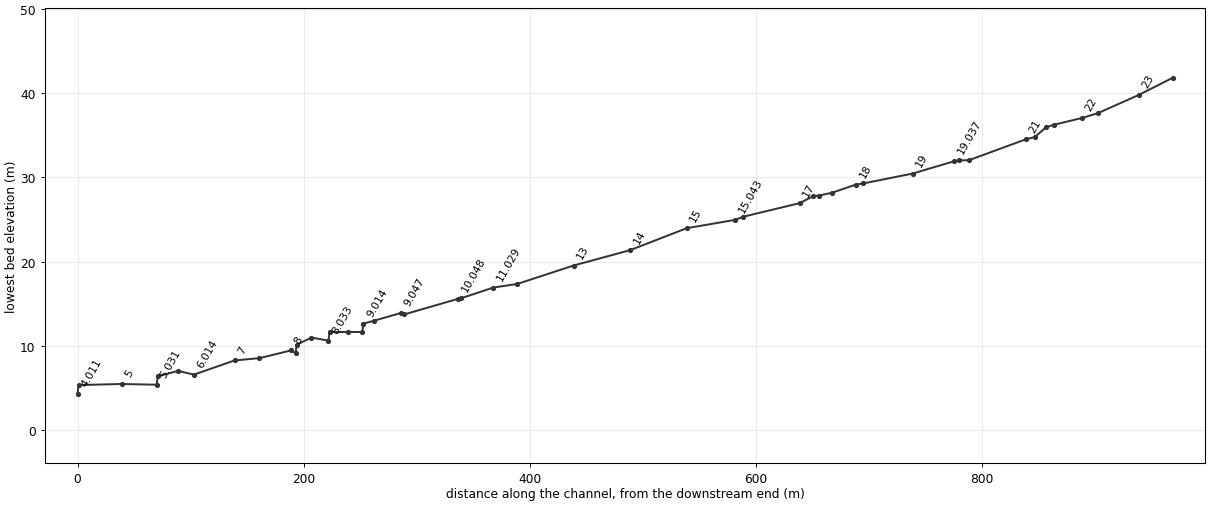
--- SIRUMHOI.prj (project) ---

Proj Title=SIRUMHOI
Current Plan=p01
Default Exp/Contr=.3,.1
SI Units
Geom File=g01
Flow File=f01
Plan File=p01
Y Axis Title=Elevation
X Axis Title(PF)=Main Channel Distance
X Axis Title(XS)=Station
BEGIN DESCRIPTION:
           BACK WATER COMPUTATION
      APPLICATION OF HEC-2 BY Samju Construction Engineering
      SIRUME-STREEM : 30 YR
END DESCRIPTION:
DSS Export Rating Curves= 0
DSS Export Rating Curve Sorted= 0
DSS Export Volume Flow Curves= 0
DXF OffsetX= 0
DXF OffsetY= 0
DXF ScaleX= 1
DXF ScaleY= 10

--- SIRUMHOI.p01 (plan) ---

Plan Title=Imported Plan 01
Version=Version 3.0.1  Mar 2001
Short Identifier=Imported Pla
Geom File=g01
Flow File=f01
Subcritical Flow
K Sum by GR= 0
Std Step Tol= 0.003
Critical Tol= 0.003
Num of Std Step Trials= 20
Max Error Tol= 0.1
Flow Tol Ratio= 0.001
Split Flow NTrial= 30
Split Flow Tol= 0.02
Split Flow Ratio= 0.02
Log Output Level= 0
Friction Slope Method= 1
Unsteady Friction Slope Method= 2
Parabolic Critical Depth
Global Vel Dist= 0 , 0 , 0
Global Log Level= 0
CheckData=True
Encroach Param=-1 ,0,0, 0
Computation Interval=1HOUR
Output Interval=1HOUR
Run HTab= 0
Run UNet= 0
Run PostProcess= 0
UNET Theta= 1
UNET ZTol= 0.02
UNET ZSATol= 0.1
UNET MxIter= 20
UNET MaxInSteps= 20
UNET DtIC= 0
UNET DtMin= 0
UNET MaxCRTS= 20
UNET WFStab= 2
UNET SFStab= 1
UNET WFX= 1
UNET SFX= 1
UNET Convert EG Bridges=-1
UNET Use Existing IB Tables=-1
Instantaneous Interval=1HOUR
Write IC File= 0
Write Velocity= 0
Write Detailed= 0

--- SIRUMHOI.f01 (steady flow) ---

Flow Title=Imported Flow 01
Version=Version 3.0.1  Mar 2001
Number of Profiles= 1
Profile Names=PF 1
River Rch & RM=RIVER-1,Reach-1         ,23.03
      75
Boundary for River Rch & Prof#=RIVER-1,Reach-1         , 1
Up Type= 0
Dn Type= 3
Dn Slope=.0109
DSS Import GetInterval= 0
DSS Import GetPeak= 0
DSS Import FillOption= 0

--- SIRUMHOI.g01 (geometry) ---

Geom Title=Imported Geom 01
Version=Version 3.0.1  Mar 2001

River Reach=RIVER-1         ,Reach-1
Reach XY= 2
              .5             .95              .5             .05

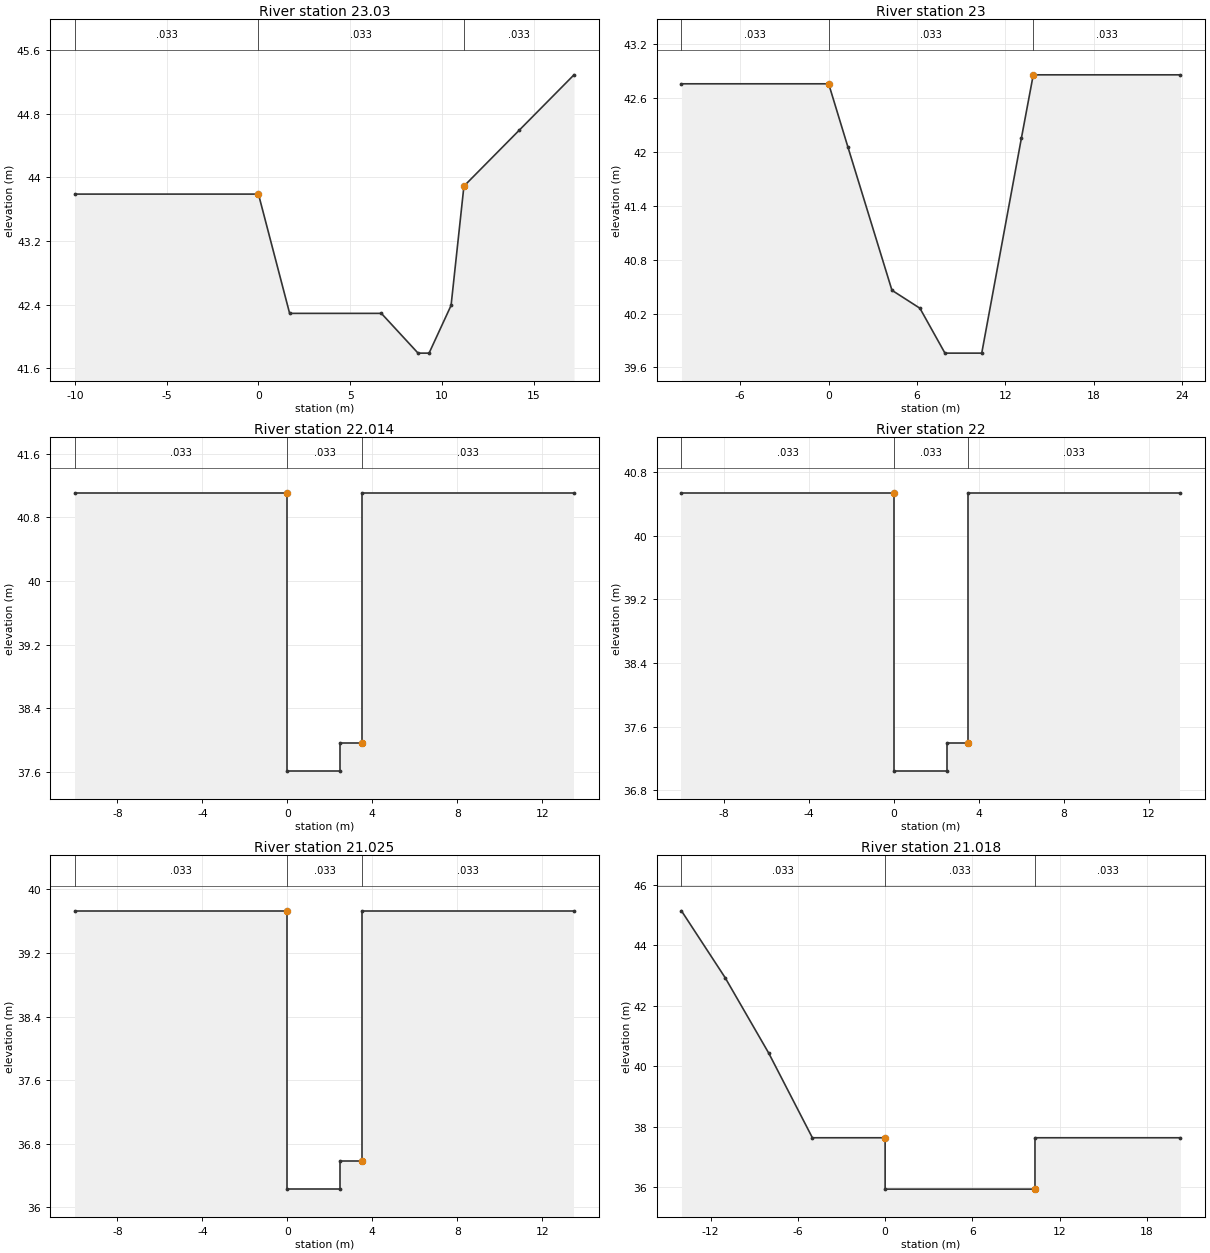
Type RM Length L Ch R = 1 ,23.03   ,30,30,30
#Sta/Elev= 10
     -10   43.79       0   43.79     1.7   42.29     6.7   42.29     8.7   41.79
     9.3   41.79    10.5   42.39    11.2   43.89    14.2   44.59    17.2   45.29
#Mann= 3 , 0 , 0
     -10    .033       0       0    .033       0    11.2    .033       0
Bank Sta=0,11.2
XS Rating Curve= 0
Exp/Cntr=.3,.1

Type RM Length L Ch R = 1 ,23      ,36,36,36
#Sta/Elev= 11
     -10   42.76       0   42.76       0   42.76     1.3   42.06     4.3   40.46
     6.2   40.26     7.9   39.76    10.4   39.76    13.1   42.16    13.9   42.86
    23.9   42.86
#Mann= 3 , 0 , 0
     -10    .033       0       0    .033       0    13.9    .033       0
Bank Sta=0,13.9
XS Rating Curve= 0
Exp/Cntr=.3,.1

Type RM Length L Ch R = 1 ,22.014  ,14,14,14
#Sta/Elev= 8
     -10   41.11       0   41.11       0   37.61     2.5   37.61     2.5   37.96
     3.5   37.96     3.5   41.11    13.5   41.11
#Mann= 3 , 0 , 0
     -10    .033       0       0    .033       0     3.5    .033       0
Bank Sta=0,3.5
XS Rating Curve= 0
Exp/Cntr=.3,.1

Type RM Length L Ch R = 1 ,22      ,25,25,25
#Sta/Elev= 8
     -10   40.54       0   40.54       0   37.04     2.5   37.04     2.5   37.39
     3.5   37.39     3.5   40.54    13.5   40.54
#Mann= 3 , 0 , 0
     -10    .033       0       0    .033       0     3.5    .033       0
Bank Sta=0,3.5
XS Rating Curve= 0
Exp/Cntr=.3,.1

Type RM Length L Ch R = 1 ,21.025  ,7,7,7
#Sta/Elev= 8
     -10   39.73       0   39.73       0   36.23     2.5   36.23     2.5   36.58
     3.5   36.58     3.5   39.73    13.5   39.73
#Mann= 3 , 0 , 0
     -10    .033       0       0    .033       0     3.5    .033       0
Bank Sta=0,3.5
XS Rating Curve= 0
Exp/Cntr=.3,.1

Type RM Length L Ch R = 1 ,21.018  ,10,10,10
#Sta/Elev= 9
     -14   45.14     -11   42.93      -8   40.43      -5   37.63       0   37.63
       0   35.93    10.3   35.93    10.3   37.63    20.3   37.63
#Mann= 3 , 0 , 0
     -14    .033       0       0    .033       0    10.3    .033       0
Bank Sta=0,10.3
XS Rating Curve= 0
Exp/Cntr=.3,.1

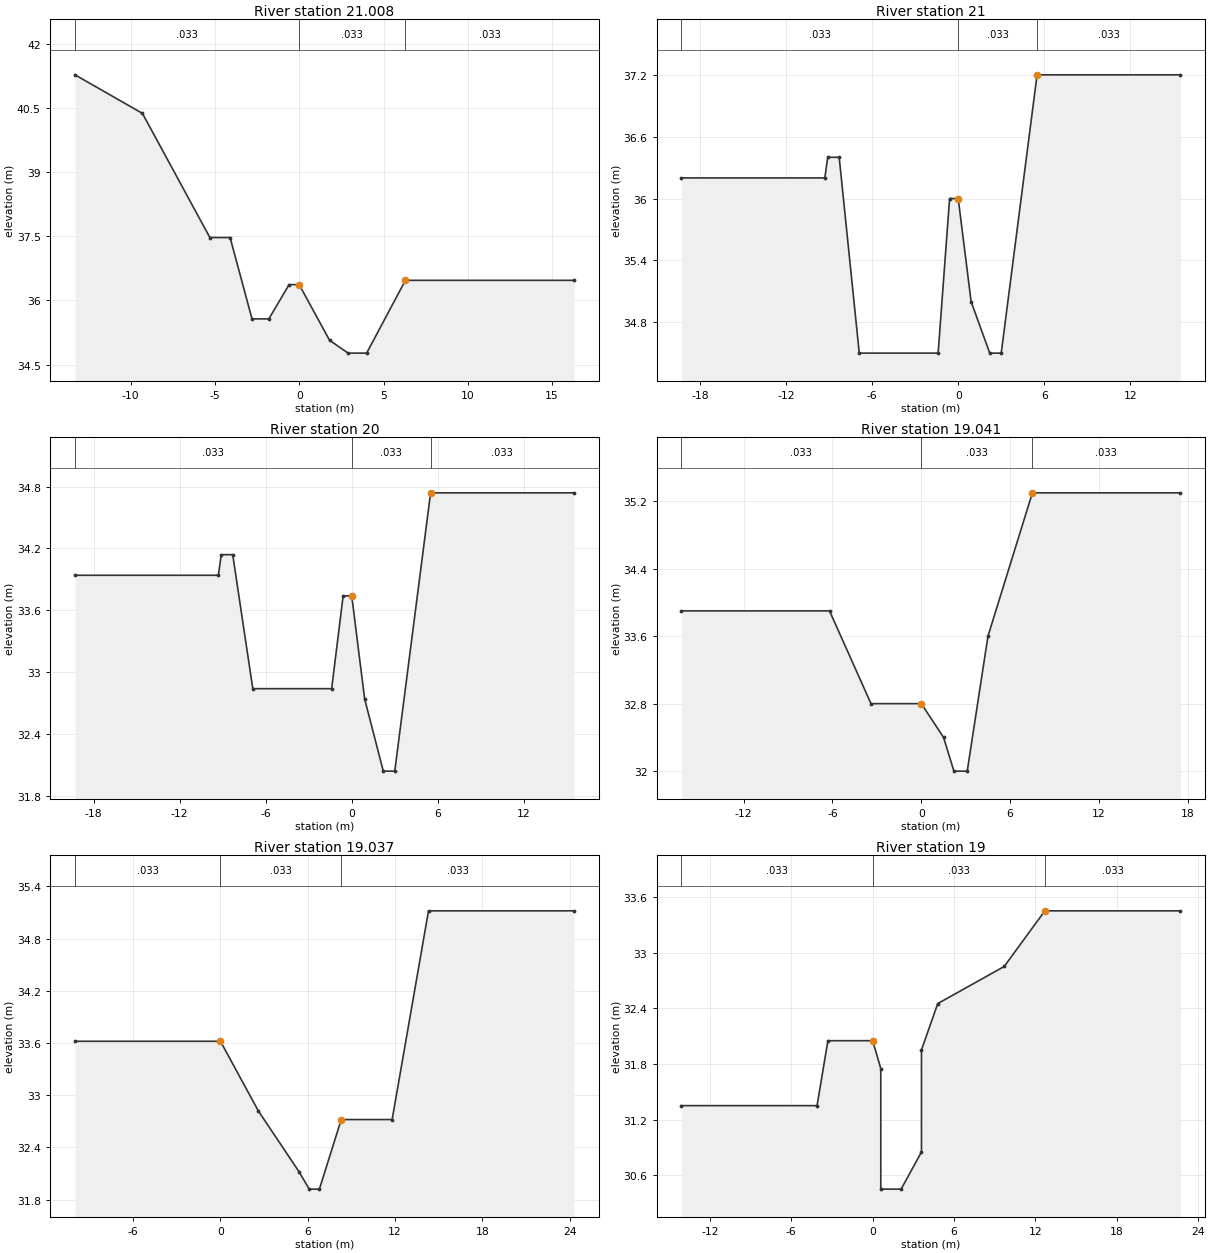
Type RM Length L Ch R = 1 ,21.008  ,8,8,8
#Sta/Elev= 13
   -13.3   41.27    -9.3   40.37    -5.3   37.47    -4.1   37.47    -2.8   35.57
    -1.8   35.57     -.6   36.37       0   36.37     1.8   35.07     2.9   34.77
       4   34.77     6.3   36.47    16.3   36.47
#Mann= 3 , 0 , 0
   -13.3    .033       0       0    .033       0     6.3    .033       0
Bank Sta=0,6.3
XS Rating Curve= 0
Exp/Cntr=.3,.1

Type RM Length L Ch R = 1 ,21      ,50,50,50
#Sta/Elev= 13
   -19.3    36.2    -9.3    36.2    -9.1    36.4    -8.3    36.4    -6.9    34.5
    -1.4    34.5     -.6      36       0      36      .9      35     2.2    34.5
       3    34.5     5.5    37.2    15.5    37.2
#Mann= 3 , 0 , 0
   -19.3    .033       0       0    .033       0     5.5    .033       0
Bank Sta=0,5.5
XS Rating Curve= 0
Exp/Cntr=.3,.1

Type RM Length L Ch R = 1 ,20      ,9,9,9
#Sta/Elev= 13
   -19.3   33.94    -9.3   33.94    -9.1   34.14    -8.3   34.14    -6.9   32.84
    -1.4   32.84     -.6   33.74       0   33.74      .9   32.74     2.2   32.04
       3   32.04     5.5   34.74    15.5   34.74
#Mann= 3 , 0 , 0
   -19.3    .033       0       0    .033       0     5.5    .033       0
Bank Sta=0,5.5
XS Rating Curve= 0
Exp/Cntr=.3,.1

Type RM Length L Ch R = 1 ,19.041  ,4,4,4
#Sta/Elev= 10
   -16.2    33.9    -6.2    33.9    -3.4    32.8       0    32.8     1.5    32.4
     2.2      32     3.1      32     4.5    33.6     7.5    35.3    17.5    35.3
#Mann= 3 , 0 , 0
   -16.2    .033       0       0    .033       0     7.5    .033       0
Bank Sta=0,7.5
XS Rating Curve= 0
Exp/Cntr=.3,.1

Type RM Length L Ch R = 1 ,19.037  ,37,37,37
#Sta/Elev= 10
     -10   33.62       0   33.62     2.6   32.82     5.4   32.12     6.1   31.92
     6.8   31.92     8.3   32.72    11.8   32.72    14.3   35.12    24.3   35.12
#Mann= 3 , 0 , 0
     -10    .033       0       0    .033       0     8.3    .033       0
Bank Sta=0,8.3
XS Rating Curve= 0
Exp/Cntr=.3,.1

Type RM Length L Ch R = 1 ,19      ,44,44,44
#Sta/Elev= 13
   -14.1   31.35    -4.1   31.35    -3.3   32.05       0   32.05      .6   31.75
      .6   30.45     2.1   30.45     3.6   30.85     3.6   31.95     4.8   32.45
     9.7   32.85    12.7   33.45    22.7   33.45
#Mann= 3 , 0 , 0
   -14.1    .033       0       0    .033       0    12.7    .033       0
Bank Sta=0,12.7
XS Rating Curve= 0
Exp/Cntr=.3,.1

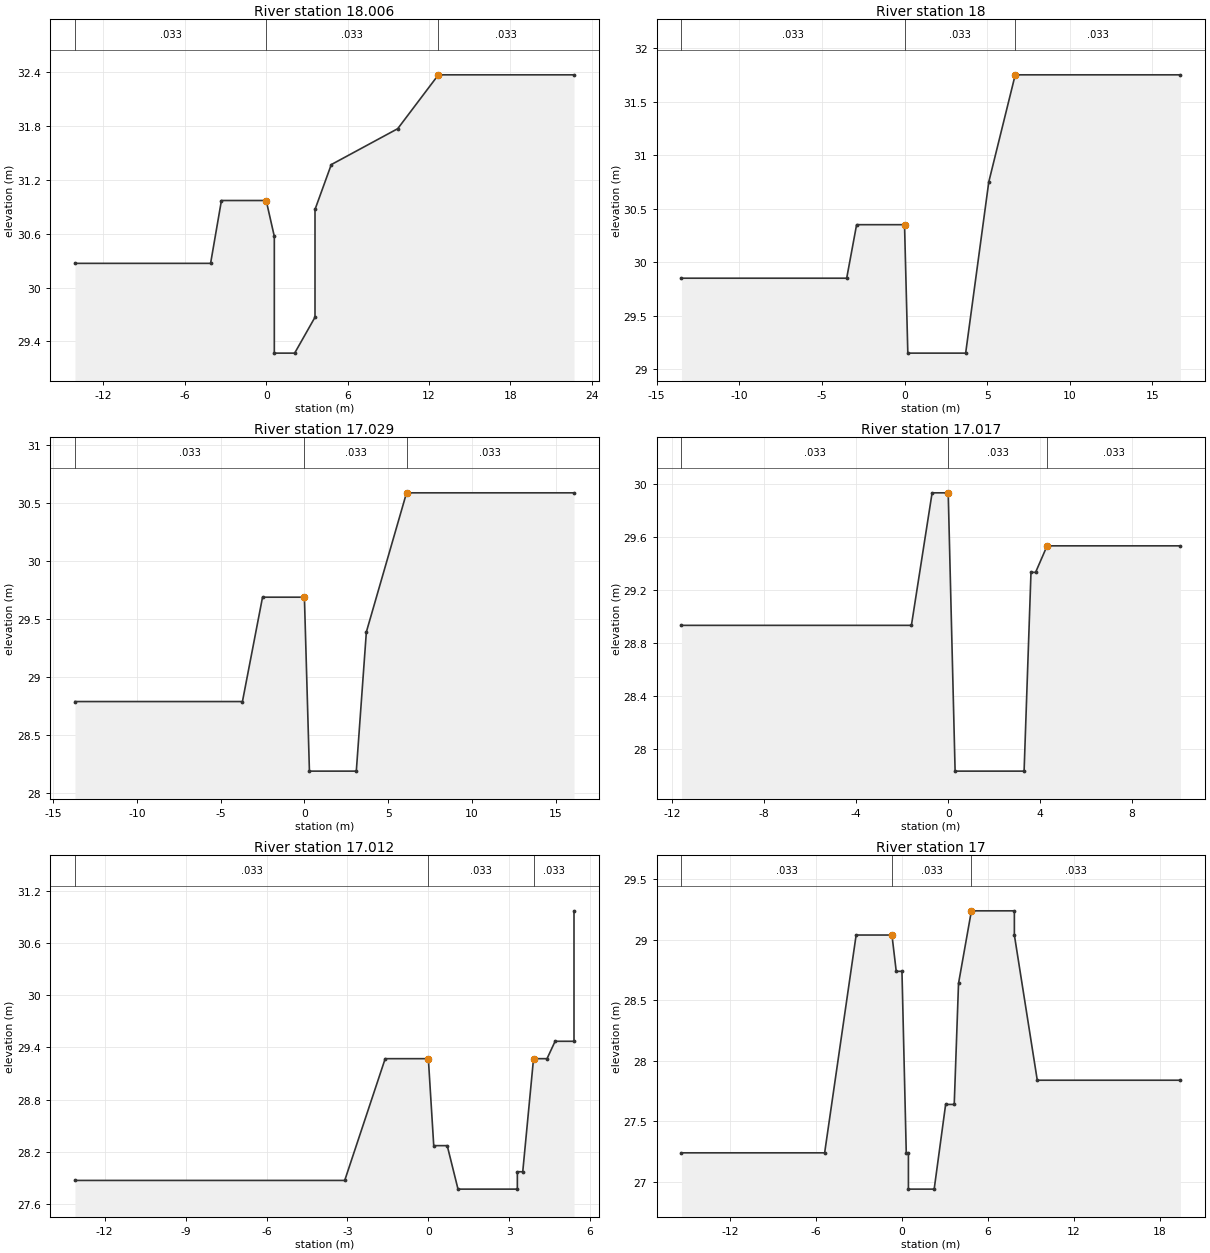
Type RM Length L Ch R = 1 ,18.006  ,6,6,6
#Sta/Elev= 13
   -14.1   30.27    -4.1   30.27    -3.3   30.97       0   30.97      .6   30.57
      .6   29.27     2.1   29.27     3.6   29.67     3.6   30.87     4.8   31.37
     9.7   31.77    12.7   32.37    22.7   32.37
#Mann= 3 , 0 , 0
   -14.1    .033       0       0    .033       0    12.7    .033       0
Bank Sta=0,12.7
XS Rating Curve= 0
Exp/Cntr=.3,.1

Type RM Length L Ch R = 1 ,18      ,21,21,21
#Sta/Elev= 9
   -13.5   29.85    -3.5   29.85    -2.9   30.35       0   30.35      .2   29.15
     3.7   29.15     5.1   30.75     6.7   31.75    16.7   31.75
#Mann= 3 , 0 , 0
   -13.5    .033       0       0    .033       0     6.7    .033       0
Bank Sta=0,6.7
XS Rating Curve= 0
Exp/Cntr=.3,.1

Type RM Length L Ch R = 1 ,17.029  ,12,12,12
#Sta/Elev= 9
   -13.7   28.79    -3.7   28.79    -2.5   29.69       0   29.69      .3   28.19
     3.1   28.19     3.7   29.39     6.1   30.59    16.1   30.59
#Mann= 3 , 0 , 0
   -13.7    .033       0       0    .033       0     6.1    .033       0
Bank Sta=0,6.1
XS Rating Curve= 0
Exp/Cntr=.3,.1

Type RM Length L Ch R = 1 ,17.017  ,5,5,5
#Sta/Elev= 10
   -11.6   28.93    -1.6   28.93     -.7   29.93       0   29.93      .3   27.83
     3.3   27.83     3.6   29.33     3.8   29.33     4.3   29.53    10.1   29.53
#Mann= 3 , 0 , 0
   -11.6    .033       0       0    .033       0     4.3    .033       0
Bank Sta=0,4.3
XS Rating Curve= 0
Exp/Cntr=.3,.1

Type RM Length L Ch R = 1 ,17.012  ,12,12,12
#Sta/Elev= 15
   -13.1   27.87    -3.1   27.87    -1.6   29.27       0   29.27      .2   28.27
      .7   28.27     1.1   27.77     3.3   27.77     3.3   27.97     3.5   27.97
     3.9   29.27     4.4   29.27     4.7   29.47     5.4   29.47     5.4   30.97
#Mann= 3 , 0 , 0
   -13.1    .033       0       0    .033       0     3.9    .033       0
Bank Sta=0,3.9
XS Rating Curve= 0
Exp/Cntr=.3,.1

Type RM Length L Ch R = 1 ,17      ,50,50,50
#Sta/Elev= 18
   -15.4   27.24    -5.4   27.24    -3.2   29.04     -.7   29.04     -.4   28.74
       0   28.74      .3   27.24     .45   27.24     .45   26.94    2.25   26.94
    3.05   27.64    3.65   27.64    3.95   28.64    4.85   29.24    7.85   29.24
    7.85   29.04    9.45   27.84   19.45   27.84
#Mann= 3 , 0 , 0
   -15.4    .033       0     -.7    .033       0    4.85    .033       0
Bank Sta=-.7,4.85
XS Rating Curve= 0
Exp/Cntr=.3,.1

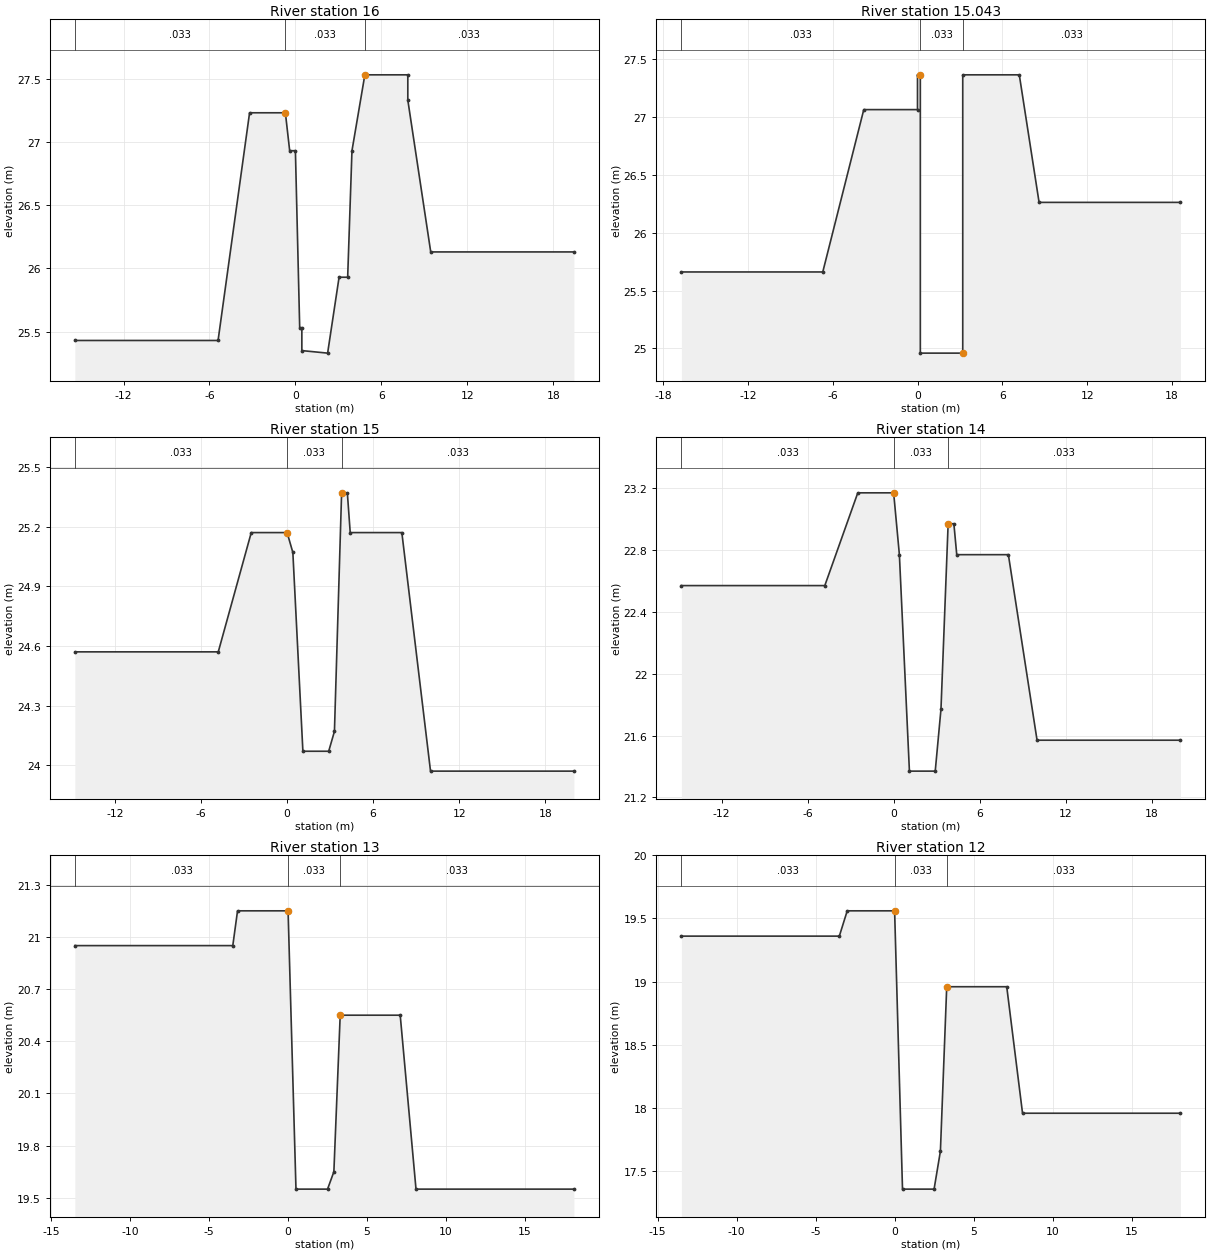
Type RM Length L Ch R = 1 ,16      ,7,7,7
#Sta/Elev= 18
   -15.4   25.43    -5.4   25.43    -3.2   27.23     -.7   27.23     -.4   26.93
       0   26.93      .3   25.53     .45   25.53     .45   25.35    2.25   25.33
    3.05   25.93    3.65   25.93    3.95   26.93    4.85   27.53    7.85   27.53
    7.85   27.33    9.45   26.13   19.45   26.13
#Mann= 3 , 0 , 0
   -15.4    .033       0     -.7    .033       0    4.85    .033       0
Bank Sta=-.7,4.85
XS Rating Curve= 0
Exp/Cntr=.3,.1

Type RM Length L Ch R = 1 ,15.043  ,43,43,43
#Sta/Elev= 12
   -16.7   25.66    -6.7   25.66    -3.8   27.06       0   27.06       0   27.36
      .2   27.36      .2   24.96     3.2   24.96     3.2   27.36     7.2   27.36
     8.6   26.26    18.6   26.26
#Mann= 3 , 0 , 0
   -16.7    .033       0      .2    .033       0     3.2    .033       0
Bank Sta=.2,3.2
XS Rating Curve= 0
Exp/Cntr=.3,.1

Type RM Length L Ch R = 1 ,15      ,50,50,50
#Sta/Elev= 14
   -14.8   24.57    -4.8   24.57    -2.5   25.17       0   25.17      .4   25.07
     1.1   24.07     2.9   24.07     3.3   24.17     3.8   25.37     4.2   25.37
     4.4   25.17       8   25.17      10   23.97      20   23.97
#Mann= 3 , 0 , 0
   -14.8    .033       0       0    .033       0     3.8    .033       0
Bank Sta=0,3.8
XS Rating Curve= 0
Exp/Cntr=.3,.1

Type RM Length L Ch R = 1 ,14      ,50,50,50
#Sta/Elev= 14
   -14.8   22.57    -4.8   22.57    -2.5   23.17       0   23.17      .4   22.77
     1.1   21.37     2.9   21.37     3.3   21.77     3.8   22.97     4.2   22.97
     4.4   22.77       8   22.77      10   21.57      20   21.57
#Mann= 3 , 0 , 0
   -14.8    .033       0       0    .033       0     3.8    .033       0
Bank Sta=0,3.8
XS Rating Curve= 0
Exp/Cntr=.3,.1

Type RM Length L Ch R = 1 ,13      ,50,50,50
#Sta/Elev= 11
   -13.5   20.95    -3.5   20.95    -3.2   21.15       0   21.15      .5   19.55
     2.5   19.55     2.9   19.65     3.3   20.55     7.1   20.55     8.1   19.55
    18.1   19.55
#Mann= 3 , 0 , 0
   -13.5    .033       0       0    .033       0     3.3    .033       0
Bank Sta=0,3.3
XS Rating Curve= 0
Exp/Cntr=.3,.1

Type RM Length L Ch R = 1 ,12      ,21,21,21
#Sta/Elev= 11
   -13.5   19.36    -3.5   19.36      -3   19.56       0   19.56      .5   17.36
     2.5   17.36     2.9   17.66     3.3   18.96     7.1   18.96     8.1   17.96
    18.1   17.96
#Mann= 3 , 0 , 0
   -13.5    .033       0       0    .033       0     3.3    .033       0
Bank Sta=0,3.3
XS Rating Curve= 0
Exp/Cntr=.3,.1

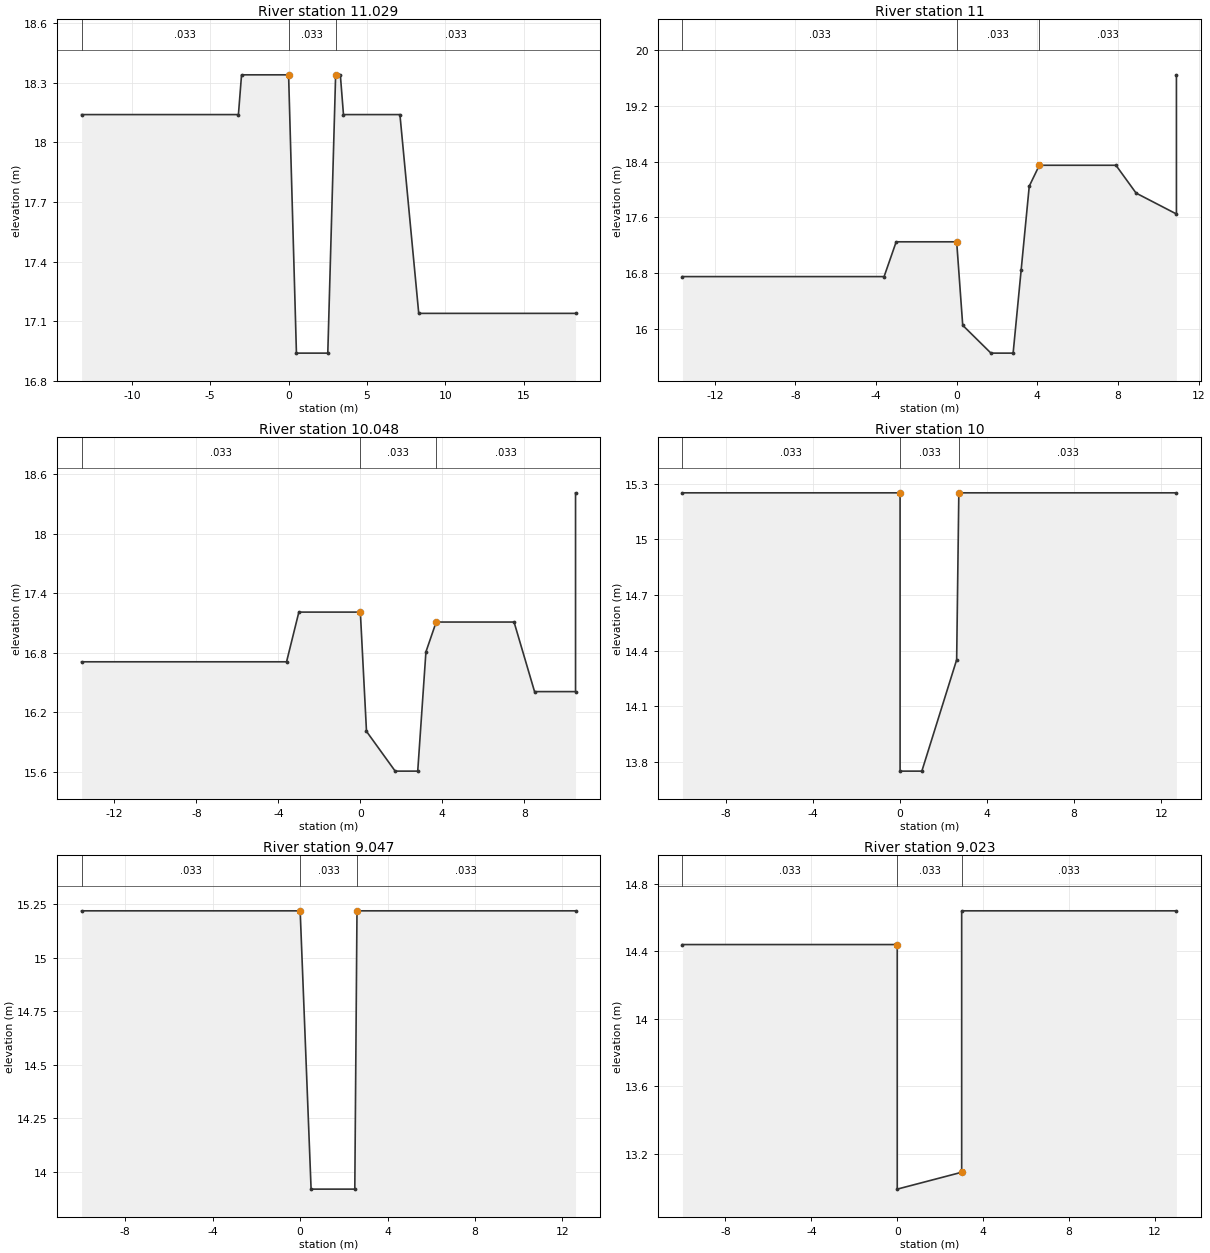
Type RM Length L Ch R = 1 ,11.029  ,29,29,29
#Sta/Elev= 12
   -13.2   18.14    -3.2   18.14      -3   18.34       0   18.34      .5   16.94
     2.5   16.94       3   18.34     3.3   18.34     3.5   18.14     7.1   18.14
     8.3   17.14    18.3   17.14
#Mann= 3 , 0 , 0
   -13.2    .033       0       0    .033       0       3    .033       0
Bank Sta=0,3
XS Rating Curve= 0
Exp/Cntr=.3,.1

Type RM Length L Ch R = 1 ,11      ,2,2,2
#Sta/Elev= 14
   -13.6   16.75    -3.6   16.75      -3   17.25       0   17.25      .3   16.05
     1.7   15.65     2.8   15.65     3.2   16.85     3.6   18.05     4.1   18.35
     7.9   18.35     8.9   17.95    10.9   17.65    10.9   19.65
#Mann= 3 , 0 , 0
   -13.6    .033       0       0    .033       0     4.1    .033       0
Bank Sta=0,4.1
XS Rating Curve= 0
Exp/Cntr=.3,.1

Type RM Length L Ch R = 1 ,10.048  ,48,48,48
#Sta/Elev= 13
   -13.6   16.71    -3.6   16.71      -3   17.21       0   17.21      .3   16.01
     1.7   15.61     2.8   15.61     3.2   16.81     3.7   17.11     7.5   17.11
     8.5   16.41    10.5   16.41    10.5   18.41
#Mann= 3 , 0 , 0
   -13.6    .033       0       0    .033       0     3.7    .033       0
Bank Sta=0,3.7
XS Rating Curve= 0
Exp/Cntr=.3,.1

Type RM Length L Ch R = 1 ,10      ,3,3,3
#Sta/Elev= 7
     -10   15.25       0   15.25       0   13.75       1   13.75     2.6   14.35
     2.7   15.25    12.7   15.25
#Mann= 3 , 0 , 0
     -10    .033       0       0    .033       0     2.7    .033       0
Bank Sta=0,2.7
XS Rating Curve= 0
Exp/Cntr=.3,.1

Type RM Length L Ch R = 1 ,9.047   ,24,24,24
#Sta/Elev= 6
     -10   15.22       0   15.22      .5   13.92     2.5   13.92     2.6   15.22
    12.6   15.22
#Mann= 3 , 0 , 0
     -10    .033       0       0    .033       0     2.6    .033       0
Bank Sta=0,2.6
XS Rating Curve= 0
Exp/Cntr=.3,.1

Type RM Length L Ch R = 1 ,9.023   ,9,9,9
#Sta/Elev= 6
     -10   14.44       0   14.44       0   12.99       3   13.09       3   14.64
      13   14.64
#Mann= 3 , 0 , 0
     -10    .033       0       0    .033       0       3    .033       0
Bank Sta=0,3
XS Rating Curve= 0
Exp/Cntr=.3,.1

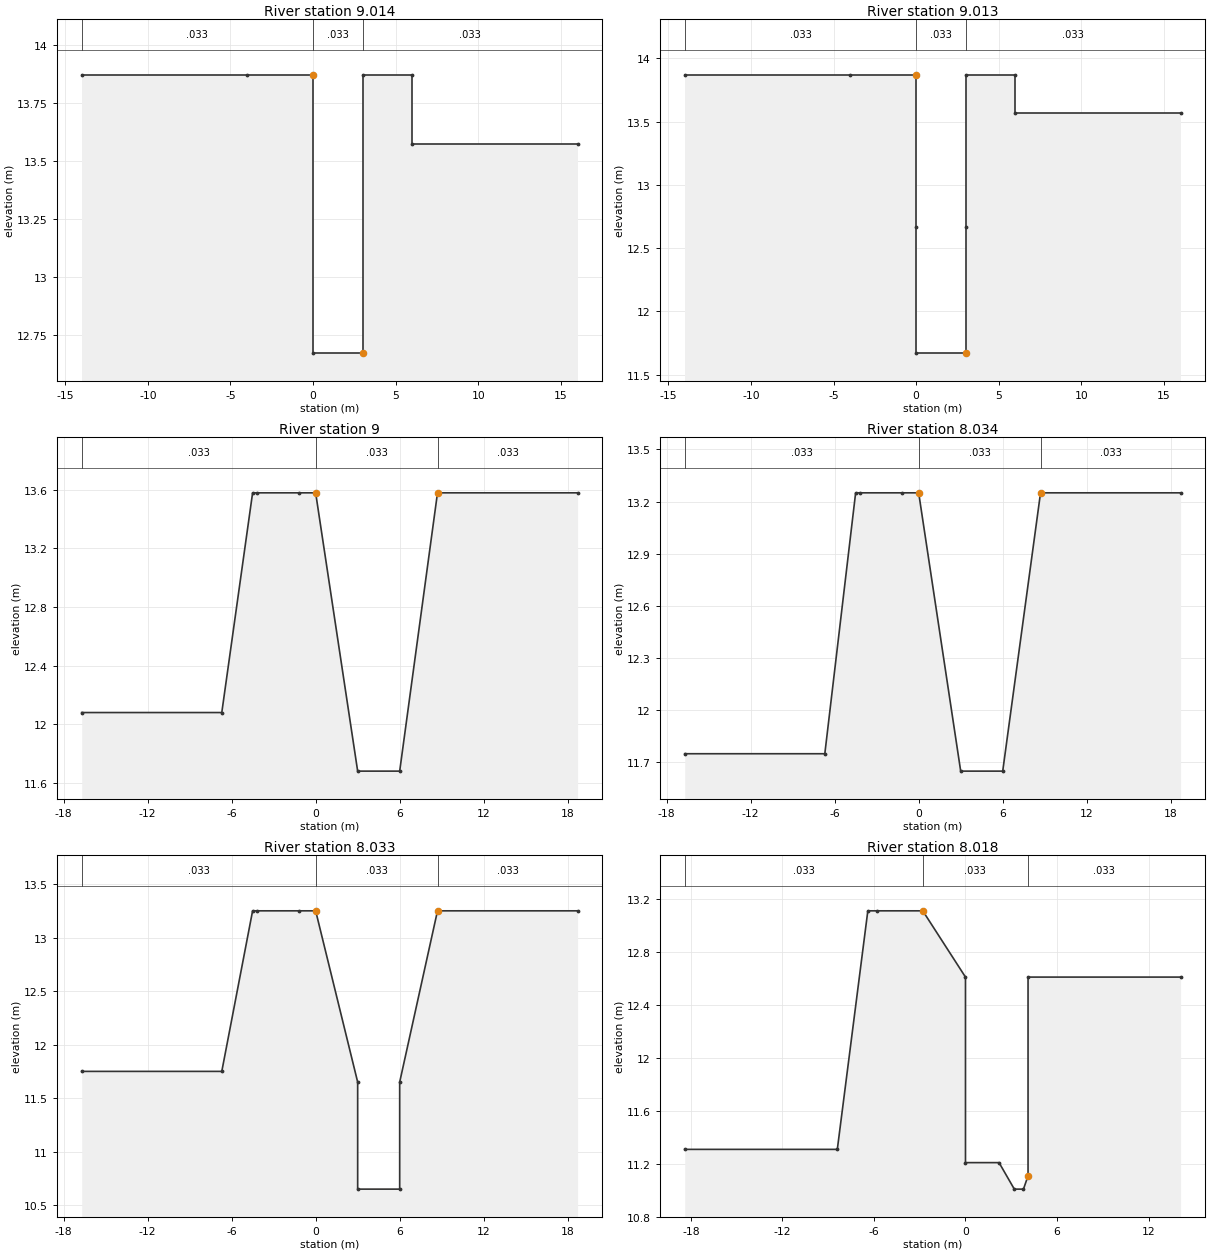
Type RM Length L Ch R = 1 ,9.014   ,1,1,1
#Sta/Elev= 9
     -14   13.87      -4   13.87       0   13.87       0   12.67       3   12.67
       3   13.87       6   13.87       6   13.57      16   13.57
#Mann= 3 , 0 , 0
     -14    .033       0       0    .033       0       3    .033       0
Bank Sta=0,3
XS Rating Curve= 0
Exp/Cntr=.3,.1

Type RM Length L Ch R = 1 ,9.013   ,13,13,13
#Sta/Elev= 11
     -14   13.87      -4   13.87       0   13.87       0   12.67       0   11.67
       3   11.67       3   12.67       3   13.87       6   13.87       6   13.57
      16   13.57
#Mann= 3 , 0 , 0
     -14    .033       0       0    .033       0       3    .033       0
Bank Sta=0,3
XS Rating Curve= 0
Exp/Cntr=.3,.1

Type RM Length L Ch R = 1 ,9       ,16,16,16
#Sta/Elev= 10
   -16.7   12.08    -6.7   12.08    -4.5   13.58    -4.2   13.58    -1.2   13.58
       0   13.58       3   11.68       6   11.68     8.7   13.58    18.7   13.58
#Mann= 3 , 0 , 0
   -16.7    .033       0       0    .033       0     8.7    .033       0
Bank Sta=0,8.7
XS Rating Curve= 0
Exp/Cntr=.3,.1

Type RM Length L Ch R = 1 ,8.034   ,1,1,1
#Sta/Elev= 10
   -16.7   11.75    -6.7   11.75    -4.5   13.25    -4.2   13.25    -1.2   13.25
       0   13.25       3   11.65       6   11.65     8.7   13.25    18.7   13.25
#Mann= 3 , 0 , 0
   -16.7    .033       0       0    .033       0     8.7    .033       0
Bank Sta=0,8.7
XS Rating Curve= 0
Exp/Cntr=.3,.1

Type RM Length L Ch R = 1 ,8.033   ,15,15,15
#Sta/Elev= 12
   -16.7   11.75    -6.7   11.75    -4.5   13.25    -4.2   13.25    -1.2   13.25
       0   13.25       3   11.65       3   10.65       6   10.65       6   11.65
     8.7   13.25    18.7   13.25
#Mann= 3 , 0 , 0
   -16.7    .033       0       0    .033       0     8.7    .033       0
Bank Sta=0,8.7
XS Rating Curve= 0
Exp/Cntr=.3,.1

Type RM Length L Ch R = 1 ,8.018   ,13,13,13
#Sta/Elev= 13
   -18.4   11.31    -8.4   11.31    -6.4   13.11    -5.8   13.11    -2.8   13.11
       0   12.61       0   11.21     2.2   11.21     3.2   11.01     3.8   11.01
     4.1   11.11     4.1   12.61    14.1   12.61
#Mann= 3 , 0 , 0
   -18.4    .033       0    -2.8    .033       0     4.1    .033       0
Bank Sta=-2.8,4.1
XS Rating Curve= 0
Exp/Cntr=.3,.1

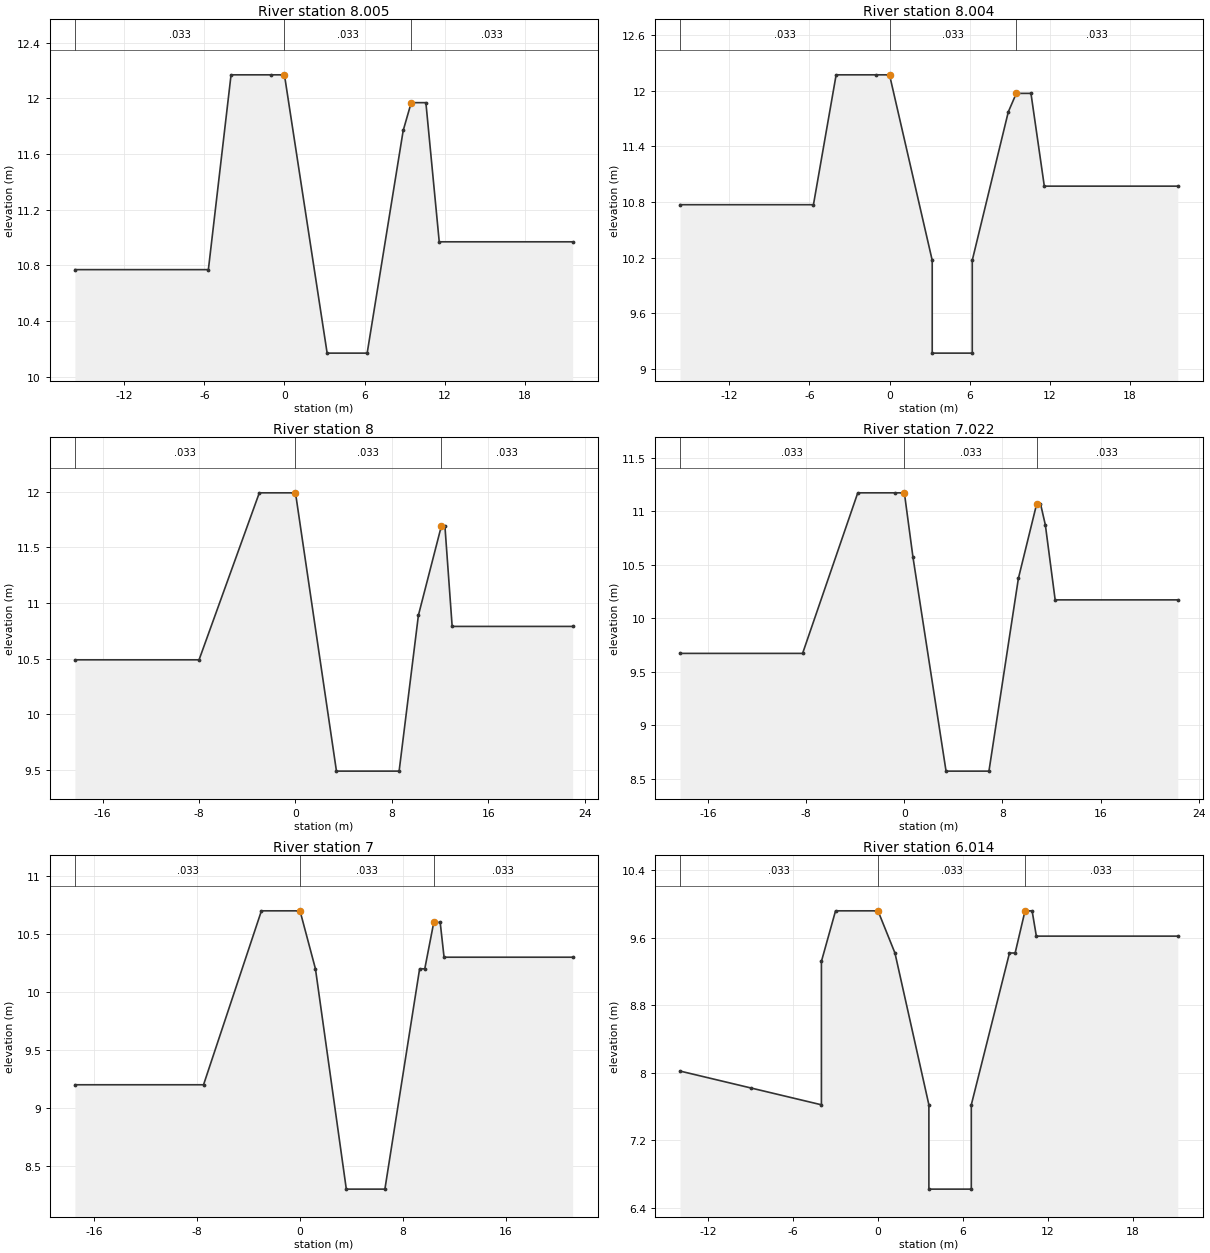
Type RM Length L Ch R = 1 ,8.005   ,1,1,1
#Sta/Elev= 12
   -15.7   10.77    -5.7   10.77      -4   12.17      -1   12.17       0   12.17
     3.2   10.17     6.2   10.17     8.9   11.77     9.5   11.97    10.6   11.97
    11.6   10.97    21.6   10.97
#Mann= 3 , 0 , 0
   -15.7    .033       0       0    .033       0     9.5    .033       0
Bank Sta=0,9.5
XS Rating Curve= 0
Exp/Cntr=.3,.1

Type RM Length L Ch R = 1 ,8.004   ,4,4,4
#Sta/Elev= 14
   -15.7   10.77    -5.7   10.77      -4   12.17      -1   12.17       0   12.17
     3.2   10.17     3.2    9.17     6.2    9.17     6.2   10.17     8.9   11.77
     9.5   11.97    10.6   11.97    11.6   10.97    21.6   10.97
#Mann= 3 , 0 , 0
   -15.7    .033       0       0    .033       0     9.5    .033       0
Bank Sta=0,9.5
XS Rating Curve= 0
Exp/Cntr=.3,.1

Type RM Length L Ch R = 1 ,8       ,28,28,28
#Sta/Elev= 11
   -18.3   10.49      -8   10.49      -3   11.99       0   11.99     3.4    9.49
     8.6    9.49    10.2   10.89    12.1   11.69    12.4   11.69      13   10.79
      23   10.79
#Mann= 3 , 0 , 0
   -18.3    .033       0       0    .033       0    12.1    .033       0
Bank Sta=0,12.1
XS Rating Curve= 0
Exp/Cntr=.3,.1

Type RM Length L Ch R = 1 ,7.022   ,22,22,22
#Sta/Elev= 14
   -18.3    9.67    -8.3    9.67    -3.8   11.17     -.8   11.17       0   11.17
      .7   10.57     3.4    8.57     6.9    8.57     9.3   10.37    10.8   11.07
    11.1   11.07    11.5   10.87    12.3   10.17    22.3   10.17
#Mann= 3 , 0 , 0
   -18.3    .033       0       0    .033       0    10.8    .033       0
Bank Sta=0,10.8
XS Rating Curve= 0
Exp/Cntr=.3,.1

Type RM Length L Ch R = 1 ,7       ,36,36,36
#Sta/Elev= 13
   -17.5     9.2    -7.5     9.2      -3    10.7       0    10.7     1.2    10.2
     3.6     8.3     6.6     8.3     9.3    10.2     9.7    10.2    10.4    10.6
    10.9    10.6    11.2    10.3    21.2    10.3
#Mann= 3 , 0 , 0
   -17.5    .033       0       0    .033       0    10.4    .033       0
Bank Sta=0,10.4
XS Rating Curve= 0
Exp/Cntr=.3,.1

Type RM Length L Ch R = 1 ,6.014   ,14,14,14
#Sta/Elev= 17
     -14    8.02      -9    7.82      -4    7.62      -4    9.32      -3    9.92
       0    9.92     1.2    9.42     3.6    7.62     3.6    6.62     6.6    6.62
     6.6    7.62     9.3    9.42     9.7    9.42    10.4    9.92    10.9    9.92
    11.2    9.62    21.2    9.62
#Mann= 3 , 0 , 0
     -14    .033       0       0    .033       0    10.4    .033       0
Bank Sta=0,10.4
XS Rating Curve= 0
Exp/Cntr=.3,.1

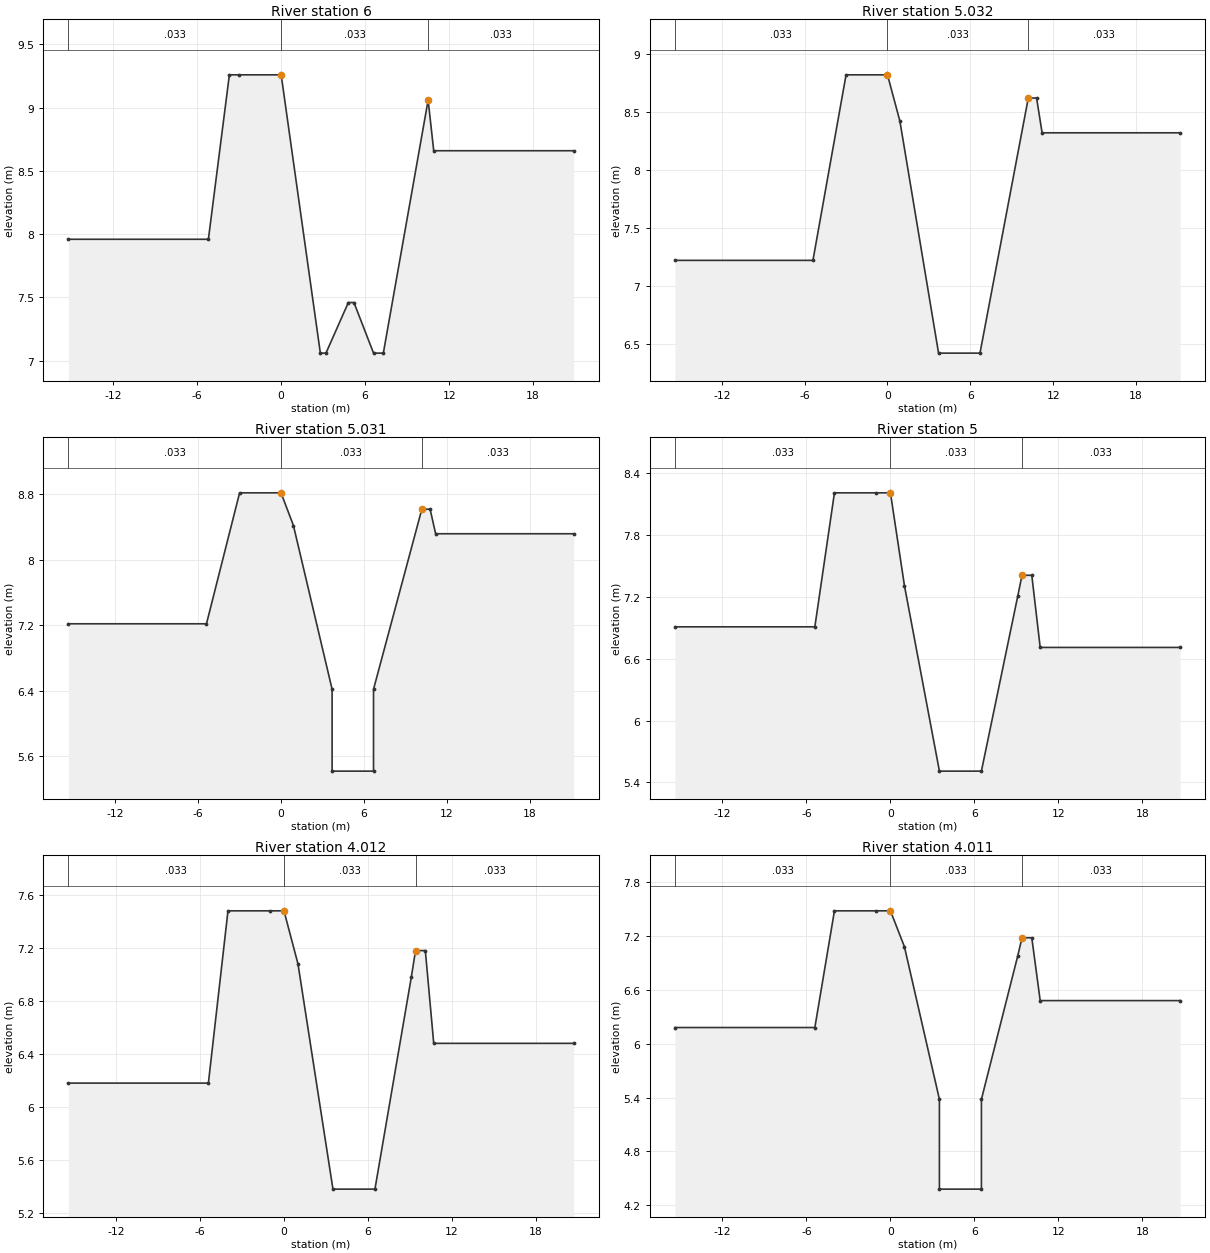
Type RM Length L Ch R = 1 ,6       ,18,18,18
#Sta/Elev= 14
   -15.2    7.96    -5.2    7.96    -3.7    9.26      -3    9.26       0    9.26
     2.8    7.06     3.2    7.06     4.8    7.46     5.2    7.46     6.6    7.06
     7.3    7.06    10.5    9.06    10.9    8.66    20.9    8.66
#Mann= 3 , 0 , 0
   -15.2    .033       0       0    .033       0    10.5    .033       0
Bank Sta=0,10.5
XS Rating Curve= 0
Exp/Cntr=.3,.1

Type RM Length L Ch R = 1 ,5.032   ,1,1,1
#Sta/Elev= 11
   -15.4    7.22    -5.4    7.22      -3    8.82       0    8.82      .9    8.42
     3.7    6.42     6.7    6.42    10.2    8.62    10.8    8.62    11.2    8.32
    21.2    8.32
#Mann= 3 , 0 , 0
   -15.4    .033       0       0    .033       0    10.2    .033       0
Bank Sta=0,10.2
XS Rating Curve= 0
Exp/Cntr=.3,.1

Type RM Length L Ch R = 1 ,5.031   ,31,31,31
#Sta/Elev= 13
   -15.4    7.22    -5.4    7.22      -3    8.82       0    8.82      .9    8.42
     3.7    6.42     3.7    5.42     6.7    5.42     6.7    6.42    10.2    8.62
    10.8    8.62    11.2    8.32    21.2    8.32
#Mann= 3 , 0 , 0
   -15.4    .033       0       0    .033       0    10.2    .033       0
Bank Sta=0,10.2
XS Rating Curve= 0
Exp/Cntr=.3,.1

Type RM Length L Ch R = 1 ,5       ,38,38,38
#Sta/Elev= 13
   -15.4    6.91    -5.4    6.91      -4    8.21      -1    8.21       0    8.21
       1    7.31     3.5    5.51     6.5    5.51     9.1    7.21     9.4    7.41
    10.1    7.41    10.7    6.71    20.7    6.71
#Mann= 3 , 0 , 0
   -15.4    .033       0       0    .033       0     9.4    .033       0
Bank Sta=0,9.4
XS Rating Curve= 0
Exp/Cntr=.3,.1

Type RM Length L Ch R = 1 ,4.012   ,1,1,1
#Sta/Elev= 13
   -15.4    6.18    -5.4    6.18      -4    7.48      -1    7.48       0    7.48
       1    7.08     3.5    5.38     6.5    5.38     9.1    6.98     9.4    7.18
    10.1    7.18    10.7    6.48    20.7    6.48
#Mann= 3 , 0 , 0
   -15.4    .033       0       0    .033       0     9.4    .033       0
Bank Sta=0,9.4
XS Rating Curve= 0
Exp/Cntr=.3,.1

Type RM Length L Ch R = 1 ,4.011   ,11,11,11
#Sta/Elev= 15
   -15.4    6.18    -5.4    6.18      -4    7.48      -1    7.48       0    7.48
       1    7.08     3.5    5.38     3.5    4.38     6.5    4.38     6.5    5.38
     9.1    6.98     9.4    7.18    10.1    7.18    10.7    6.48    20.7    6.48
#Mann= 3 , 0 , 0
   -15.4    .033       0       0    .033       0     9.4    .033       0
Bank Sta=0,9.4
XS Rating Curve= 0
Exp/Cntr=.3,.1