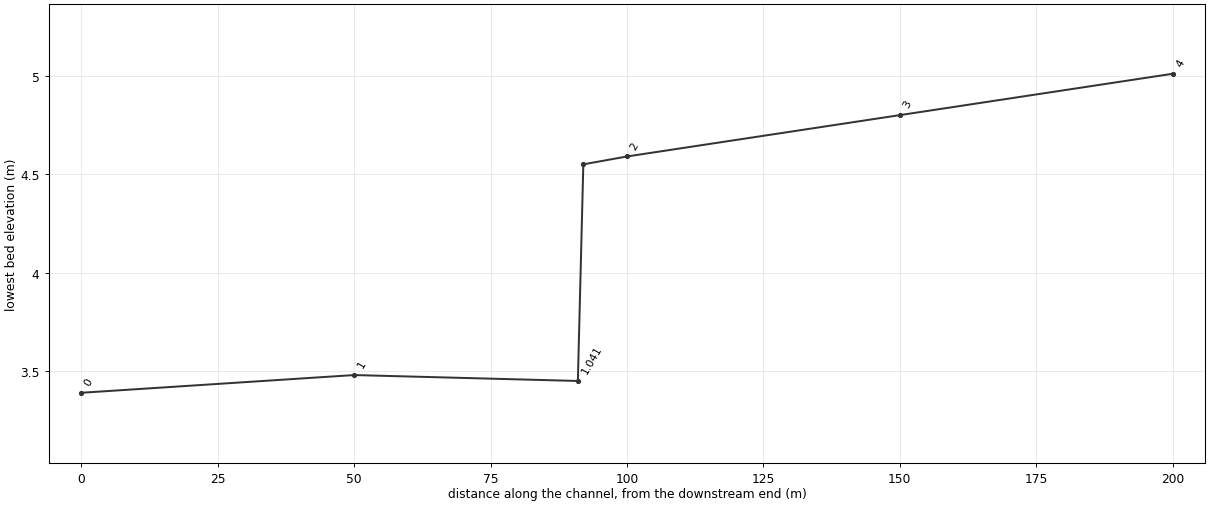
HEC-RAS study SIRUMHOI.prj: SIRUMHOI

--- SIRUMHOI.g01 (geometry) --- (continued)

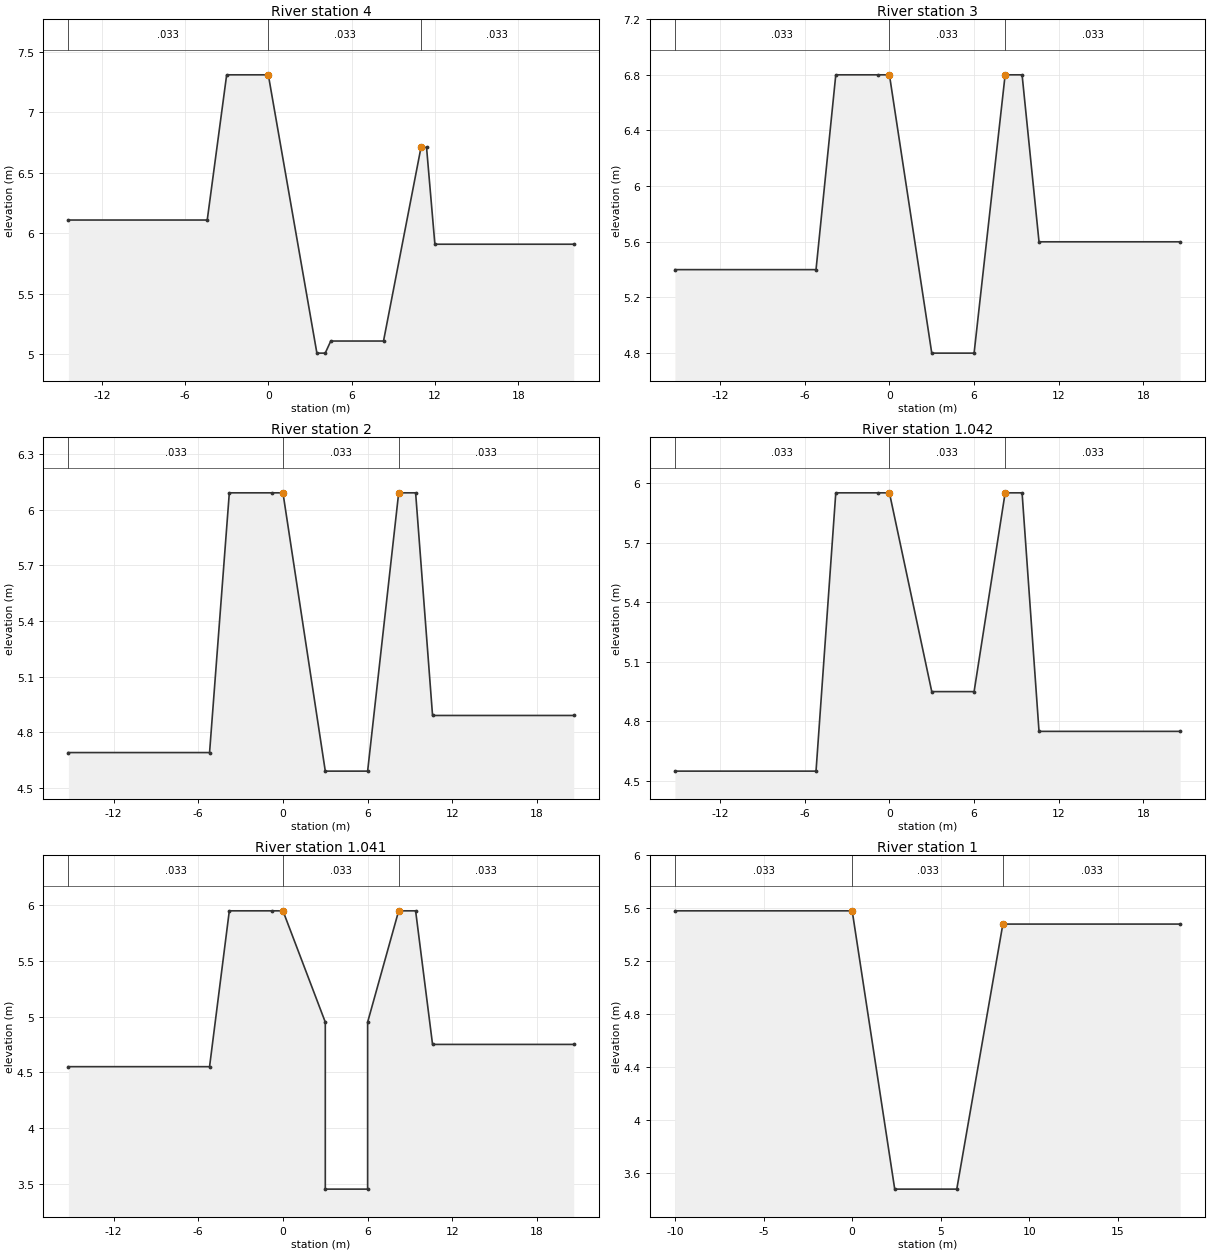
Type RM Length L Ch R = 1 ,4       ,50,50,50
#Sta/Elev= 12
   -14.4    6.11    -4.4    6.11      -3    7.31       0    7.31     3.5    5.01
     4.1    5.01     4.5    5.11     8.3    5.11      11    6.71    11.4    6.71
      12    5.91      22    5.91
#Mann= 3 , 0 , 0
   -14.4    .033       0       0    .033       0      11    .033       0
Bank Sta=0,11
XS Rating Curve= 0
Exp/Cntr=.3,.1

Type RM Length L Ch R = 1 ,3       ,50,50,50
#Sta/Elev= 11
   -15.2     5.4    -5.2     5.4    -3.8     6.8     -.8     6.8       0     6.8
       3     4.8       6     4.8     8.2     6.8     9.4     6.8    10.6     5.6
    20.6     5.6
#Mann= 3 , 0 , 0
   -15.2    .033       0       0    .033       0     8.2    .033       0
Bank Sta=0,8.2
XS Rating Curve= 0
Exp/Cntr=.3,.1

Type RM Length L Ch R = 1 ,2       ,8,8,8
#Sta/Elev= 11
   -15.2    4.69    -5.2    4.69    -3.8    6.09     -.8    6.09       0    6.09
       3    4.59       6    4.59     8.2    6.09     9.4    6.09    10.6    4.89
    20.6    4.89
#Mann= 3 , 0 , 0
   -15.2    .033       0       0    .033       0     8.2    .033       0
Bank Sta=0,8.2
XS Rating Curve= 0
Exp/Cntr=.3,.1

Type RM Length L Ch R = 1 ,1.042   ,1,1,1
#Sta/Elev= 11
   -15.2    4.55    -5.2    4.55    -3.8    5.95     -.8    5.95       0    5.95
       3    4.95       6    4.95     8.2    5.95     9.4    5.95    10.6    4.75
    20.6    4.75
#Mann= 3 , 0 , 0
   -15.2    .033       0       0    .033       0     8.2    .033       0
Bank Sta=0,8.2
XS Rating Curve= 0
Exp/Cntr=.3,.1

Type RM Length L Ch R = 1 ,1.041   ,41,41,41
#Sta/Elev= 13
   -15.2    4.55    -5.2    4.55    -3.8    5.95     -.8    5.95       0    5.95
       3    4.95       3    3.45       6    3.45       6    4.95     8.2    5.95
     9.4    5.95    10.6    4.75    20.6    4.75
#Mann= 3 , 0 , 0
   -15.2    .033       0       0    .033       0     8.2    .033       0
Bank Sta=0,8.2
XS Rating Curve= 0
Exp/Cntr=.3,.1

Type RM Length L Ch R = 1 ,1       ,50,50,50
#Sta/Elev= 6
     -10    5.58       0    5.58     2.4    3.48     5.9    3.48     8.5    5.48
    18.5    5.48
#Mann= 3 , 0 , 0
     -10    .033       0       0    .033       0     8.5    .033       0
Bank Sta=0,8.5
XS Rating Curve= 0
Exp/Cntr=.3,.1

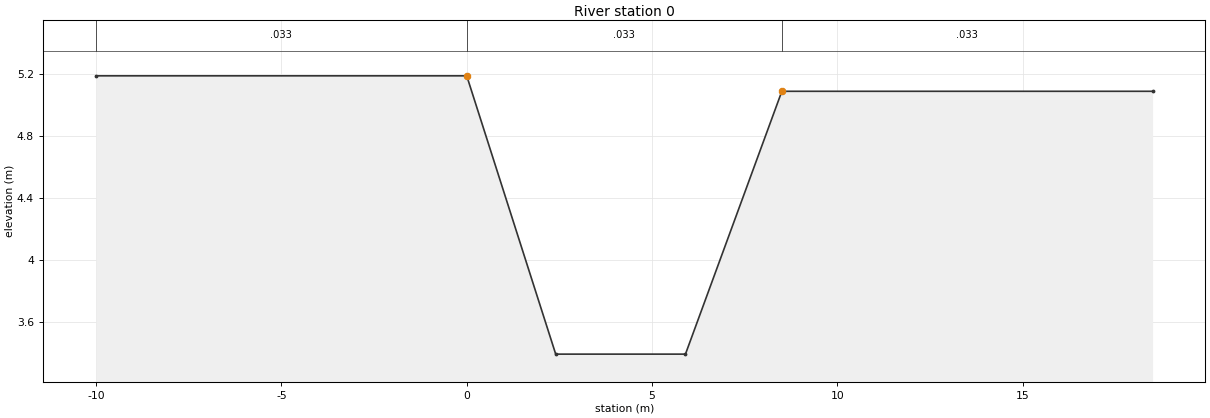
Type RM Length L Ch R = 1 ,0       ,0,0,0
#Sta/Elev= 6
     -10    5.19       0    5.19     2.4    3.39     5.9    3.39     8.5    5.09
    18.5    5.09
#Mann= 3 , 0 , 0
     -10    .033       0       0    .033       0     8.5    .033       0
Bank Sta=0,8.5
XS Rating Curve= 0
Exp/Cntr=.3,.1

Chan Stop Cuts=-1