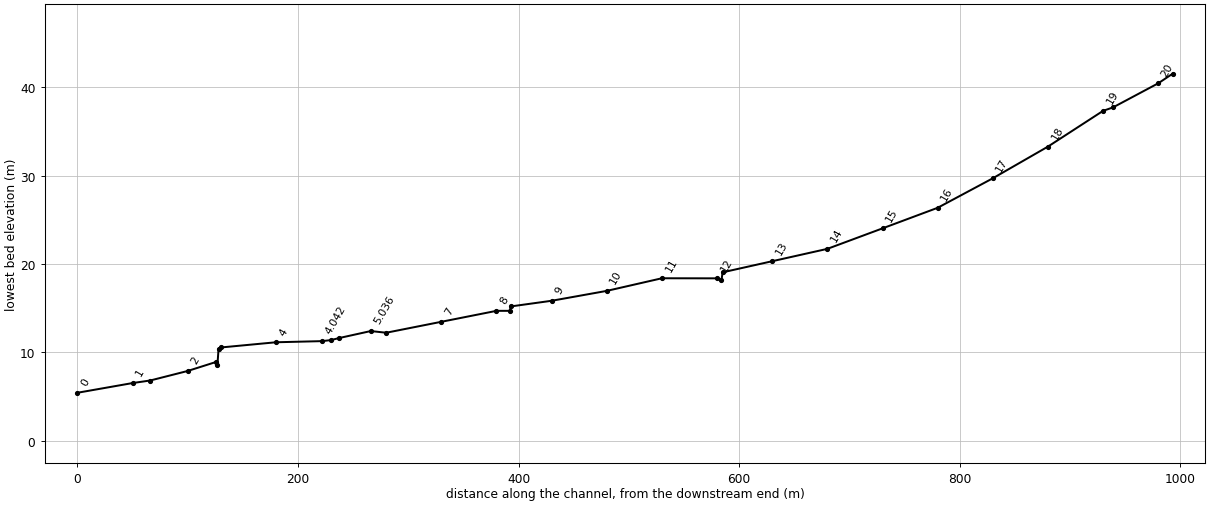
--- WEJUNG.prj (project) ---

Proj Title=WEJUNG
Current Plan=p01
Default Exp/Contr=.3,.1
SI Units
Geom File=g01
Flow File=f01
Plan File=p01
Y Axis Title=Elevation
X Axis Title(PF)=Main Channel Distance
X Axis Title(XS)=Station
BEGIN DESCRIPTION:
           BACK WATER COMPUTATION
      APPLICATION OF HEC-2 BY Samju Construction Engineering
      WEJOONG-STREEM : 30 YR
END DESCRIPTION:
DSS Export Rating Curves= 0
DSS Export Rating Curve Sorted= 0
DSS Export Volume Flow Curves= 0
DXF OffsetX= 0
DXF OffsetY= 0
DXF ScaleX= 1
DXF ScaleY= 10

--- WEJUNG.p01 (plan) ---

Plan Title=Imported Plan 01
Version=Version 3.0.1  Mar 2001
Short Identifier=Imported Pla
Geom File=g01
Flow File=f01
Subcritical Flow
K Sum by GR= 0
Std Step Tol= 0.003
Critical Tol= 0.003
Num of Std Step Trials= 20
Max Error Tol= 0.1
Flow Tol Ratio= 0.001
Split Flow NTrial= 30
Split Flow Tol= 0.02
Split Flow Ratio= 0.02
Log Output Level= 0
Friction Slope Method= 1
Unsteady Friction Slope Method= 2
Parabolic Critical Depth
Global Vel Dist= 0 , 0 , 0
Global Log Level= 0
CheckData=True
Encroach Param=-1 ,0,0, 0
Computation Interval=1HOUR
Output Interval=1HOUR
Run HTab= 0
Run UNet= 0
Run PostProcess= 0
UNET Theta= 1
UNET ZTol= 0.02
UNET ZSATol= 0.1
UNET MxIter= 20
UNET MaxInSteps= 20
UNET DtIC= 0
UNET DtMin= 0
UNET MaxCRTS= 20
UNET WFStab= 2
UNET SFStab= 1
UNET WFX= 1
UNET SFX= 1
UNET Convert EG Bridges=-1
UNET Use Existing IB Tables=-1
Instantaneous Interval=1HOUR
Write IC File= 0
Write Velocity= 0
Write Detailed= 0

--- WEJUNG.f01 (steady flow) ---

Flow Title=Imported Flow 01
Version=Version 3.0.1  Mar 2001
Number of Profiles= 1
Profile Names=PF 1
River Rch & RM=RIVER-1,Reach-1         ,20.013
      75
Boundary for River Rch & Prof#=RIVER-1,Reach-1         , 1
Up Type= 0
Dn Type= 3
Dn Slope=.0109
DSS Import GetInterval= 0
DSS Import GetPeak= 0
DSS Import FillOption= 0

--- WEJUNG.g01 (geometry) ---

Geom Title=Imported Geom 01
Version=Version 3.0.1  Mar 2001

River Reach=RIVER-1         ,Reach-1
Reach XY= 2
              .5             .95              .5             .05

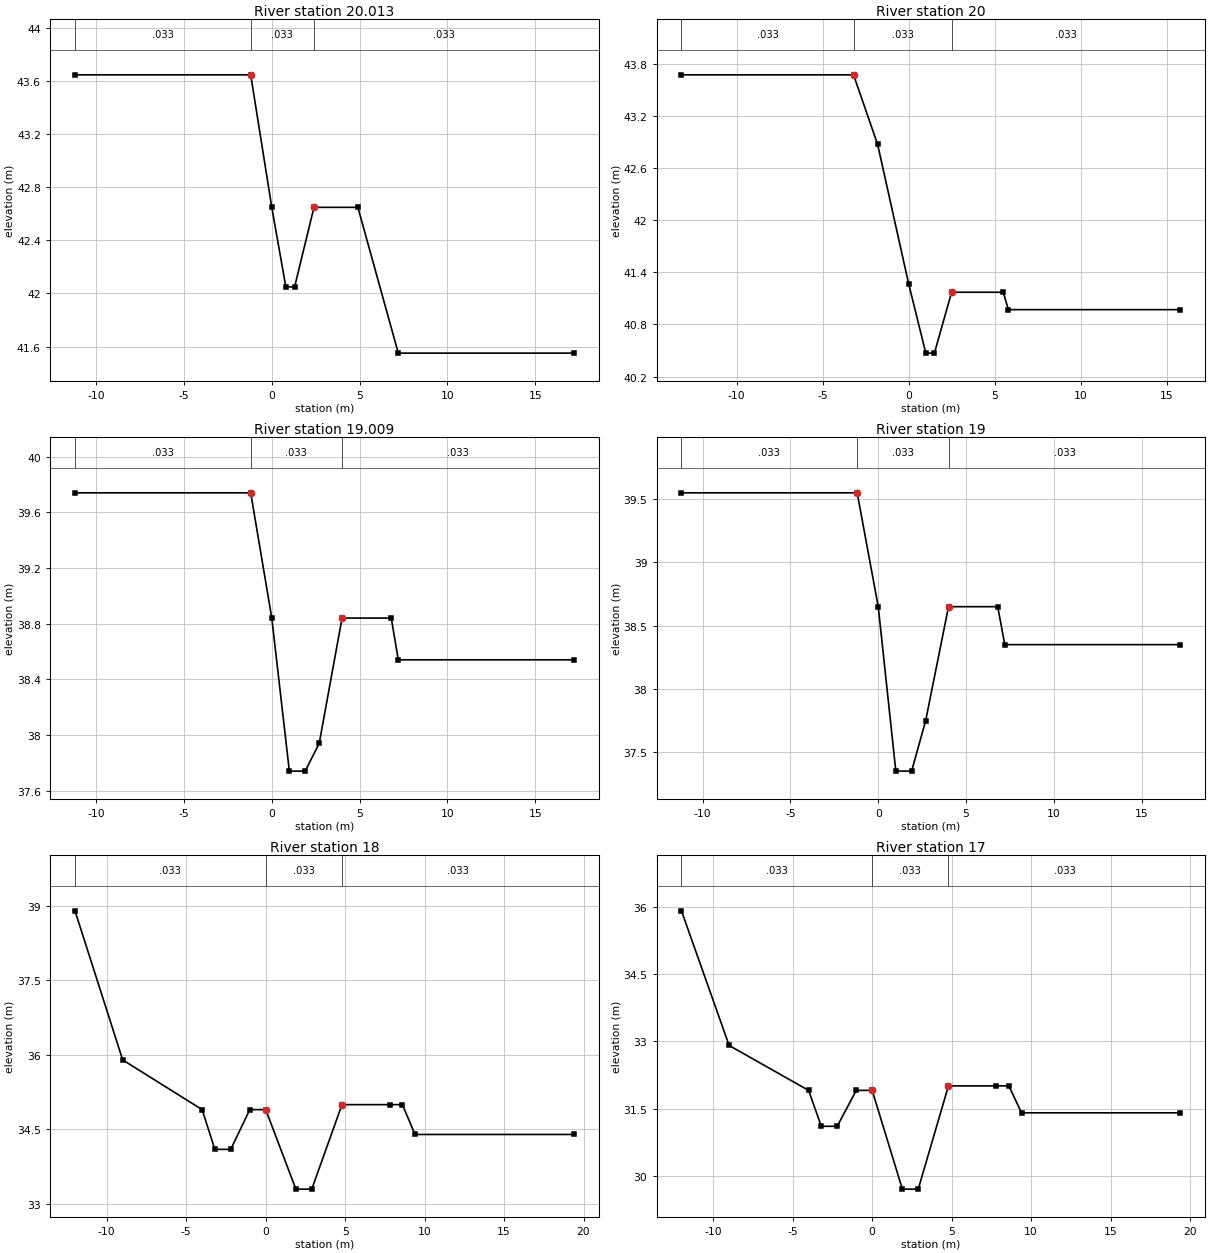
Type RM Length L Ch R = 1 ,20.013  ,13,13,13
#Sta/Elev= 9
   -11.2   43.65    -1.2   43.65       0   42.65      .8   42.05     1.3   42.05
     2.4   42.65     4.9   42.65     7.2   41.55    17.2   41.55
#Mann= 3 , 0 , 0
   -11.2    .033       0    -1.2    .033       0     2.4    .033       0
Bank Sta=-1.2,2.4
XS Rating Curve= 0
Exp/Cntr=.3,.1

Type RM Length L Ch R = 1 ,20      ,41,41,41
#Sta/Elev= 10
   -13.2   43.67    -3.2   43.67    -1.8   42.87       0   41.27       1   40.47
     1.5   40.47     2.5   41.17     5.5   41.17     5.8   40.97    15.8   40.97
#Mann= 3 , 0 , 0
   -13.2    .033       0    -3.2    .033       0     2.5    .033       0
Bank Sta=-3.2,2.5
XS Rating Curve= 0
Exp/Cntr=.3,.1

Type RM Length L Ch R = 1 ,19.009  ,9,9,9
#Sta/Elev= 10
   -11.2   39.74    -1.2   39.74       0   38.84       1   37.74     1.9   37.74
     2.7   37.94       4   38.84     6.8   38.84     7.2   38.54    17.2   38.54
#Mann= 3 , 0 , 0
   -11.2    .033       0    -1.2    .033       0       4    .033       0
Bank Sta=-1.2,4
XS Rating Curve= 0
Exp/Cntr=.3,.1

Type RM Length L Ch R = 1 ,19      ,50,50,50
#Sta/Elev= 10
   -11.2   39.55    -1.2   39.55       0   38.65       1   37.35     1.9   37.35
     2.7   37.75       4   38.65     6.8   38.65     7.2   38.35    17.2   38.35
#Mann= 3 , 0 , 0
   -11.2    .033       0    -1.2    .033       0       4    .033       0
Bank Sta=-1.2,4
XS Rating Curve= 0
Exp/Cntr=.3,.1

Type RM Length L Ch R = 1 ,18      ,50,50,50
#Sta/Elev= 14
     -12    38.9      -9    35.9      -4    34.9    -3.2    34.1    -2.2    34.1
      -1    34.9       0    34.9     1.9    33.3     2.9    33.3     4.8      35
     7.8      35     8.6      35     9.4    34.4    19.4    34.4
#Mann= 3 , 0 , 0
     -12    .033       0       0    .033       0     4.8    .033       0
Bank Sta=0,4.8
XS Rating Curve= 0
Exp/Cntr=.3,.1

Type RM Length L Ch R = 1 ,17      ,50,50,50
#Sta/Elev= 14
     -12   35.91      -9   32.91      -4   31.91    -3.2   31.11    -2.2   31.11
      -1   31.91       0   31.91     1.9   29.71     2.9   29.71     4.8   32.01
     7.8   32.01     8.6   32.01     9.4   31.41    19.4   31.41
#Mann= 3 , 0 , 0
     -12    .033       0       0    .033       0     4.8    .033       0
Bank Sta=0,4.8
XS Rating Curve= 0
Exp/Cntr=.3,.1

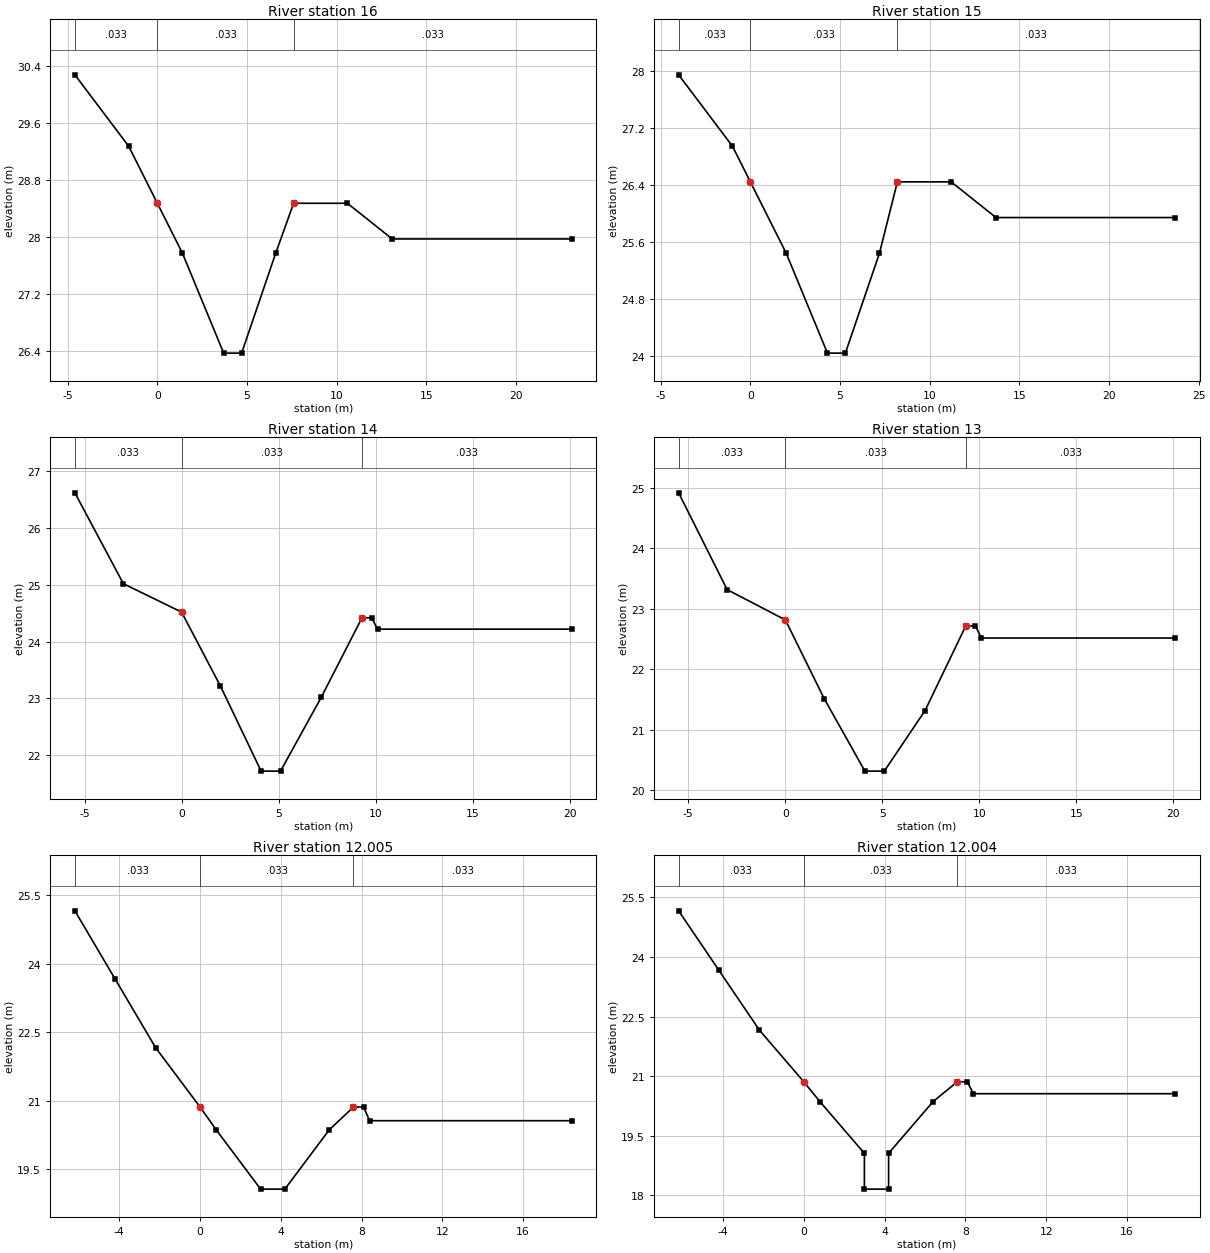
Type RM Length L Ch R = 1 ,16      ,50,50,50
#Sta/Elev= 11
    -4.6   30.27    -1.6   29.27       0   28.47     1.4   27.77     3.7   26.37
     4.7   26.37     6.6   27.77     7.6   28.47    10.6   28.47    13.1   27.97
    23.1   27.97
#Mann= 3 , 0 , 0
    -4.6    .033       0       0    .033       0     7.6    .033       0
Bank Sta=0,7.6
XS Rating Curve= 0
Exp/Cntr=.3,.1

Type RM Length L Ch R = 1 ,15      ,50,50,50
#Sta/Elev= 11
      -4   27.94      -1   26.94       0   26.44       2   25.44     4.3   24.04
     5.3   24.04     7.2   25.44     8.2   26.44    11.2   26.44    13.7   25.94
    23.7   25.94
#Mann= 3 , 0 , 0
      -4    .033       0       0    .033       0     8.2    .033       0
Bank Sta=0,8.2
XS Rating Curve= 0
Exp/Cntr=.3,.1

Type RM Length L Ch R = 1 ,14      ,50,50,50
#Sta/Elev= 11
    -5.5   26.62      -3   25.02       0   24.52       2   23.22     4.1   21.72
     5.1   21.72     7.2   23.02     9.3   24.42     9.8   24.42    10.1   24.22
    20.1   24.22
#Mann= 3 , 0 , 0
    -5.5    .033       0       0    .033       0     9.3    .033       0
Bank Sta=0,9.3
XS Rating Curve= 0
Exp/Cntr=.3,.1

Type RM Length L Ch R = 1 ,13      ,45,45,45
#Sta/Elev= 11
    -5.5   24.92      -3   23.32       0   22.82       2   21.52     4.1   20.32
     5.1   20.32     7.2   21.32     9.3   22.72     9.8   22.72    10.1   22.52
    20.1   22.52
#Mann= 3 , 0 , 0
    -5.5    .033       0       0    .033       0     9.3    .033       0
Bank Sta=0,9.3
XS Rating Curve= 0
Exp/Cntr=.3,.1

Type RM Length L Ch R = 1 ,12.005  ,1,1,1
#Sta/Elev= 12
    -6.2   25.16    -4.2   23.66    -2.2   22.16       0   20.86      .8   20.36
       3   19.06     4.2   19.06     6.4   20.36     7.6   20.86     8.1   20.86
     8.4   20.56    18.4   20.56
#Mann= 3 , 0 , 0
    -6.2    .033       0       0    .033       0     7.6    .033       0
Bank Sta=0,7.6
XS Rating Curve= 0
Exp/Cntr=.3,.1

Type RM Length L Ch R = 1 ,12.004  ,4,4,4
#Sta/Elev= 14
    -6.2   25.16    -4.2   23.66    -2.2   22.16       0   20.86      .8   20.36
       3   19.06       3   18.16     4.2   18.16     4.2   19.06     6.4   20.36
     7.6   20.86     8.1   20.86     8.4   20.56    18.4   20.56
#Mann= 3 , 0 , 0
    -6.2    .033       0       0    .033       0     7.6    .033       0
Bank Sta=0,7.6
XS Rating Curve= 0
Exp/Cntr=.3,.1

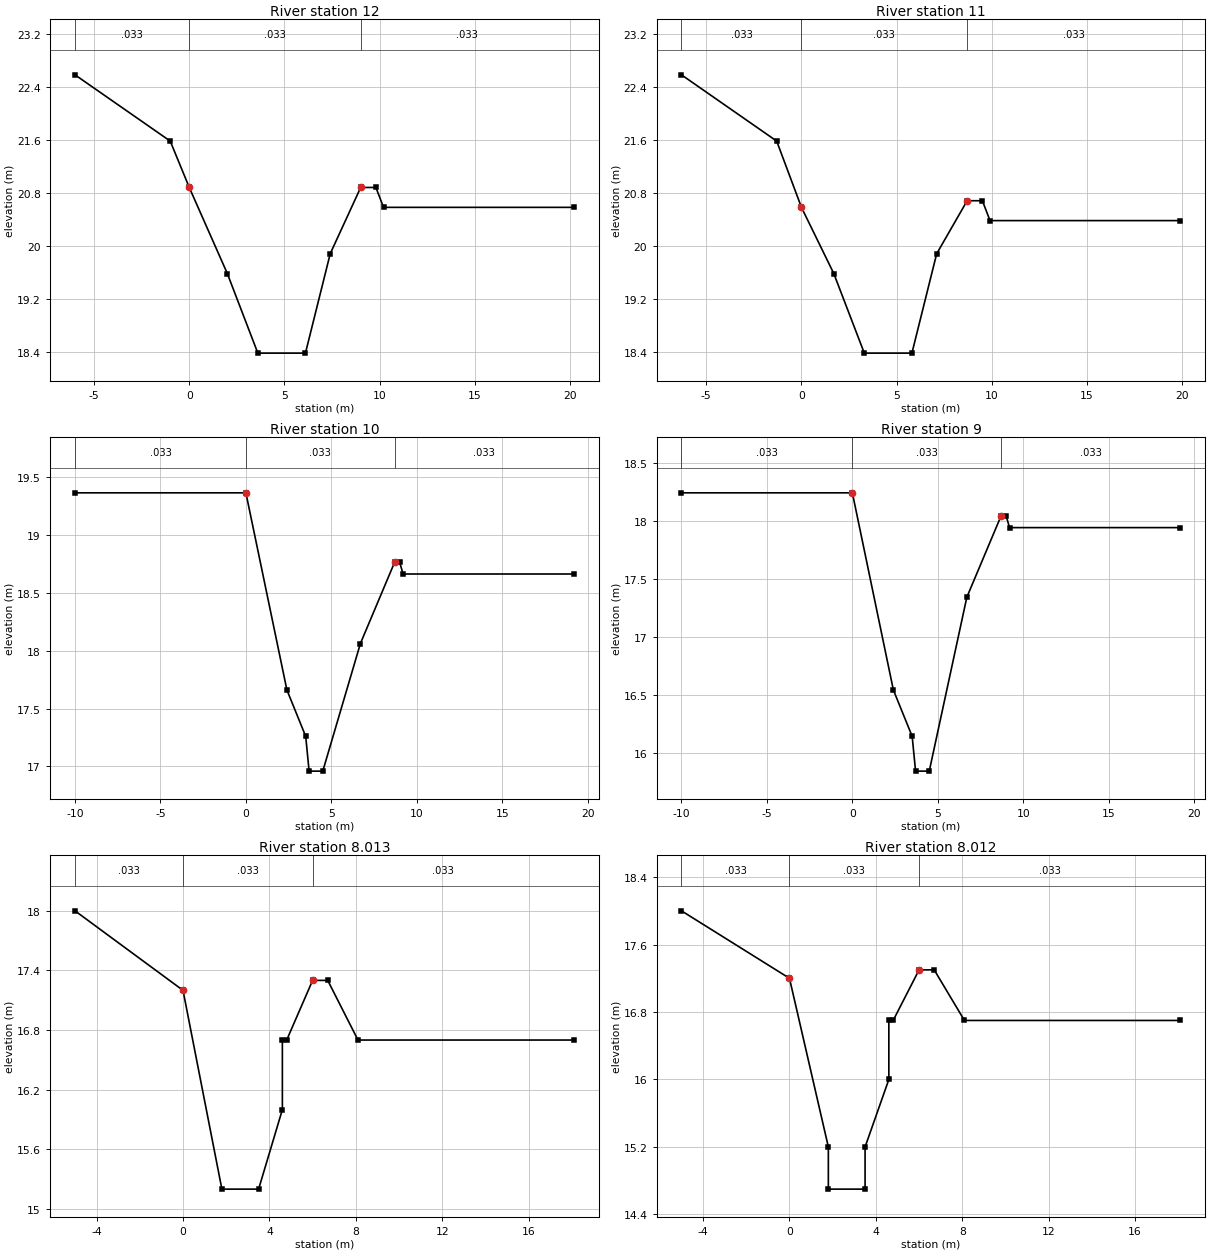
Type RM Length L Ch R = 1 ,12      ,50,50,50
#Sta/Elev= 11
      -6   22.58      -1   21.58       0   20.88       2   19.58     3.6   18.38
     6.1   18.38     7.4   19.88       9   20.88     9.8   20.88    10.2   20.58
    20.2   20.58
#Mann= 3 , 0 , 0
      -6    .033       0       0    .033       0       9    .033       0
Bank Sta=0,9
XS Rating Curve= 0
Exp/Cntr=.3,.1

Type RM Length L Ch R = 1 ,11      ,50,50,50
#Sta/Elev= 11
    -6.3   22.59    -1.3   21.59       0   20.59     1.7   19.59     3.3   18.39
     5.8   18.39     7.1   19.89     8.7   20.69     9.5   20.69     9.9   20.39
    19.9   20.39
#Mann= 3 , 0 , 0
    -6.3    .033       0       0    .033       0     8.7    .033       0
Bank Sta=0,8.7
XS Rating Curve= 0
Exp/Cntr=.3,.1

Type RM Length L Ch R = 1 ,10      ,50,50,50
#Sta/Elev= 11
     -10   19.36       0   19.36     2.4   17.66     3.5   17.26     3.7   16.96
     4.5   16.96     6.7   18.06     8.7   18.76       9   18.76     9.2   18.66
    19.2   18.66
#Mann= 3 , 0 , 0
     -10    .033       0       0    .033       0     8.7    .033       0
Bank Sta=0,8.7
XS Rating Curve= 0
Exp/Cntr=.3,.1

Type RM Length L Ch R = 1 ,9       ,37,37,37
#Sta/Elev= 11
     -10   18.24       0   18.24     2.4   16.54     3.5   16.14     3.7   15.84
     4.5   15.84     6.7   17.34     8.7   18.04       9   18.04     9.2   17.94
    19.2   17.94
#Mann= 3 , 0 , 0
     -10    .033       0       0    .033       0     8.7    .033       0
Bank Sta=0,8.7
XS Rating Curve= 0
Exp/Cntr=.3,.1

Type RM Length L Ch R = 1 ,8.013   ,1,1,1
#Sta/Elev= 11
      -5      18       0    17.2     1.8    15.2     3.5    15.2     4.6      16
     4.6    16.7     4.8    16.7       6    17.3     6.7    17.3     8.1    16.7
    18.1    16.7
#Mann= 3 , 0 , 0
      -5    .033       0       0    .033       0       6    .033       0
Bank Sta=0,6
XS Rating Curve= 0
Exp/Cntr=.3,.1

Type RM Length L Ch R = 1 ,8.012   ,12,12,12
#Sta/Elev= 13
      -5      18       0    17.2     1.8    15.2     1.8    14.7     3.5    14.7
     3.5    15.2     4.6      16     4.6    16.7     4.8    16.7       6    17.3
     6.7    17.3     8.1    16.7    18.1    16.7
#Mann= 3 , 0 , 0
      -5    .033       0       0    .033       0       6    .033       0
Bank Sta=0,6
XS Rating Curve= 0
Exp/Cntr=.3,.1

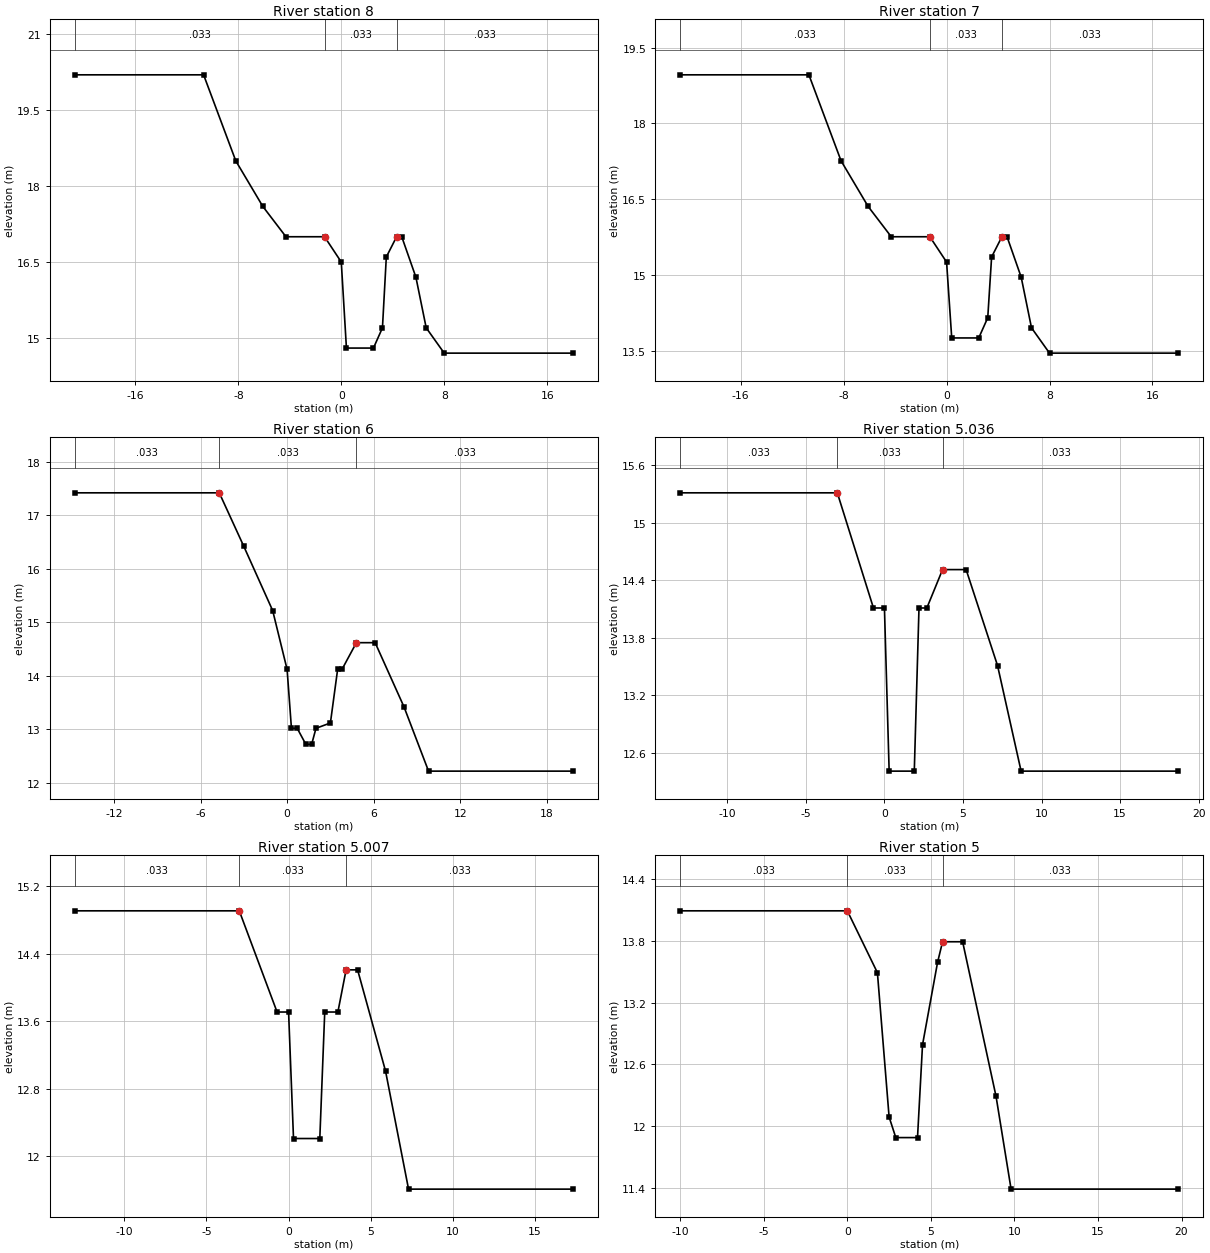
Type RM Length L Ch R = 1 ,8       ,50,50,50
#Sta/Elev= 17
   -20.7    20.2   -10.7    20.2    -8.2    18.5    -6.1    17.6    -4.3      17
    -1.3      17       0    16.5      .4    14.8     2.5    14.8     3.2    15.2
     3.5    16.6     4.3      17     4.7      17     5.8    16.2     6.6    15.2
       8    14.7      18    14.7
#Mann= 3 , 0 , 0
   -20.7    .033       0    -1.3    .033       0     4.3    .033       0
Bank Sta=-1.3,4.3
XS Rating Curve= 0
Exp/Cntr=.3,.1

Type RM Length L Ch R = 1 ,7       ,50,50,50
#Sta/Elev= 17
   -20.7   18.96   -10.7   18.96    -8.2   17.26    -6.1   16.36    -4.3   15.76
    -1.3   15.76       0   15.26      .4   13.76     2.5   13.76     3.2   14.16
     3.5   15.36     4.3   15.76     4.7   15.76     5.8   14.96     6.6   13.96
       8   13.46      18   13.46
#Mann= 3 , 0 , 0
   -20.7    .033       0    -1.3    .033       0     4.3    .033       0
Bank Sta=-1.3,4.3
XS Rating Curve= 0
Exp/Cntr=.3,.1

Type RM Length L Ch R = 1 ,6       ,14,14,14
#Sta/Elev= 18
   -14.7   17.42    -4.7   17.42      -3   16.42      -1   15.22       0   14.12
      .3   13.02      .7   13.02     1.3   12.72     1.7   12.72       2   13.02
       3   13.12     3.5   14.12     3.8   14.12     4.8   14.62     6.1   14.62
     8.1   13.42     9.8   12.22    19.8   12.22
#Mann= 3 , 0 , 0
   -14.7    .033       0    -4.7    .033       0     4.8    .033       0
Bank Sta=-4.7,4.8
XS Rating Curve= 0
Exp/Cntr=.3,.1

Type RM Length L Ch R = 1 ,5.036   ,29,29,29
#Sta/Elev= 13
     -13   15.31      -3   15.31     -.7   14.11       0   14.11      .3   12.41
     1.9   12.41     2.2   14.11     2.7   14.11     3.7   14.51     5.2   14.51
     7.2   13.51     8.7   12.41    18.7   12.41
#Mann= 3 , 0 , 0
     -13    .033       0      -3    .033       0     3.7    .033       0
Bank Sta=-3,3.7
XS Rating Curve= 0
Exp/Cntr=.3,.1

Type RM Length L Ch R = 1 ,5.007   ,7,7,7
#Sta/Elev= 13
     -13   14.91      -3   14.91     -.7   13.71       0   13.71      .3   12.21
     1.9   12.21     2.2   13.71       3   13.71     3.5   14.21     4.2   14.21
     5.9   13.01     7.3   11.61    17.3   11.61
#Mann= 3 , 0 , 0
     -13    .033       0      -3    .033       0     3.5    .033       0
Bank Sta=-3,3.5
XS Rating Curve= 0
Exp/Cntr=.3,.1

Type RM Length L Ch R = 1 ,5       ,8,8,8
#Sta/Elev= 13
     -10   14.09       0   14.09     1.8   13.49     2.5   12.09     2.9   11.89
     4.2   11.89     4.5   12.79     5.4   13.59     5.7   13.79     6.9   13.79
     8.9   12.29     9.8   11.39    19.8   11.39
#Mann= 3 , 0 , 0
     -10    .033       0       0    .033       0     5.7    .033       0
Bank Sta=0,5.7
XS Rating Curve= 0
Exp/Cntr=.3,.1

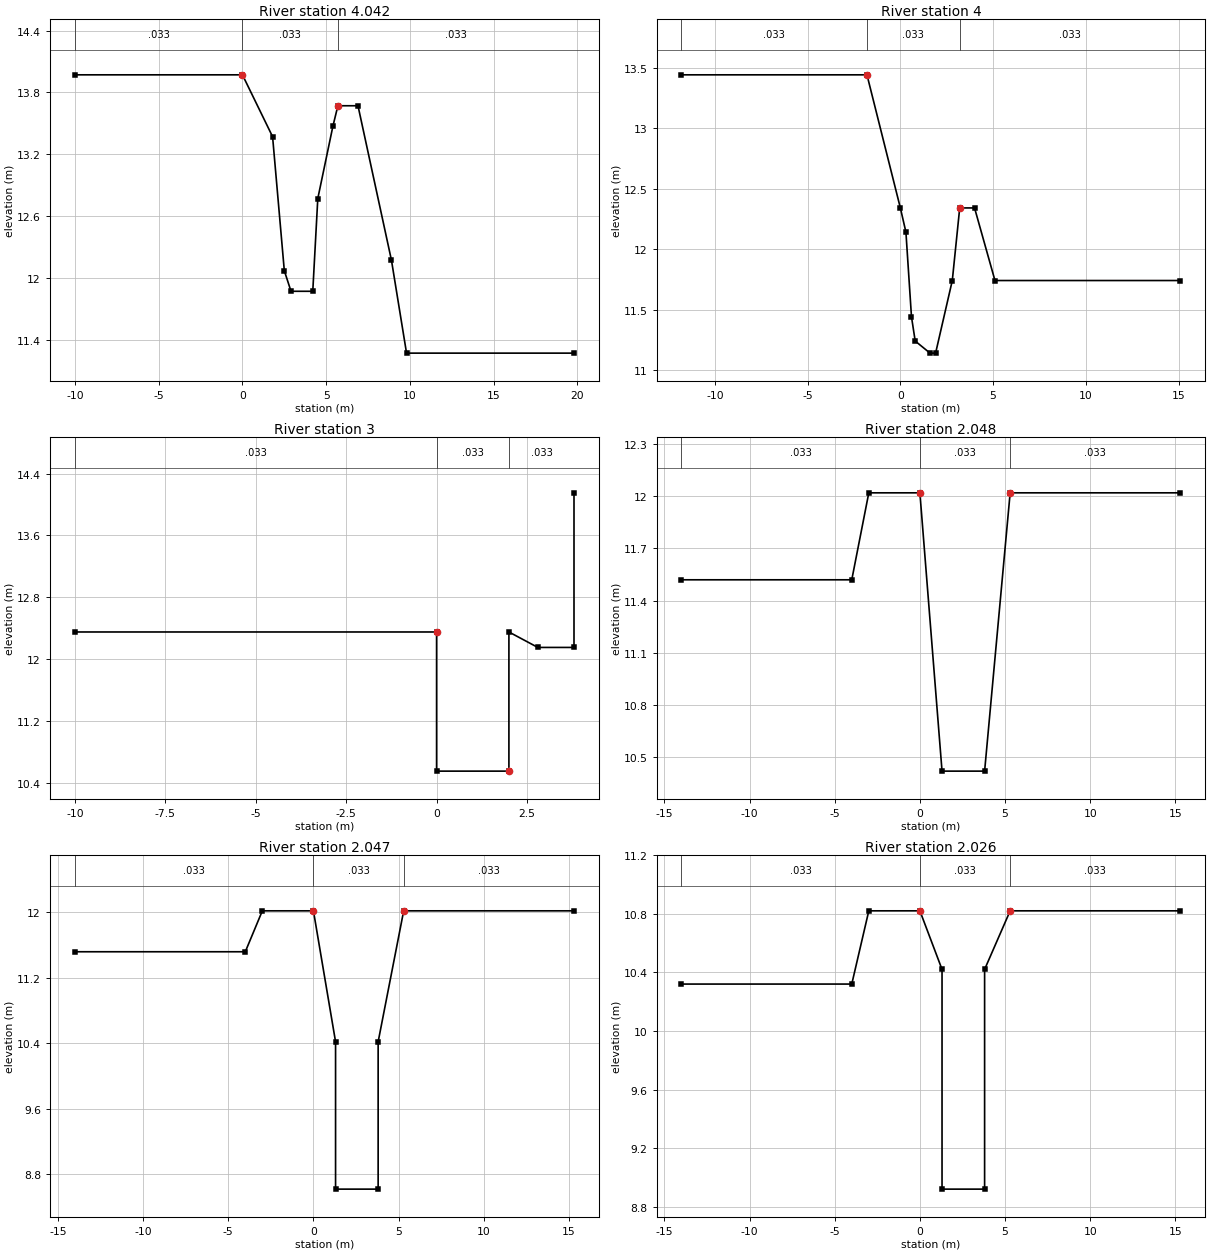
Type RM Length L Ch R = 1 ,4.042   ,42,42,42
#Sta/Elev= 13
     -10   13.97       0   13.97     1.8   13.37     2.5   12.07     2.9   11.87
     4.2   11.87     4.5   12.77     5.4   13.47     5.7   13.67     6.9   13.67
     8.9   12.17     9.8   11.27    19.8   11.27
#Mann= 3 , 0 , 0
     -10    .033       0       0    .033       0     5.7    .033       0
Bank Sta=0,5.7
XS Rating Curve= 0
Exp/Cntr=.3,.1

Type RM Length L Ch R = 1 ,4       ,50,50,50
#Sta/Elev= 13
   -11.8   13.44    -1.8   13.44       0   12.34      .3   12.14      .6   11.44
      .8   11.24     1.6   11.14     1.9   11.14     2.8   11.74     3.2   12.34
       4   12.34     5.1   11.74    15.1   11.74
#Mann= 3 , 0 , 0
   -11.8    .033       0    -1.8    .033       0     3.2    .033       0
Bank Sta=-1.8,3.2
XS Rating Curve= 0
Exp/Cntr=.3,.1

Type RM Length L Ch R = 1 ,3       ,2,2,2
#Sta/Elev= 8
     -10   12.35       0   12.35       0   10.55       2   10.55       2   12.35
     2.8   12.15     3.8   12.15     3.8   14.15
#Mann= 3 , 0 , 0
     -10    .033       0       0    .033       0       2    .033       0
Bank Sta=0,2
XS Rating Curve= 0
Exp/Cntr=.3,.1

Type RM Length L Ch R = 1 ,2.048   ,1,1,1
#Sta/Elev= 8
     -14   11.52      -4   11.52      -3   12.02       0   12.02     1.3   10.42
     3.8   10.42     5.3   12.02    15.3   12.02
#Mann= 3 , 0 , 0
     -14    .033       0       0    .033       0     5.3    .033       0
Bank Sta=0,5.3
XS Rating Curve= 0
Exp/Cntr=.3,.1

Type RM Length L Ch R = 1 ,2.047   ,1,1,1
#Sta/Elev= 10
     -14   11.52      -4   11.52      -3   12.02       0   12.02     1.3   10.42
     1.3    8.62     3.8    8.62     3.8   10.42     5.3   12.02    15.3   12.02
#Mann= 3 , 0 , 0
     -14    .033       0       0    .033       0     5.3    .033       0
Bank Sta=0,5.3
XS Rating Curve= 0
Exp/Cntr=.3,.1

Type RM Length L Ch R = 1 ,2.026   ,26,26,26
#Sta/Elev= 10
     -14   10.32      -4   10.32      -3   10.82       0   10.82     1.3   10.42
     1.3    8.92     3.8    8.92     3.8   10.42     5.3   10.82    15.3   10.82
#Mann= 3 , 0 , 0
     -14    .033       0       0    .033       0     5.3    .033       0
Bank Sta=0,5.3
XS Rating Curve= 0
Exp/Cntr=.3,.1

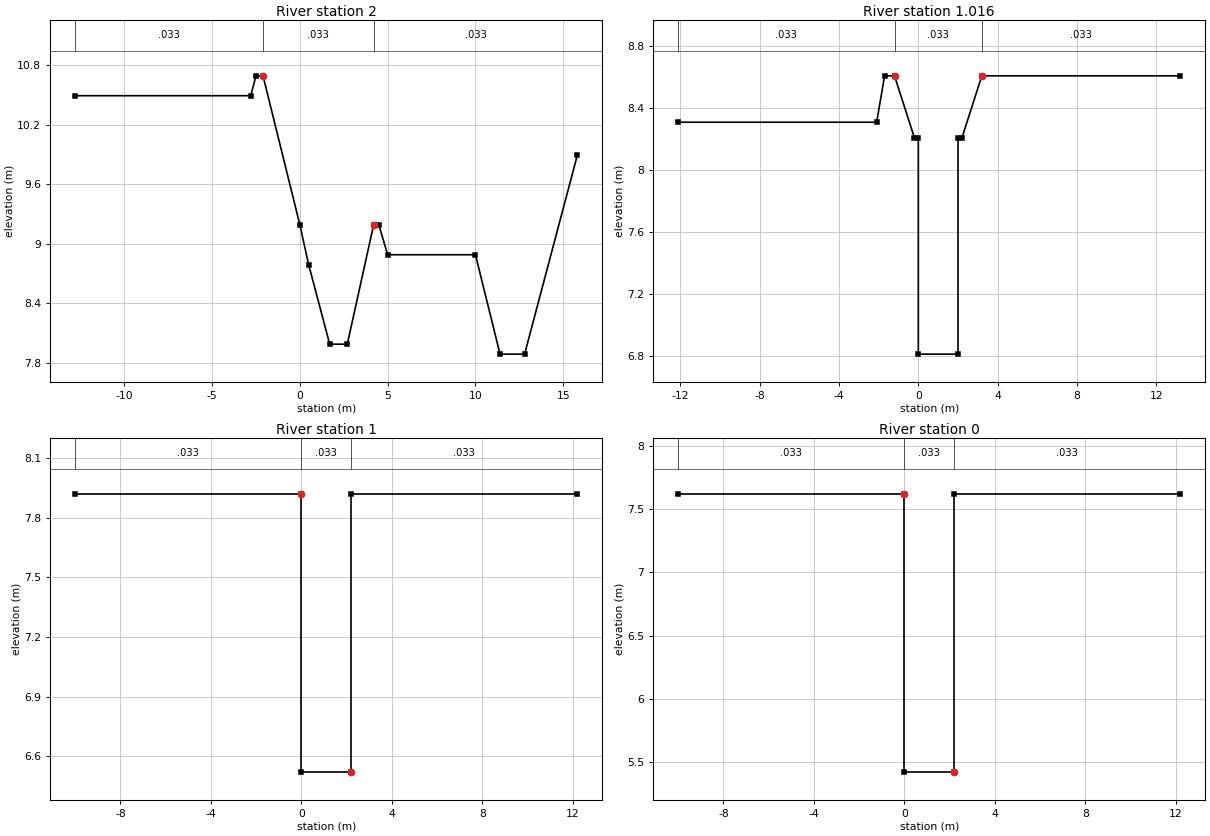
Type RM Length L Ch R = 1 ,2       ,34,34,34
#Sta/Elev= 15
   -12.8   10.49    -2.8   10.49    -2.5   10.69    -2.1   10.69       0    9.19
      .5    8.79     1.7    7.99     2.7    7.99     4.2    9.19     4.5    9.19
       5    8.89      10    8.89    11.4    7.89    12.8    7.89    15.8    9.89
#Mann= 3 , 0 , 0
   -12.8    .033       0    -2.1    .033       0     4.2    .033       0
Bank Sta=-2.1,4.2
XS Rating Curve= 0
Exp/Cntr=.3,.1

Type RM Length L Ch R = 1 ,1.016   ,16,16,16
#Sta/Elev= 12
   -12.1    8.31    -2.1    8.31    -1.7    8.61    -1.2    8.61     -.2    8.21
       0    8.21       0    6.81       2    6.81       2    8.21     2.2    8.21
     3.2    8.61    13.2    8.61
#Mann= 3 , 0 , 0
   -12.1    .033       0    -1.2    .033       0     3.2    .033       0
Bank Sta=-1.2,3.2
XS Rating Curve= 0
Exp/Cntr=.3,.1

Type RM Length L Ch R = 1 ,1       ,50,50,50
#Sta/Elev= 6
     -10    7.92       0    7.92       0    6.52     2.2    6.52     2.2    7.92
    12.2    7.92
#Mann= 3 , 0 , 0
     -10    .033       0       0    .033       0     2.2    .033       0
Bank Sta=0,2.2
XS Rating Curve= 0
Exp/Cntr=.3,.1

Type RM Length L Ch R = 1 ,0       ,0,0,0
#Sta/Elev= 6
     -10    7.62       0    7.62       0    5.42     2.2    5.42     2.2    7.62
    12.2    7.62
#Mann= 3 , 0 , 0
     -10    .033       0       0    .033       0     2.2    .033       0
Bank Sta=0,2.2
XS Rating Curve= 0
Exp/Cntr=.3,.1

Chan Stop Cuts=-1