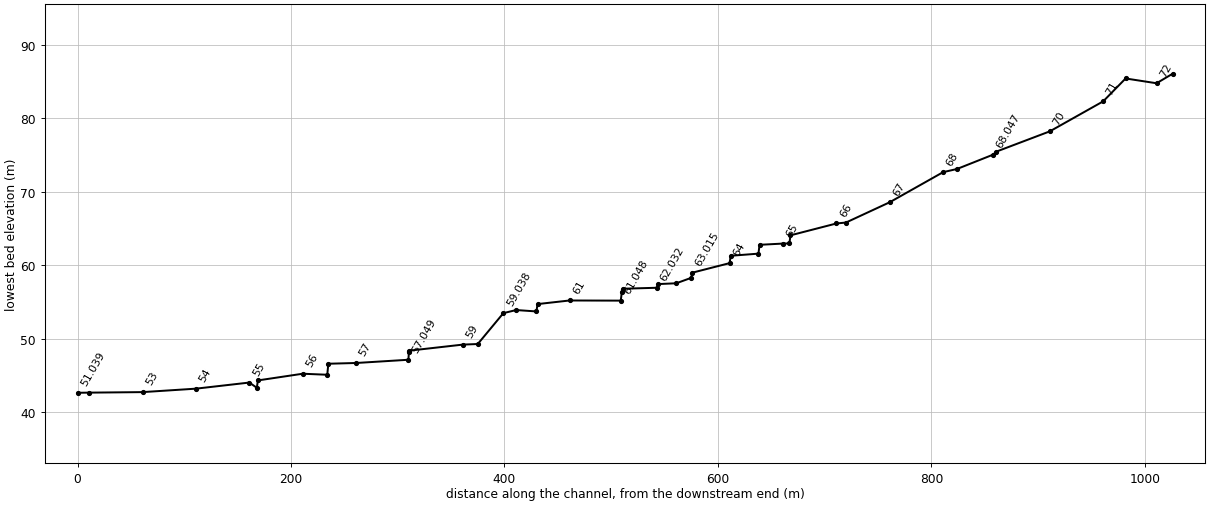
--- DONGSIL.prj (project) ---

Proj Title=DONGSIL
Current Plan=p01
Default Exp/Contr=.3,.1
SI Units
Geom File=g01
Flow File=f01
Plan File=p01
Y Axis Title=Elevation
X Axis Title(PF)=Main Channel Distance
X Axis Title(XS)=Station
BEGIN DESCRIPTION:
           BACK WATER COMPUTATION
      APPLICATION OF HEC-2 BY Samju Construction Engineering
      DONGSIL-STREEM : 30 YR
END DESCRIPTION:
DSS Export Rating Curves= 0
DSS Export Rating Curve Sorted= 0
DSS Export Volume Flow Curves= 0
DXF OffsetX= 0
DXF OffsetY= 0
DXF ScaleX= 1
DXF ScaleY= 10

--- DONGSIL.p01 (plan) ---

Plan Title=Imported Plan 01
Version=Version 3.0.1  Mar 2001
Short Identifier=Imported Pla
Geom File=g01
Flow File=f01
Subcritical Flow
K Sum by GR= 0
Std Step Tol= 0.003
Critical Tol= 0.003
Num of Std Step Trials= 20
Max Error Tol= 0.1
Flow Tol Ratio= 0.001
Split Flow NTrial= 30
Split Flow Tol= 0.02
Split Flow Ratio= 0.02
Log Output Level= 0
Friction Slope Method= 1
Unsteady Friction Slope Method= 2
Parabolic Critical Depth
Global Vel Dist= 0 , 0 , 0
Global Log Level= 0
CheckData=True
Encroach Param=-1 ,0,0, 0
Computation Interval=1HOUR
Output Interval=1HOUR
Run HTab= 0
Run UNet= 0
Run PostProcess= 0
UNET Theta= 1
UNET ZTol= 0.02
UNET ZSATol= 0.1
UNET MxIter= 20
UNET MaxInSteps= 20
UNET DtIC= 0
UNET DtMin= 0
UNET MaxCRTS= 20
UNET WFStab= 2
UNET SFStab= 1
UNET WFX= 1
UNET SFX= 1
UNET Convert EG Bridges=-1
UNET Use Existing IB Tables=-1
Instantaneous Interval=1HOUR
Write IC File= 0
Write Velocity= 0
Write Detailed= 0

--- DONGSIL.f01 (steady flow) ---

Flow Title=Imported Flow 01
Version=Version 3.0.1  Mar 2001
Number of Profiles= 1
Profile Names=PF 1
River Rch & RM=RIVER-1,Reach-1         ,72.015
      75
Boundary for River Rch & Prof#=RIVER-1,Reach-1         , 1
Up Type= 0
Dn Type= 3
Dn Slope=.0109
DSS Import GetInterval= 0
DSS Import GetPeak= 0
DSS Import FillOption= 0

--- DONGSIL.g01 (geometry) ---

Geom Title=Imported Geom 01
Version=Version 3.0.1  Mar 2001

River Reach=RIVER-1         ,Reach-1
Reach XY= 2
              .5             .95              .5             .05

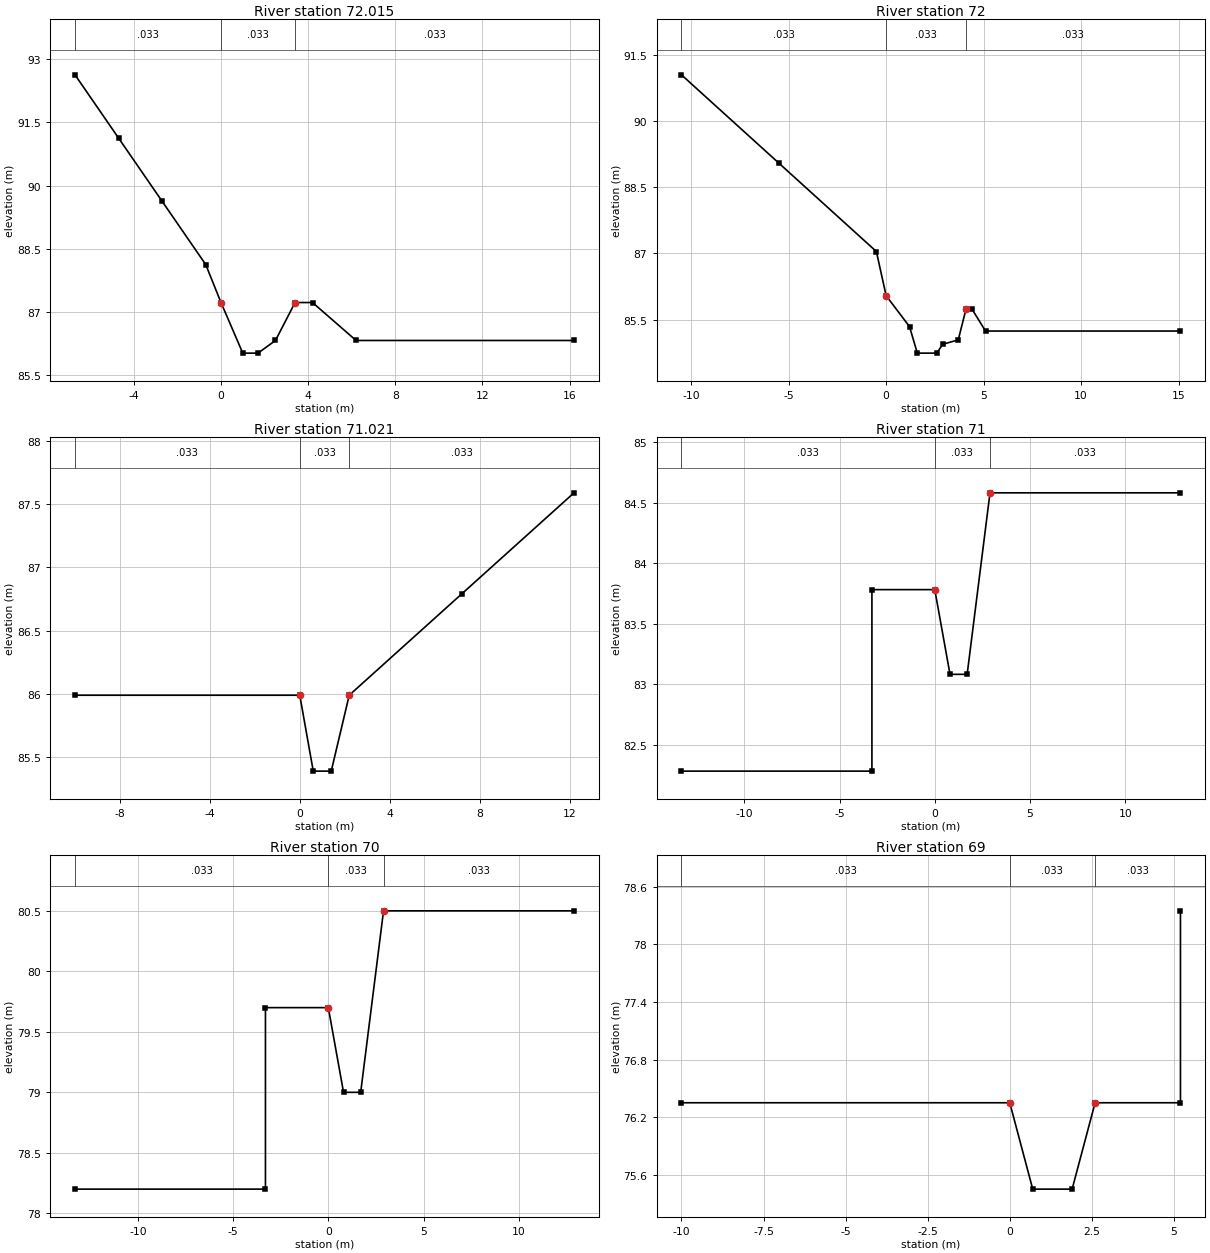
Type RM Length L Ch R = 1 ,72.015  ,15,15,15
#Sta/Elev= 12
    -6.7   92.63    -4.7   91.13    -2.7   89.63     -.7   88.13       0   87.23
       1   86.03     1.7   86.03     2.5   86.33     3.4   87.23     4.2   87.23
     6.2   86.33    16.2   86.33
#Mann= 3 , 0 , 0
    -6.7    .033       0       0    .033       0     3.4    .033       0
Bank Sta=0,3.4
XS Rating Curve= 0
Exp/Cntr=.3,.1

Type RM Length L Ch R = 1 ,72      ,29,29,29
#Sta/Elev= 13
   -10.5   91.04    -5.5   89.04     -.5   87.04       0   86.04     1.2   85.34
     1.6   84.74     2.6   84.74     2.9   84.94     3.7   85.04     4.1   85.74
     4.4   85.74     5.1   85.24    15.1   85.24
#Mann= 3 , 0 , 0
   -10.5    .033       0       0    .033       0     4.1    .033       0
Bank Sta=0,4.1
XS Rating Curve= 0
Exp/Cntr=.3,.1

Type RM Length L Ch R = 1 ,71.021  ,21,21,21
#Sta/Elev= 7
     -10   85.99       0   85.99      .6   85.39     1.4   85.39     2.2   85.99
     7.2   86.79    12.2   87.59
#Mann= 3 , 0 , 0
     -10    .033       0       0    .033       0     2.2    .033       0
Bank Sta=0,2.2
XS Rating Curve= 0
Exp/Cntr=.3,.1

Type RM Length L Ch R = 1 ,71      ,50,50,50
#Sta/Elev= 8
   -13.3   82.28    -3.3   82.28    -3.3   83.78       0   83.78      .8   83.08
     1.7   83.08     2.9   84.58    12.9   84.58
#Mann= 3 , 0 , 0
   -13.3    .033       0       0    .033       0     2.9    .033       0
Bank Sta=0,2.9
XS Rating Curve= 0
Exp/Cntr=.3,.1

Type RM Length L Ch R = 1 ,70      ,50,50,50
#Sta/Elev= 8
   -13.3    78.2    -3.3    78.2    -3.3    79.7       0    79.7      .8      79
     1.7      79     2.9    80.5    12.9    80.5
#Mann= 3 , 0 , 0
   -13.3    .033       0       0    .033       0     2.9    .033       0
Bank Sta=0,2.9
XS Rating Curve= 0
Exp/Cntr=.3,.1

Type RM Length L Ch R = 1 ,69      ,3,3,3
#Sta/Elev= 7
     -10   76.35       0   76.35      .7   75.45     1.9   75.45     2.6   76.35
     5.2   76.35     5.2   78.35
#Mann= 3 , 0 , 0
     -10    .033       0       0    .033       0     2.6    .033       0
Bank Sta=0,2.6
XS Rating Curve= 0
Exp/Cntr=.3,.1

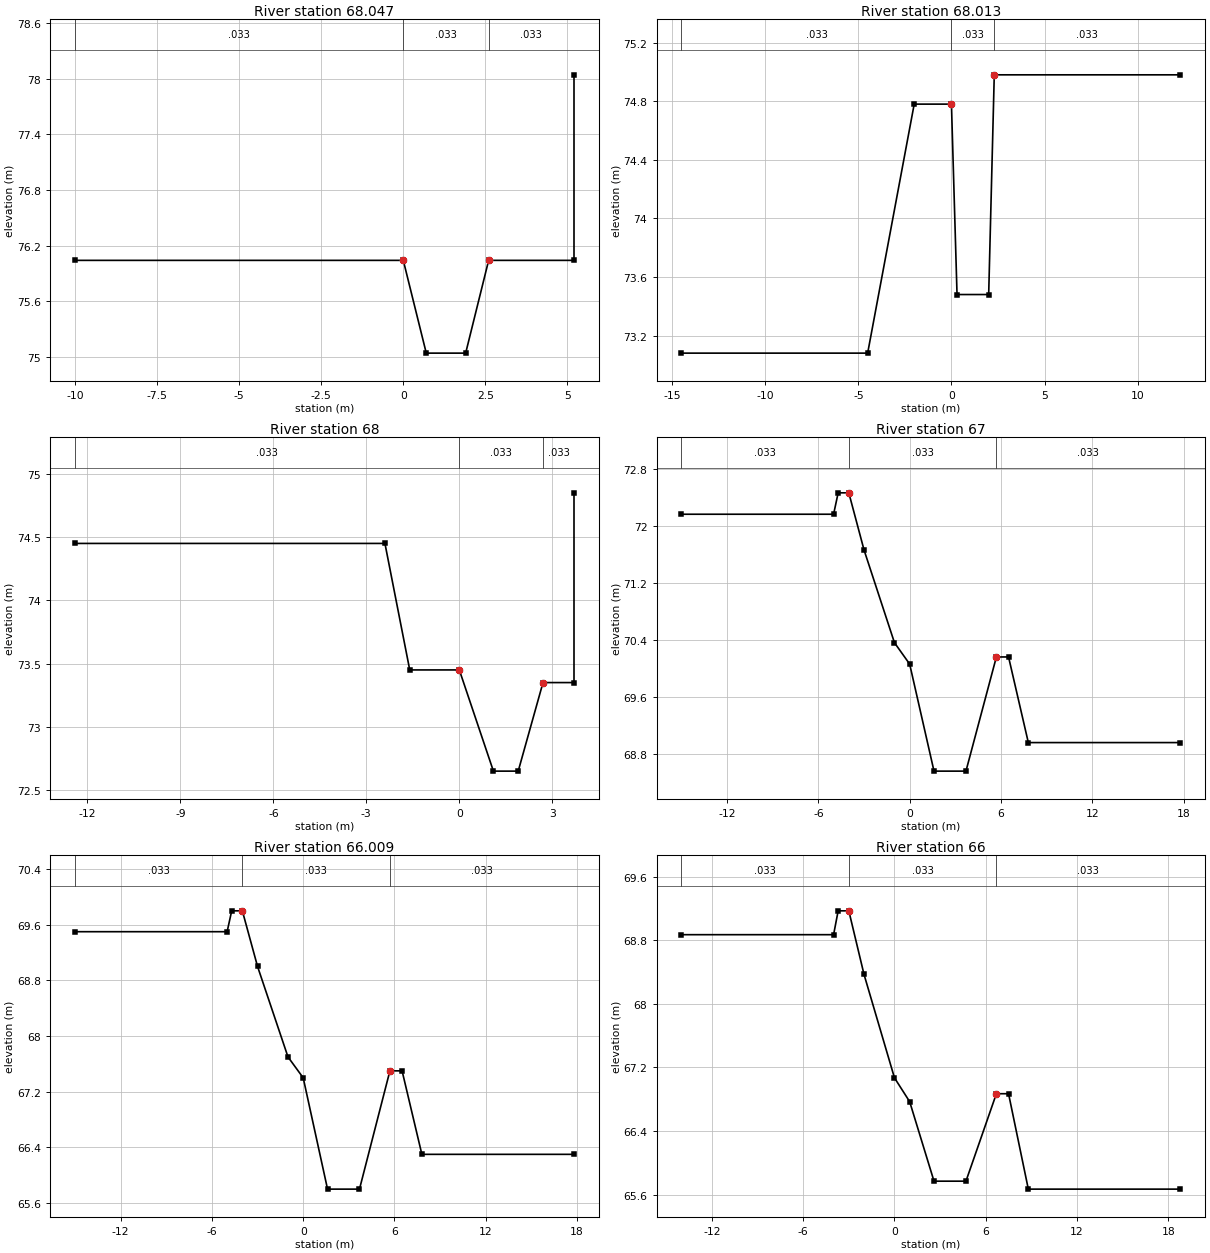
Type RM Length L Ch R = 1 ,68.047  ,34,34,34
#Sta/Elev= 7
     -10   76.04       0   76.04      .7   75.04     1.9   75.04     2.6   76.04
     5.2   76.04     5.2   78.04
#Mann= 3 , 0 , 0
     -10    .033       0       0    .033       0     2.6    .033       0
Bank Sta=0,2.6
XS Rating Curve= 0
Exp/Cntr=.3,.1

Type RM Length L Ch R = 1 ,68.013  ,13,13,13
#Sta/Elev= 8
   -14.5   73.08    -4.5   73.08      -2   74.78       0   74.78      .3   73.48
       2   73.48     2.3   74.98    12.3   74.98
#Mann= 3 , 0 , 0
   -14.5    .033       0       0    .033       0     2.3    .033       0
Bank Sta=0,2.3
XS Rating Curve= 0
Exp/Cntr=.3,.1

Type RM Length L Ch R = 1 ,68      ,50,50,50
#Sta/Elev= 9
   -12.4   74.45    -2.4   74.45    -1.6   73.45       0   73.45     1.1   72.65
     1.9   72.65     2.7   73.35     3.7   73.35     3.7   74.85
#Mann= 3 , 0 , 0
   -12.4    .033       0       0    .033       0     2.7    .033       0
Bank Sta=0,2.7
XS Rating Curve= 0
Exp/Cntr=.3,.1

Type RM Length L Ch R = 1 ,67      ,41,41,41
#Sta/Elev= 13
     -15   72.16      -5   72.16    -4.7   72.46      -4   72.46      -3   71.66
      -1   70.36       0   70.06     1.6   68.56     3.7   68.56     5.7   70.16
     6.5   70.16     7.8   68.96    17.8   68.96
#Mann= 3 , 0 , 0
     -15    .033       0      -4    .033       0     5.7    .033       0
Bank Sta=-4,5.7
XS Rating Curve= 0
Exp/Cntr=.3,.1

Type RM Length L Ch R = 1 ,66.009  ,9,9,9
#Sta/Elev= 13
     -15    69.5      -5    69.5    -4.7    69.8      -4    69.8      -3      69
      -1    67.7       0    67.4     1.6    65.8     3.7    65.8     5.7    67.5
     6.5    67.5     7.8    66.3    17.8    66.3
#Mann= 3 , 0 , 0
     -15    .033       0      -4    .033       0     5.7    .033       0
Bank Sta=-4,5.7
XS Rating Curve= 0
Exp/Cntr=.3,.1

Type RM Length L Ch R = 1 ,66      ,43,43,43
#Sta/Elev= 13
     -14   68.87      -4   68.87    -3.7   69.17      -3   69.17      -2   68.37
       0   67.07       1   66.77     2.6   65.77     4.7   65.77     6.7   66.87
     7.5   66.87     8.8   65.67    18.8   65.67
#Mann= 3 , 0 , 0
     -14    .033       0      -3    .033       0     6.7    .033       0
Bank Sta=-3,6.7
XS Rating Curve= 0
Exp/Cntr=.3,.1

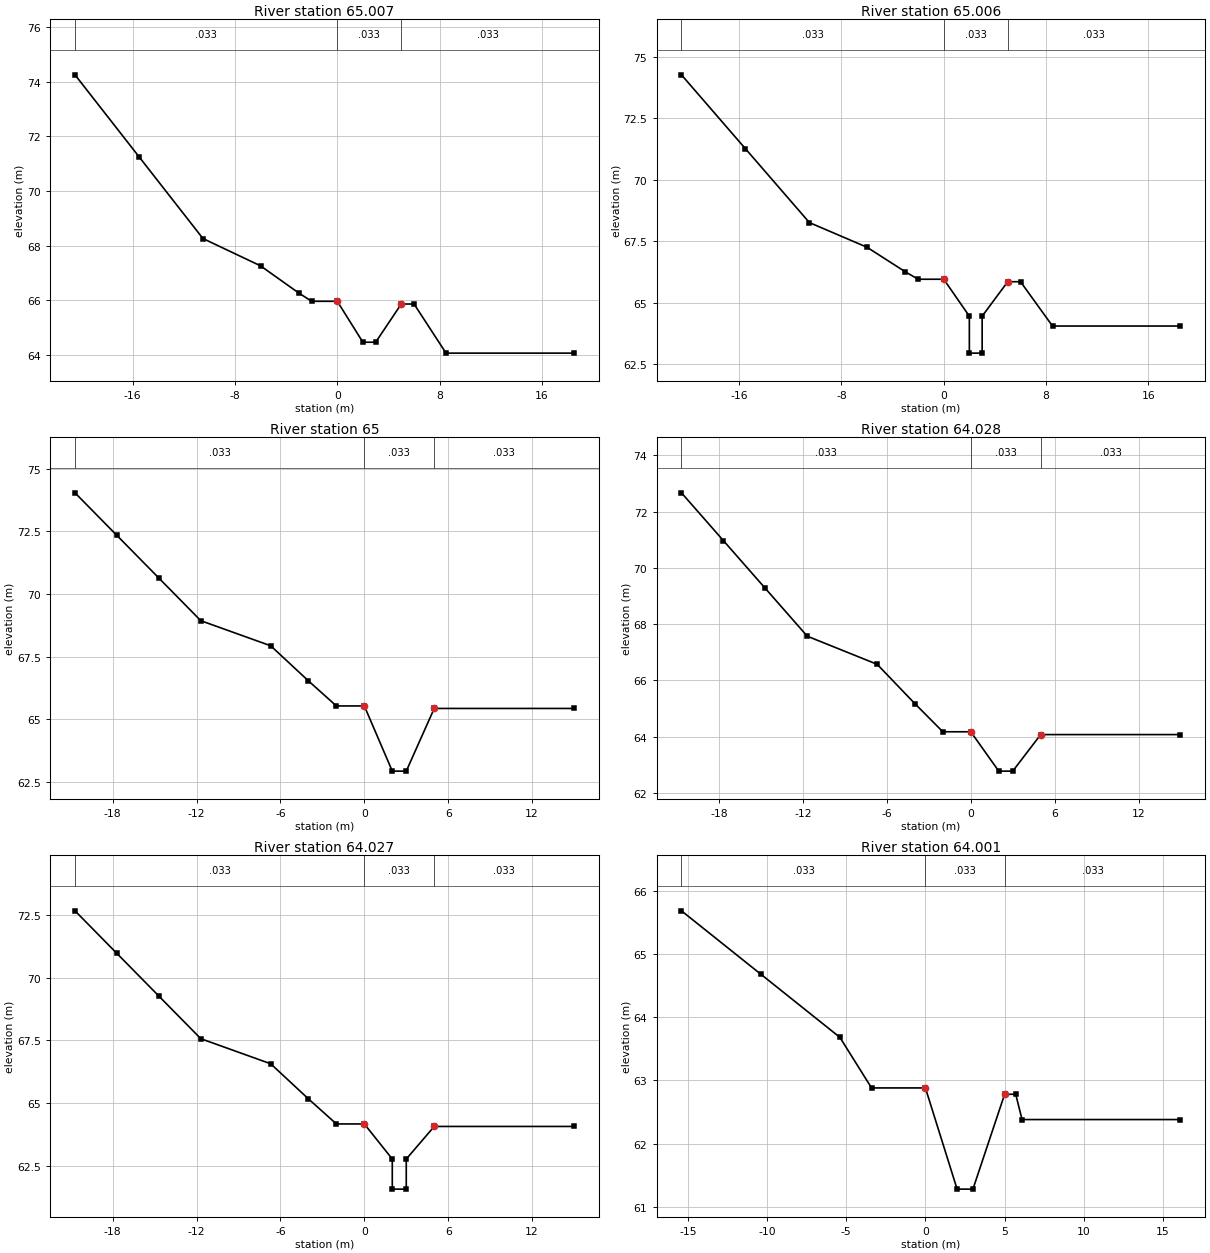
Type RM Length L Ch R = 1 ,65.007  ,1,1,1
#Sta/Elev= 13
   -20.5   74.26   -15.5   71.26   -10.5   68.26      -6   67.26      -3   66.26
      -2   65.96       0   65.96       2   64.46       3   64.46       5   65.86
       6   65.86     8.5   64.06    18.5   64.06
#Mann= 3 , 0 , 0
   -20.5    .033       0       0    .033       0       5    .033       0
Bank Sta=0,5
XS Rating Curve= 0
Exp/Cntr=.3,.1

Type RM Length L Ch R = 1 ,65.006  ,6,6,6
#Sta/Elev= 15
   -20.5   74.26   -15.5   71.26   -10.5   68.26      -6   67.26      -3   66.26
      -2   65.96       0   65.96       2   64.46       2   62.96       3   62.96
       3   64.46       5   65.86       6   65.86     8.5   64.06    18.5   64.06
#Mann= 3 , 0 , 0
   -20.5    .033       0       0    .033       0       5    .033       0
Bank Sta=0,5
XS Rating Curve= 0
Exp/Cntr=.3,.1

Type RM Length L Ch R = 1 ,65      ,22,22,22
#Sta/Elev= 12
   -20.7   74.04   -17.7   72.34   -14.7   70.64   -11.7   68.94    -6.7   67.94
      -4   66.54      -2   65.54       0   65.54       2   62.94       3   62.94
       5   65.44      15   65.44
#Mann= 3 , 0 , 0
   -20.7    .033       0       0    .033       0       5    .033       0
Bank Sta=0,5
XS Rating Curve= 0
Exp/Cntr=.3,.1

Type RM Length L Ch R = 1 ,64.028  ,1,1,1
#Sta/Elev= 12
   -20.7   72.67   -17.7   70.97   -14.7   69.27   -11.7   67.57    -6.7   66.57
      -4   65.17      -2   64.17       0   64.17       2   62.77       3   62.77
       5   64.07      15   64.07
#Mann= 3 , 0 , 0
   -20.7    .033       0       0    .033       0       5    .033       0
Bank Sta=0,5
XS Rating Curve= 0
Exp/Cntr=.3,.1

Type RM Length L Ch R = 1 ,64.027  ,26,26,26
#Sta/Elev= 14
   -20.7   72.67   -17.7   70.97   -14.7   69.27   -11.7   67.57    -6.7   66.57
      -4   65.17      -2   64.17       0   64.17       2   62.77       2   61.57
       3   61.57       3   62.77       5   64.07      15   64.07
#Mann= 3 , 0 , 0
   -20.7    .033       0       0    .033       0       5    .033       0
Bank Sta=0,5
XS Rating Curve= 0
Exp/Cntr=.3,.1

Type RM Length L Ch R = 1 ,64.001  ,1,1,1
#Sta/Elev= 11
   -15.4   65.68   -10.4   64.68    -5.4   63.68    -3.4   62.88       0   62.88
       2   61.28       3   61.28       5   62.78     5.7   62.78     6.1   62.38
    16.1   62.38
#Mann= 3 , 0 , 0
   -15.4    .033       0       0    .033       0       5    .033       0
Bank Sta=0,5
XS Rating Curve= 0
Exp/Cntr=.3,.1

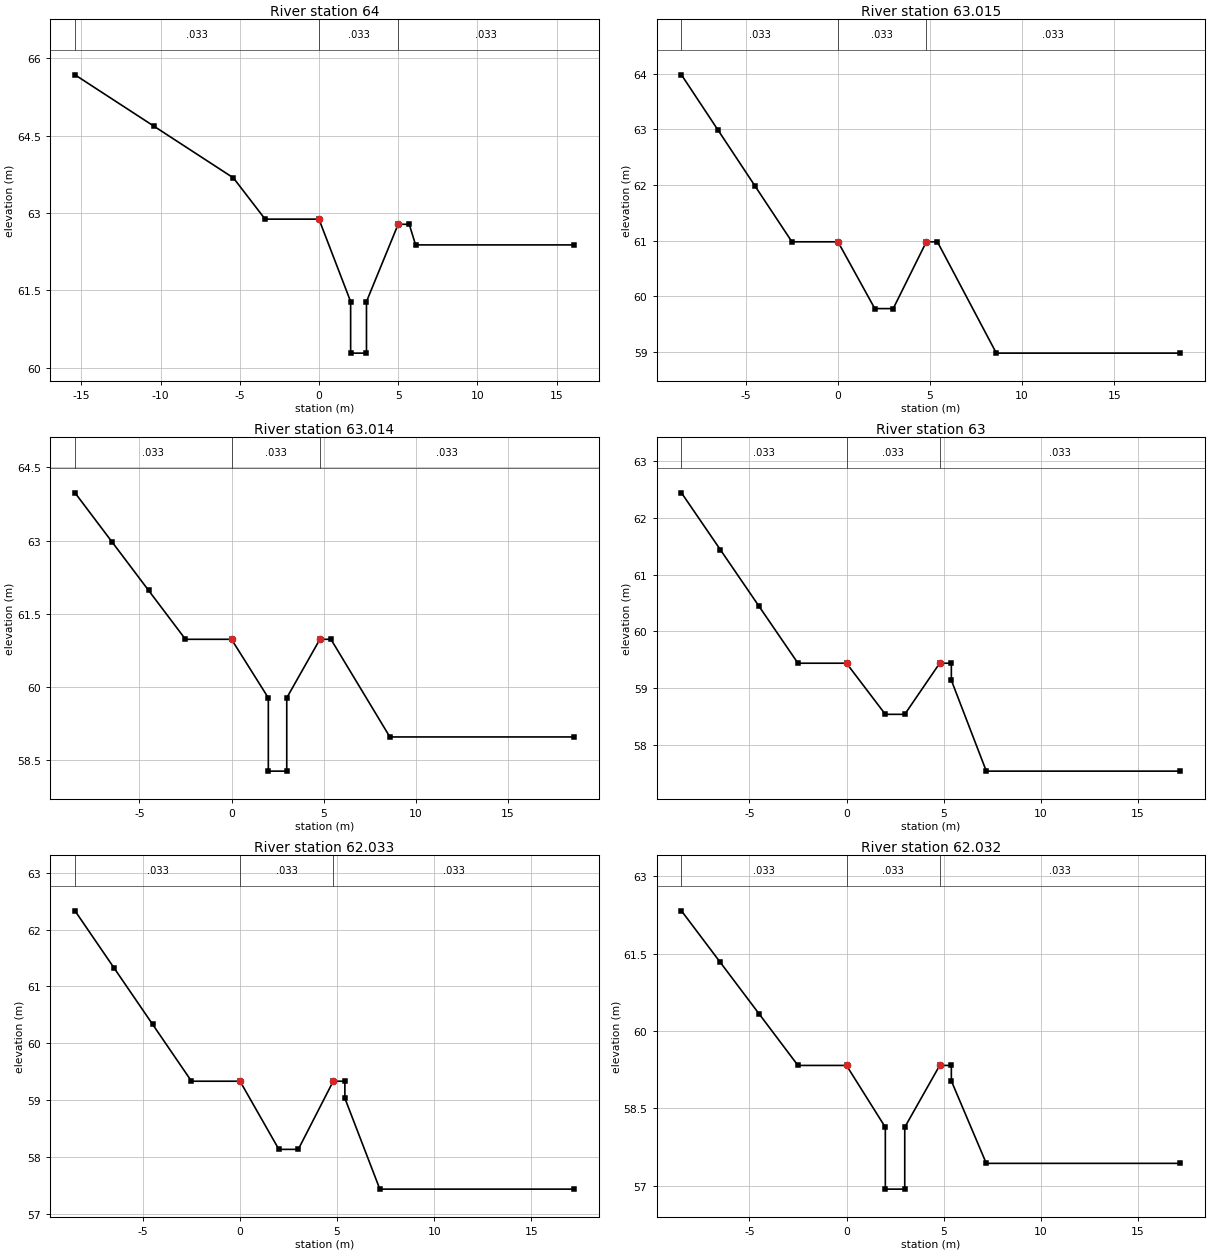
Type RM Length L Ch R = 1 ,64      ,35,35,35
#Sta/Elev= 13
   -15.4   65.68   -10.4   64.68    -5.4   63.68    -3.4   62.88       0   62.88
       2   61.28       2   60.28       3   60.28       3   61.28       5   62.78
     5.7   62.78     6.1   62.38    16.1   62.38
#Mann= 3 , 0 , 0
   -15.4    .033       0       0    .033       0       5    .033       0
Bank Sta=0,5
XS Rating Curve= 0
Exp/Cntr=.3,.1

Type RM Length L Ch R = 1 ,63.015  ,1,1,1
#Sta/Elev= 11
    -8.5   63.98    -6.5   62.98    -4.5   61.98    -2.5   60.98       0   60.98
       2   59.78       3   59.78     4.8   60.98     5.4   60.98     8.6   58.98
    18.6   58.98
#Mann= 3 , 0 , 0
    -8.5    .033       0       0    .033       0     4.8    .033       0
Bank Sta=0,4.8
XS Rating Curve= 0
Exp/Cntr=.3,.1

Type RM Length L Ch R = 1 ,63.014  ,14,14,14
#Sta/Elev= 13
    -8.5   63.98    -6.5   62.98    -4.5   61.98    -2.5   60.98       0   60.98
       2   59.78       2   58.28       3   58.28       3   59.78     4.8   60.98
     5.4   60.98     8.6   58.98    18.6   58.98
#Mann= 3 , 0 , 0
    -8.5    .033       0       0    .033       0     4.8    .033       0
Bank Sta=0,4.8
XS Rating Curve= 0
Exp/Cntr=.3,.1

Type RM Length L Ch R = 1 ,63      ,17,17,17
#Sta/Elev= 12
    -8.5   62.44    -6.5   61.44    -4.5   60.44    -2.5   59.44       0   59.44
       2   58.54       3   58.54     4.8   59.44     5.4   59.44     5.4   59.14
     7.2   57.54    17.2   57.54
#Mann= 3 , 0 , 0
    -8.5    .033       0       0    .033       0     4.8    .033       0
Bank Sta=0,4.8
XS Rating Curve= 0
Exp/Cntr=.3,.1

Type RM Length L Ch R = 1 ,62.033  ,1,1,1
#Sta/Elev= 12
    -8.5   62.33    -6.5   61.33    -4.5   60.33    -2.5   59.33       0   59.33
       2   58.13       3   58.13     4.8   59.33     5.4   59.33     5.4   59.03
     7.2   57.43    17.2   57.43
#Mann= 3 , 0 , 0
    -8.5    .033       0       0    .033       0     4.8    .033       0
Bank Sta=0,4.8
XS Rating Curve= 0
Exp/Cntr=.3,.1

Type RM Length L Ch R = 1 ,62.032  ,32,32,32
#Sta/Elev= 14
    -8.5   62.33    -6.5   61.33    -4.5   60.33    -2.5   59.33       0   59.33
       2   58.13       2   56.93       3   56.93       3   58.13     4.8   59.33
     5.4   59.33     5.4   59.03     7.2   57.43    17.2   57.43
#Mann= 3 , 0 , 0
    -8.5    .033       0       0    .033       0     4.8    .033       0
Bank Sta=0,4.8
XS Rating Curve= 0
Exp/Cntr=.3,.1

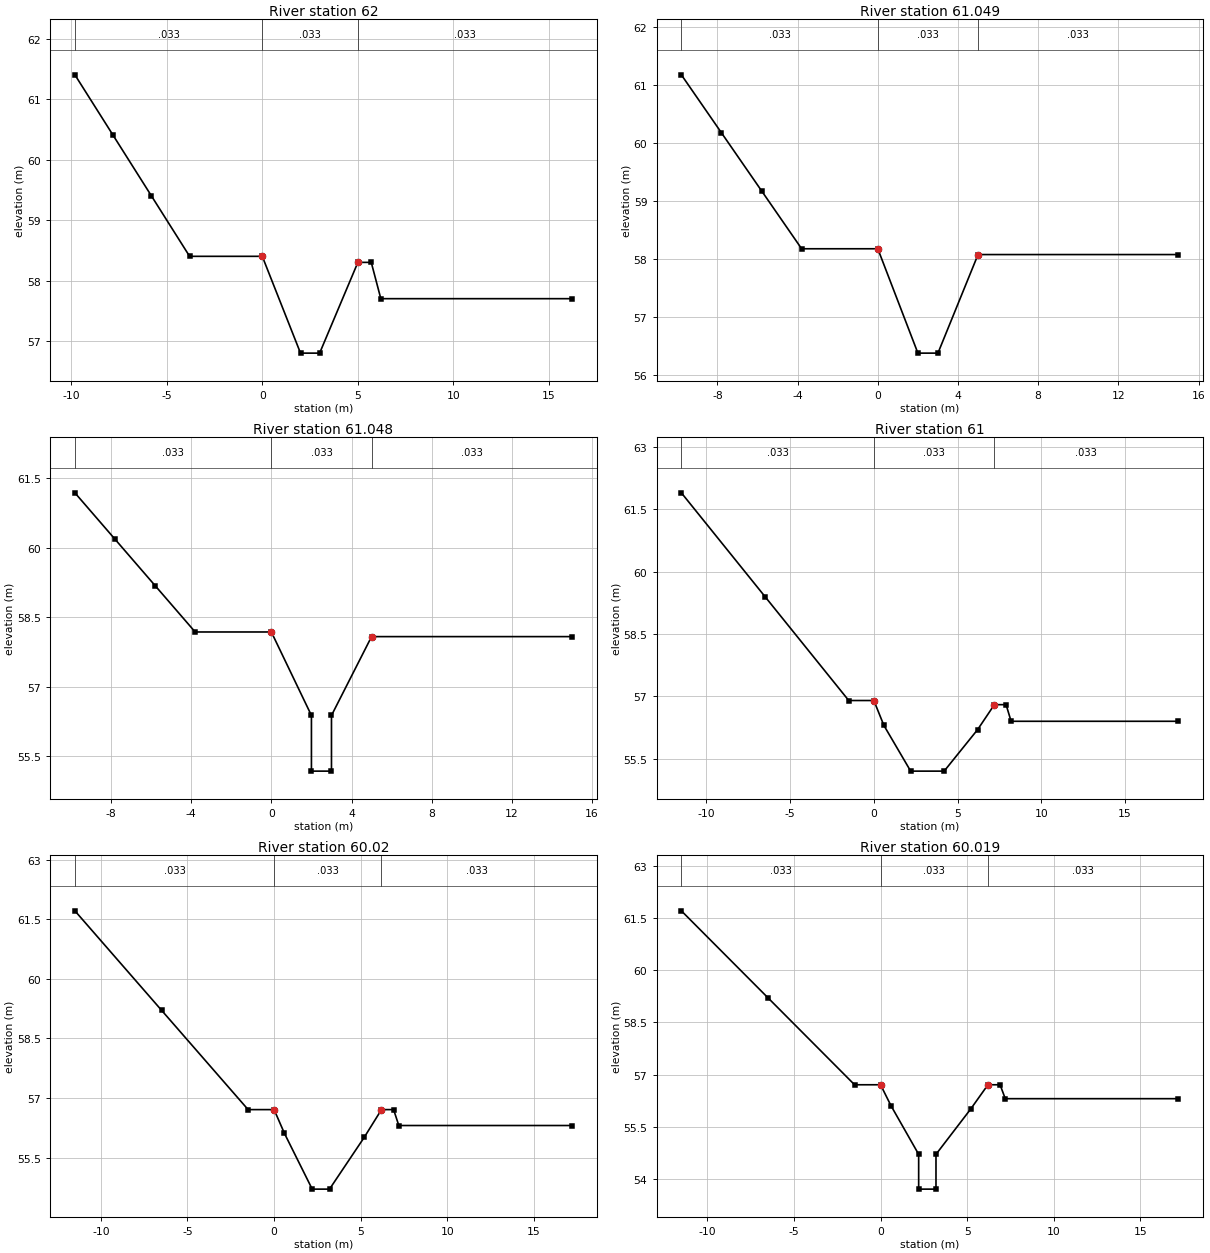
Type RM Length L Ch R = 1 ,62      ,1,1,1
#Sta/Elev= 11
    -9.8    61.4    -7.8    60.4    -5.8    59.4    -3.8    58.4       0    58.4
       2    56.8       3    56.8       5    58.3     5.7    58.3     6.2    57.7
    16.2    57.7
#Mann= 3 , 0 , 0
    -9.8    .033       0       0    .033       0       5    .033       0
Bank Sta=0,5
XS Rating Curve= 0
Exp/Cntr=.3,.1

Type RM Length L Ch R = 1 ,61.049  ,1,1,1
#Sta/Elev= 9
    -9.8   61.18    -7.8   60.18    -5.8   59.18    -3.8   58.18       0   58.18
       2   56.38       3   56.38       5   58.08      15   58.08
#Mann= 3 , 0 , 0
    -9.8    .033       0       0    .033       0       5    .033       0
Bank Sta=0,5
XS Rating Curve= 0
Exp/Cntr=.3,.1

Type RM Length L Ch R = 1 ,61.048  ,48,48,48
#Sta/Elev= 11
    -9.8   61.18    -7.8   60.18    -5.8   59.18    -3.8   58.18       0   58.18
       2   56.38       2   55.18       3   55.18       3   56.38       5   58.08
      15   58.08
#Mann= 3 , 0 , 0
    -9.8    .033       0       0    .033       0       5    .033       0
Bank Sta=0,5
XS Rating Curve= 0
Exp/Cntr=.3,.1

Type RM Length L Ch R = 1 ,61      ,30,30,30
#Sta/Elev= 12
   -11.5    61.9    -6.5    59.4    -1.5    56.9       0    56.9      .6    56.3
     2.2    55.2     4.2    55.2     6.2    56.2     7.2    56.8     7.9    56.8
     8.2    56.4    18.2    56.4
#Mann= 3 , 0 , 0
   -11.5    .033       0       0    .033       0     7.2    .033       0
Bank Sta=0,7.2
XS Rating Curve= 0
Exp/Cntr=.3,.1

Type RM Length L Ch R = 1 ,60.02   ,1,1,1
#Sta/Elev= 12
   -11.5   61.71    -6.5   59.21    -1.5   56.71       0   56.71      .6   56.11
     2.2   54.71     3.2   54.71     5.2   56.01     6.2   56.71     6.9   56.71
     7.2   56.31    17.2   56.31
#Mann= 3 , 0 , 0
   -11.5    .033       0       0    .033       0     6.2    .033       0
Bank Sta=0,6.2
XS Rating Curve= 0
Exp/Cntr=.3,.1

Type RM Length L Ch R = 1 ,60.019  ,19,19,19
#Sta/Elev= 14
   -11.5   61.71    -6.5   59.21    -1.5   56.71       0   56.71      .6   56.11
     2.2   54.71     2.2   53.71     3.2   53.71     3.2   54.71     5.2   56.01
     6.2   56.71     6.9   56.71     7.2   56.31    17.2   56.31
#Mann= 3 , 0 , 0
   -11.5    .033       0       0    .033       0     6.2    .033       0
Bank Sta=0,6.2
XS Rating Curve= 0
Exp/Cntr=.3,.1

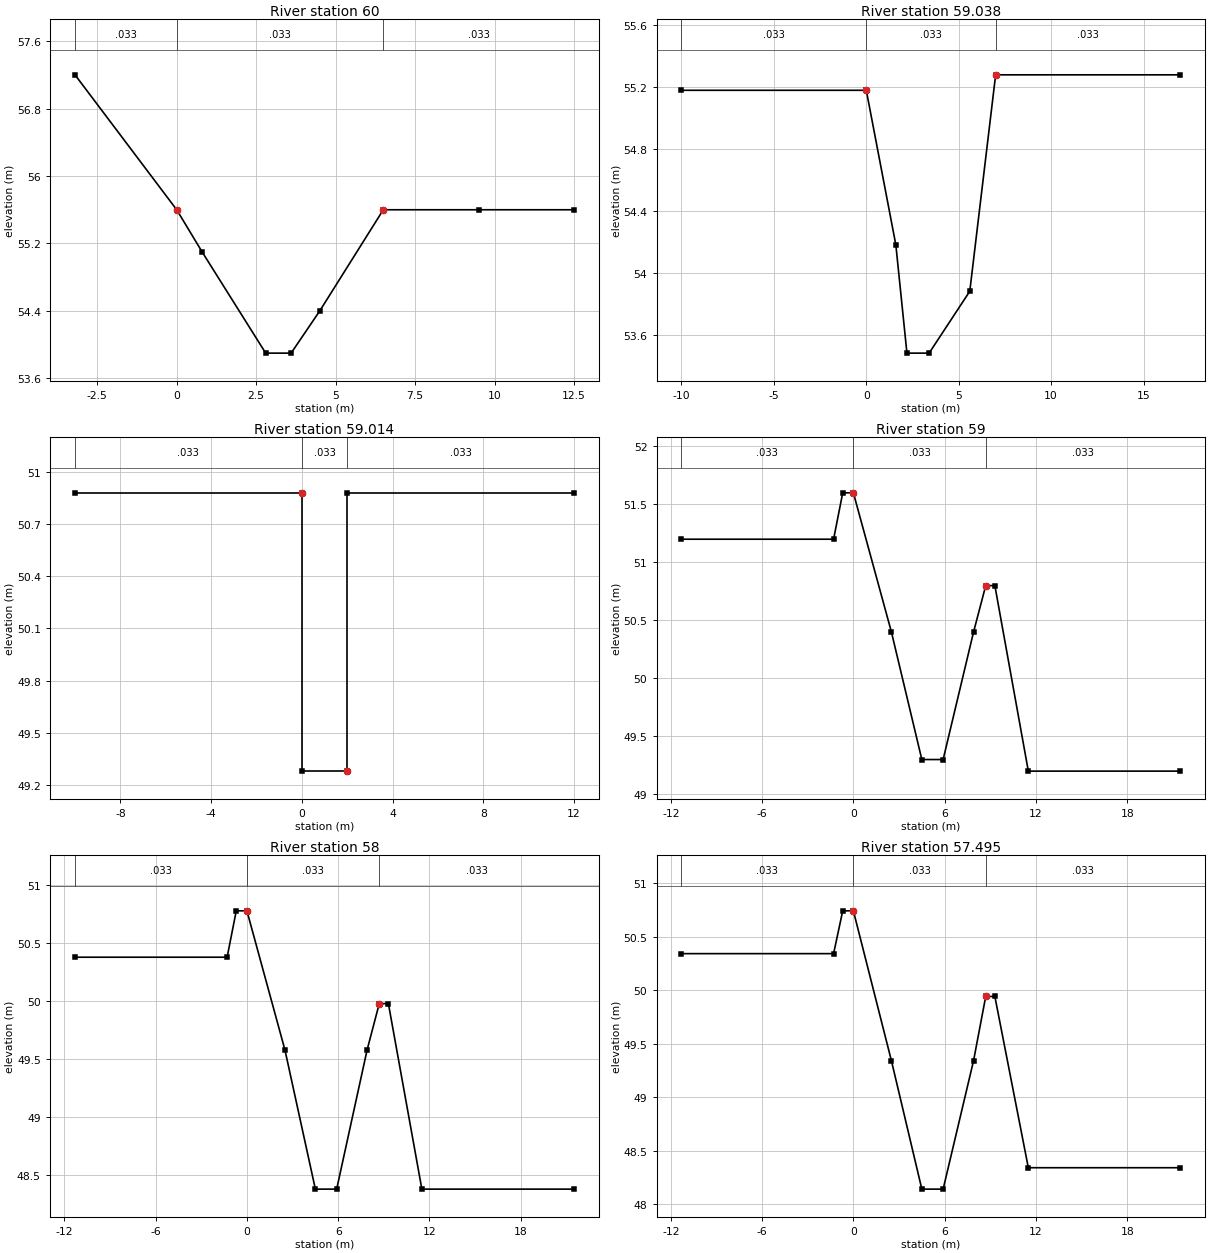
Type RM Length L Ch R = 1 ,60      ,12,12,12
#Sta/Elev= 9
    -3.2    57.2       0    55.6      .8    55.1     2.8    53.9     3.6    53.9
     4.5    54.4     6.5    55.6     9.5    55.6    12.5    55.6
#Mann= 3 , 0 , 0
    -3.2    .033       0       0    .033       0     6.5    .033       0
Bank Sta=0,6.5
XS Rating Curve= 0
Exp/Cntr=.3,.1

Type RM Length L Ch R = 1 ,59.038  ,24,24,24
#Sta/Elev= 8
     -10   55.18       0   55.18     1.6   54.18     2.2   53.48     3.4   53.48
     5.6   53.88       7   55.28      17   55.28
#Mann= 3 , 0 , 0
     -10    .033       0       0    .033       0       7    .033       0
Bank Sta=0,7
XS Rating Curve= 0
Exp/Cntr=.3,.1

Type RM Length L Ch R = 1 ,59.014  ,14,14,14
#Sta/Elev= 6
     -10   50.88       0   50.88       0   49.28       2   49.28       2   50.88
      12   50.88
#Mann= 3 , 0 , 0
     -10    .033       0       0    .033       0       2    .033       0
Bank Sta=0,2
XS Rating Curve= 0
Exp/Cntr=.3,.1

Type RM Length L Ch R = 1 ,59      ,50,50,50
#Sta/Elev= 12
   -11.3    51.2    -1.3    51.2     -.7    51.6       0    51.6     2.5    50.4
     4.5    49.3     5.9    49.3     7.9    50.4     8.7    50.8     9.3    50.8
    11.5    49.2    21.5    49.2
#Mann= 3 , 0 , 0
   -11.3    .033       0       0    .033       0     8.7    .033       0
Bank Sta=0,8.7
XS Rating Curve= 0
Exp/Cntr=.3,.1

Type RM Length L Ch R = 1 ,58      ,.5,.5,.5
#Sta/Elev= 12
   -11.3   50.38    -1.3   50.38     -.7   50.78       0   50.78     2.5   49.58
     4.5   48.38     5.9   48.38     7.9   49.58     8.7   49.98     9.3   49.98
    11.5   48.38    21.5   48.38
#Mann= 3 , 0 , 0
   -11.3    .033       0       0    .033       0     8.7    .033       0
Bank Sta=0,8.7
XS Rating Curve= 0
Exp/Cntr=.3,.1

Type RM Length L Ch R = 1 ,57.495  ,.5,.5,.5
#Sta/Elev= 12
   -11.3   50.34    -1.3   50.34     -.7   50.74       0   50.74     2.5   49.34
     4.5   48.14     5.9   48.14     7.9   49.34     8.7   49.94     9.3   49.94
    11.5   48.34    21.5   48.34
#Mann= 3 , 0 , 0
   -11.3    .033       0       0    .033       0     8.7    .033       0
Bank Sta=0,8.7
XS Rating Curve= 0
Exp/Cntr=.3,.1

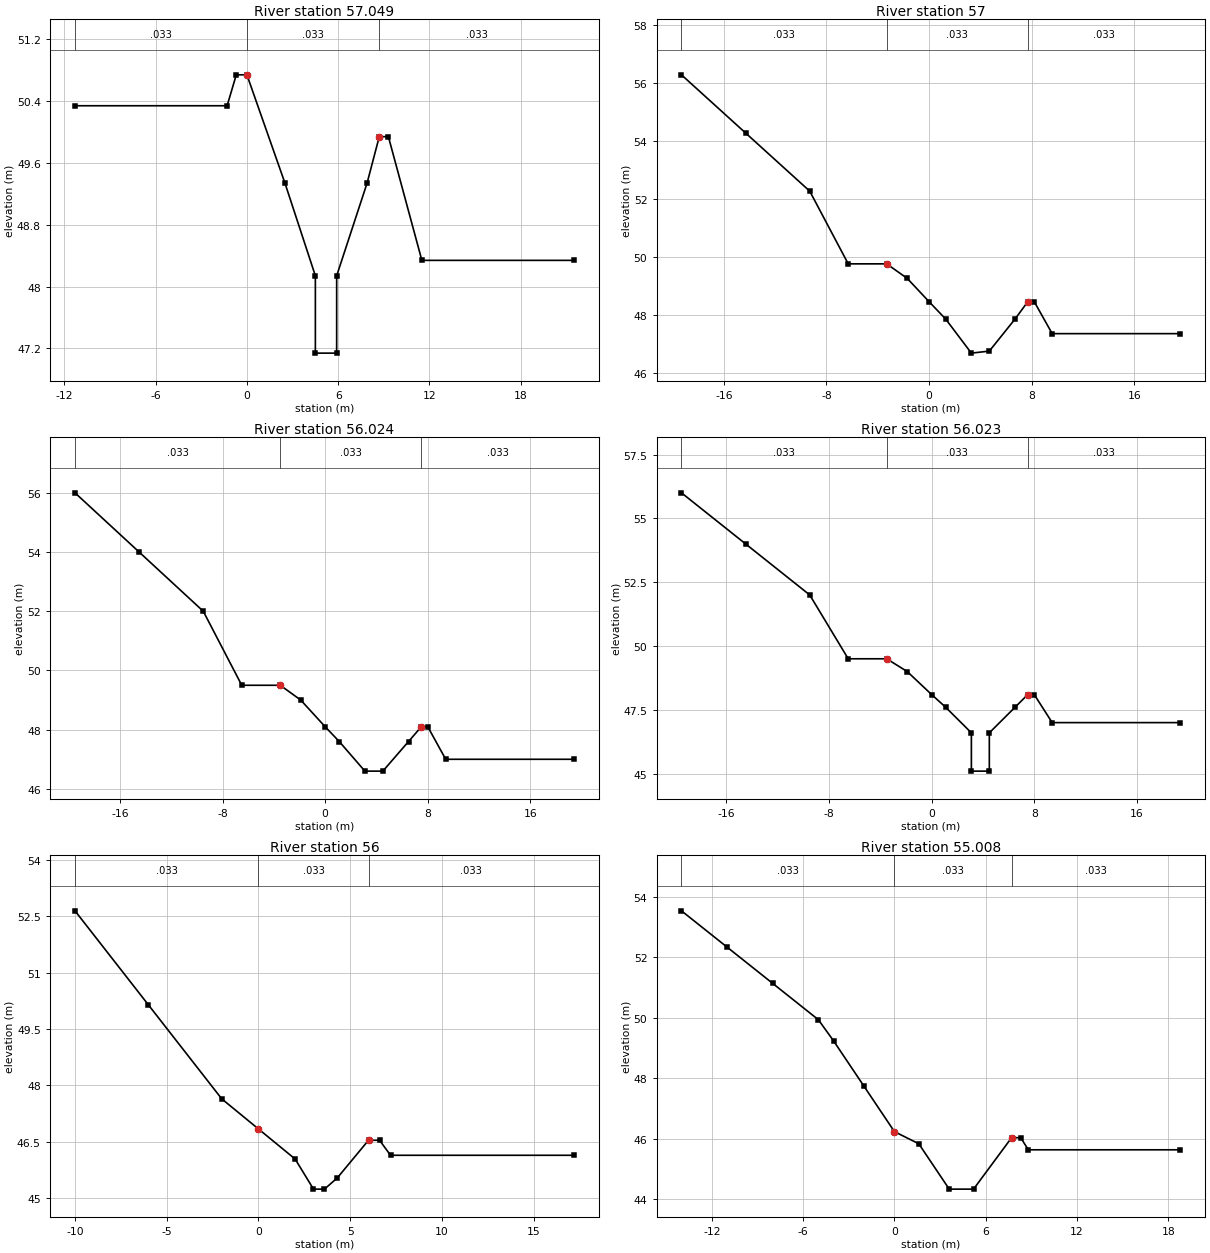
Type RM Length L Ch R = 1 ,57.049  ,49,49,49
#Sta/Elev= 14
   -11.3   50.34    -1.3   50.34     -.7   50.74       0   50.74     2.5   49.34
     4.5   48.14     4.5   47.14     5.9   47.14     5.9   48.14     7.9   49.34
     8.7   49.94     9.3   49.94    11.5   48.34    21.5   48.34
#Mann= 3 , 0 , 0
   -11.3    .033       0       0    .033       0     8.7    .033       0
Bank Sta=0,8.7
XS Rating Curve= 0
Exp/Cntr=.3,.1

Type RM Length L Ch R = 1 ,57      ,26,26,26
#Sta/Elev= 15
   -19.3   56.27   -14.3   54.27    -9.3   52.27    -6.3   49.77    -3.3   49.77
    -1.7   49.27       0   48.47     1.3   47.87     3.3    46.7     4.7   46.77
     6.7   47.87     7.7   48.47     8.2   48.47     9.6   47.37    19.6   47.37
#Mann= 3 , 0 , 0
   -19.3    .033       0    -3.3    .033       0     7.7    .033       0
Bank Sta=-3.3,7.7
XS Rating Curve= 0
Exp/Cntr=.3,.1

Type RM Length L Ch R = 1 ,56.024  ,1,1,1
#Sta/Elev= 15
   -19.5      56   -14.5      54    -9.5      52    -6.5    49.5    -3.5    49.5
    -1.9      49       0    48.1     1.1    47.6     3.1    46.6     4.5    46.6
     6.5    47.6     7.5    48.1       8    48.1     9.4      47    19.4      47
#Mann= 3 , 0 , 0
   -19.5    .033       0    -3.5    .033       0     7.5    .033       0
Bank Sta=-3.5,7.5
XS Rating Curve= 0
Exp/Cntr=.3,.1

Type RM Length L Ch R = 1 ,56.023  ,23,23,23
#Sta/Elev= 17
   -19.5      56   -14.5      54    -9.5      52    -6.5    49.5    -3.5    49.5
    -1.9      49       0    48.1     1.1    47.6     3.1    46.6     3.1    45.1
     4.5    45.1     4.5    46.6     6.5    47.6     7.5    48.1       8    48.1
     9.4      47    19.4      47
#Mann= 3 , 0 , 0
   -19.5    .033       0    -3.5    .033       0     7.5    .033       0
Bank Sta=-3.5,7.5
XS Rating Curve= 0
Exp/Cntr=.3,.1

Type RM Length L Ch R = 1 ,56      ,42,42,42
#Sta/Elev= 12
     -10   52.64      -6   50.14      -2   47.64       0   46.84       2   46.04
       3   45.24     3.6   45.24     4.3   45.54       6   46.54     6.6   46.54
     7.2   46.14    17.2   46.14
#Mann= 3 , 0 , 0
     -10    .033       0       0    .033       0       6    .033       0
Bank Sta=0,6
XS Rating Curve= 0
Exp/Cntr=.3,.1

Type RM Length L Ch R = 1 ,55.008  ,1,1,1
#Sta/Elev= 14
     -14   53.53     -11   52.33      -8   51.13      -5   49.93      -4   49.23
      -2   47.73       0   46.23     1.6   45.83     3.6   44.33     5.2   44.33
     7.7   46.03     8.3   46.03     8.8   45.63    18.8   45.63
#Mann= 3 , 0 , 0
     -14    .033       0       0    .033       0     7.7    .033       0
Bank Sta=0,7.7
XS Rating Curve= 0
Exp/Cntr=.3,.1

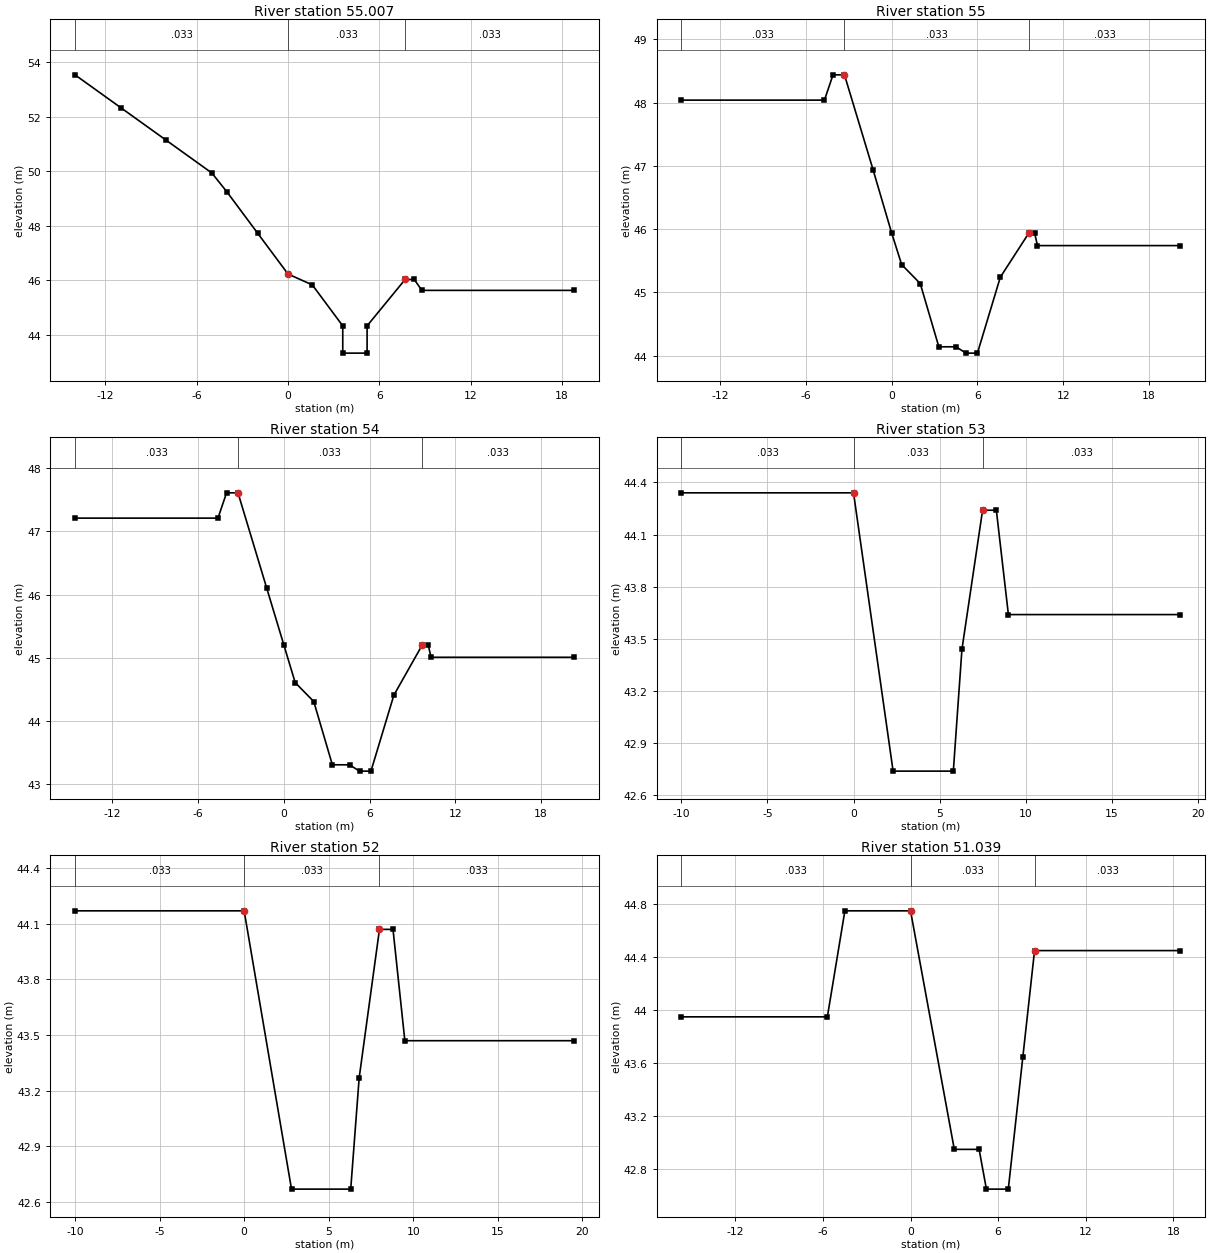
Type RM Length L Ch R = 1 ,55.007  ,7,7,7
#Sta/Elev= 16
     -14   53.53     -11   52.33      -8   51.13      -5   49.93      -4   49.23
      -2   47.73       0   46.23     1.6   45.83     3.6   44.33     3.6   43.33
     5.2   43.33     5.2   44.33     7.7   46.03     8.3   46.03     8.8   45.63
    18.8   45.63
#Mann= 3 , 0 , 0
     -14    .033       0       0    .033       0     7.7    .033       0
Bank Sta=0,7.7
XS Rating Curve= 0
Exp/Cntr=.3,.1

Type RM Length L Ch R = 1 ,55      ,50,50,50
#Sta/Elev= 17
   -14.7   48.04    -4.7   48.04    -4.1   48.44    -3.3   48.44    -1.3   46.94
       0   45.94      .7   45.44       2   45.14     3.3   44.14     4.5   44.14
     5.2   44.04       6   44.04     7.6   45.24     9.6   45.94      10   45.94
    10.2   45.74    20.2   45.74
#Mann= 3 , 0 , 0
   -14.7    .033       0    -3.3    .033       0     9.6    .033       0
Bank Sta=-3.3,9.6
XS Rating Curve= 0
Exp/Cntr=.3,.1

Type RM Length L Ch R = 1 ,54      ,50,50,50
#Sta/Elev= 17
   -14.6   47.21    -4.6   47.21      -4   47.61    -3.2   47.61    -1.2   46.11
       0   45.21      .8   44.61     2.1   44.31     3.4   43.31     4.6   43.31
     5.3   43.21     6.1   43.21     7.7   44.41     9.7   45.21    10.1   45.21
    10.3   45.01    20.3   45.01
#Mann= 3 , 0 , 0
   -14.6    .033       0    -3.2    .033       0     9.7    .033       0
Bank Sta=-3.2,9.7
XS Rating Curve= 0
Exp/Cntr=.3,.1

Type RM Length L Ch R = 1 ,53      ,50,50,50
#Sta/Elev= 9
     -10   44.34       0   44.34     2.3   42.74     5.8   42.74     6.3   43.44
     7.5   44.24     8.3   44.24       9   43.64      19   43.64
#Mann= 3 , 0 , 0
     -10    .033       0       0    .033       0     7.5    .033       0
Bank Sta=0,7.5
XS Rating Curve= 0
Exp/Cntr=.3,.1

Type RM Length L Ch R = 1 ,52      ,11,11,11
#Sta/Elev= 9
     -10   44.17       0   44.17     2.8   42.67     6.3   42.67     6.8   43.27
       8   44.07     8.8   44.07     9.5   43.47    19.5   43.47
#Mann= 3 , 0 , 0
     -10    .033       0       0    .033       0       8    .033       0
Bank Sta=0,8
XS Rating Curve= 0
Exp/Cntr=.3,.1

Type RM Length L Ch R = 1 ,51.039  ,39,39,39
#Sta/Elev= 11
   -15.7   43.95    -5.7   43.95    -4.5   44.75       0   44.75       3   42.95
     4.7   42.95     5.2   42.65     6.7   42.65     7.7   43.65     8.5   44.45
    18.5   44.45
#Mann= 3 , 0 , 0
   -15.7    .033       0       0    .033       0     8.5    .033       0
Bank Sta=0,8.5
XS Rating Curve= 0
Exp/Cntr=.3,.1