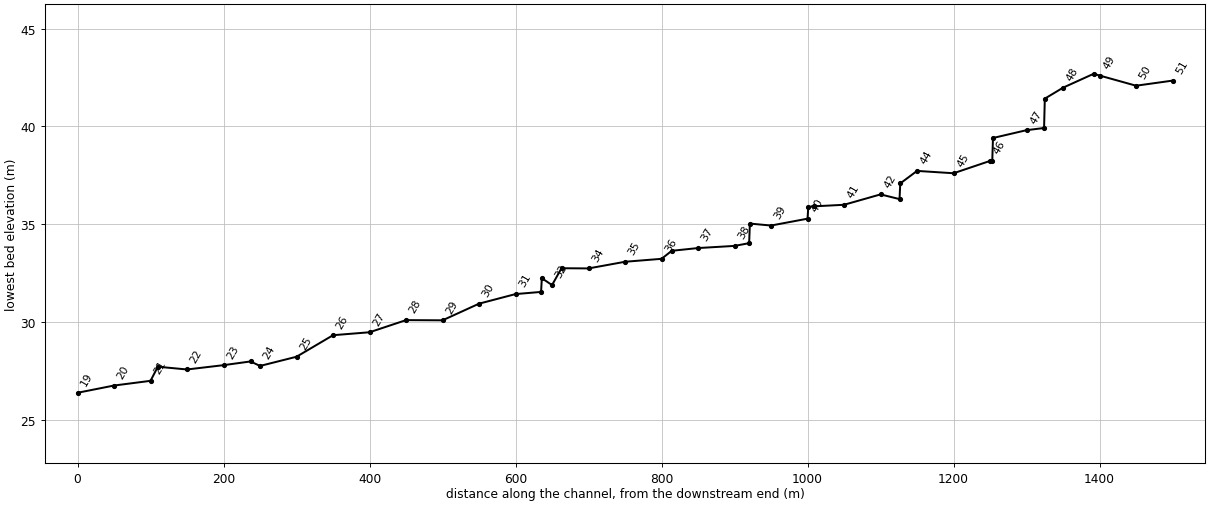
HEC-RAS study DONGSIL.prj: DONGSIL

--- DONGSIL.g01 (geometry) --- (continued)

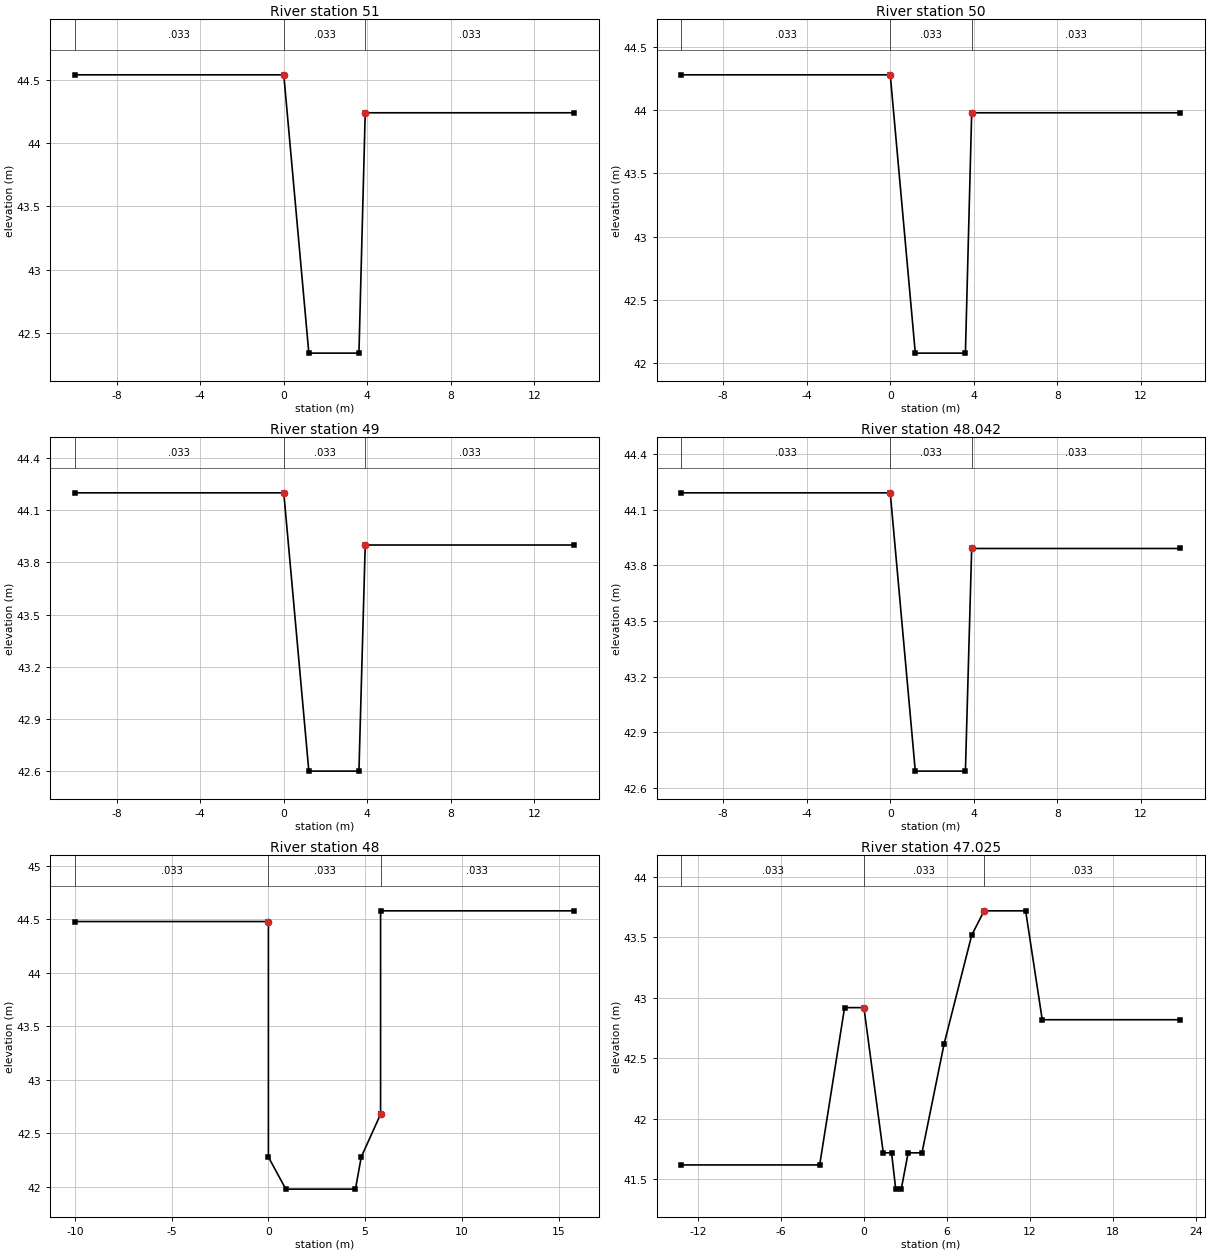
Type RM Length L Ch R = 1 ,51      ,50,50,50
#Sta/Elev= 6
     -10   44.54       0   44.54     1.2   42.34     3.6   42.34     3.9   44.24
    13.9   44.24
#Mann= 3 , 0 , 0
     -10    .033       0       0    .033       0     3.9    .033       0
Bank Sta=0,3.9
XS Rating Curve= 0
Exp/Cntr=.3,.1

Type RM Length L Ch R = 1 ,50      ,50,50,50
#Sta/Elev= 6
     -10   44.28       0   44.28     1.2   42.08     3.6   42.08     3.9   43.98
    13.9   43.98
#Mann= 3 , 0 , 0
     -10    .033       0       0    .033       0     3.9    .033       0
Bank Sta=0,3.9
XS Rating Curve= 0
Exp/Cntr=.3,.1

Type RM Length L Ch R = 1 ,49      ,8,8,8
#Sta/Elev= 6
     -10    44.2       0    44.2     1.2    42.6     3.6    42.6     3.9    43.9
    13.9    43.9
#Mann= 3 , 0 , 0
     -10    .033       0       0    .033       0     3.9    .033       0
Bank Sta=0,3.9
XS Rating Curve= 0
Exp/Cntr=.3,.1

Type RM Length L Ch R = 1 ,48.042  ,42,42,42
#Sta/Elev= 6
     -10   44.19       0   44.19     1.2   42.69     3.6   42.69     3.9   43.89
    13.9   43.89
#Mann= 3 , 0 , 0
     -10    .033       0       0    .033       0     3.9    .033       0
Bank Sta=0,3.9
XS Rating Curve= 0
Exp/Cntr=.3,.1

Type RM Length L Ch R = 1 ,48      ,25,25,25
#Sta/Elev= 10
     -10   44.48       0   44.48       0   42.28      .9   41.98     4.5   41.98
     4.8   42.28     5.8   42.68     5.8   42.68     5.8   44.58    15.8   44.58
#Mann= 3 , 0 , 0
     -10    .033       0       0    .033       0     5.8    .033       0
Bank Sta=0,5.8
XS Rating Curve= 0
Exp/Cntr=.3,.1

Type RM Length L Ch R = 1 ,47.025  ,1,1,1
#Sta/Elev= 16
   -13.2   41.62    -3.2   41.62    -1.4   42.92       0   42.92     1.4   41.72
       2   41.72     2.3   41.42     2.7   41.42     3.2   41.72     4.2   41.72
     5.8   42.62     7.8   43.52     8.7   43.72    11.7   43.72    12.9   42.82
    22.9   42.82
#Mann= 3 , 0 , 0
   -13.2    .033       0       0    .033       0     8.7    .033       0
Bank Sta=0,8.7
XS Rating Curve= 0
Exp/Cntr=.3,.1

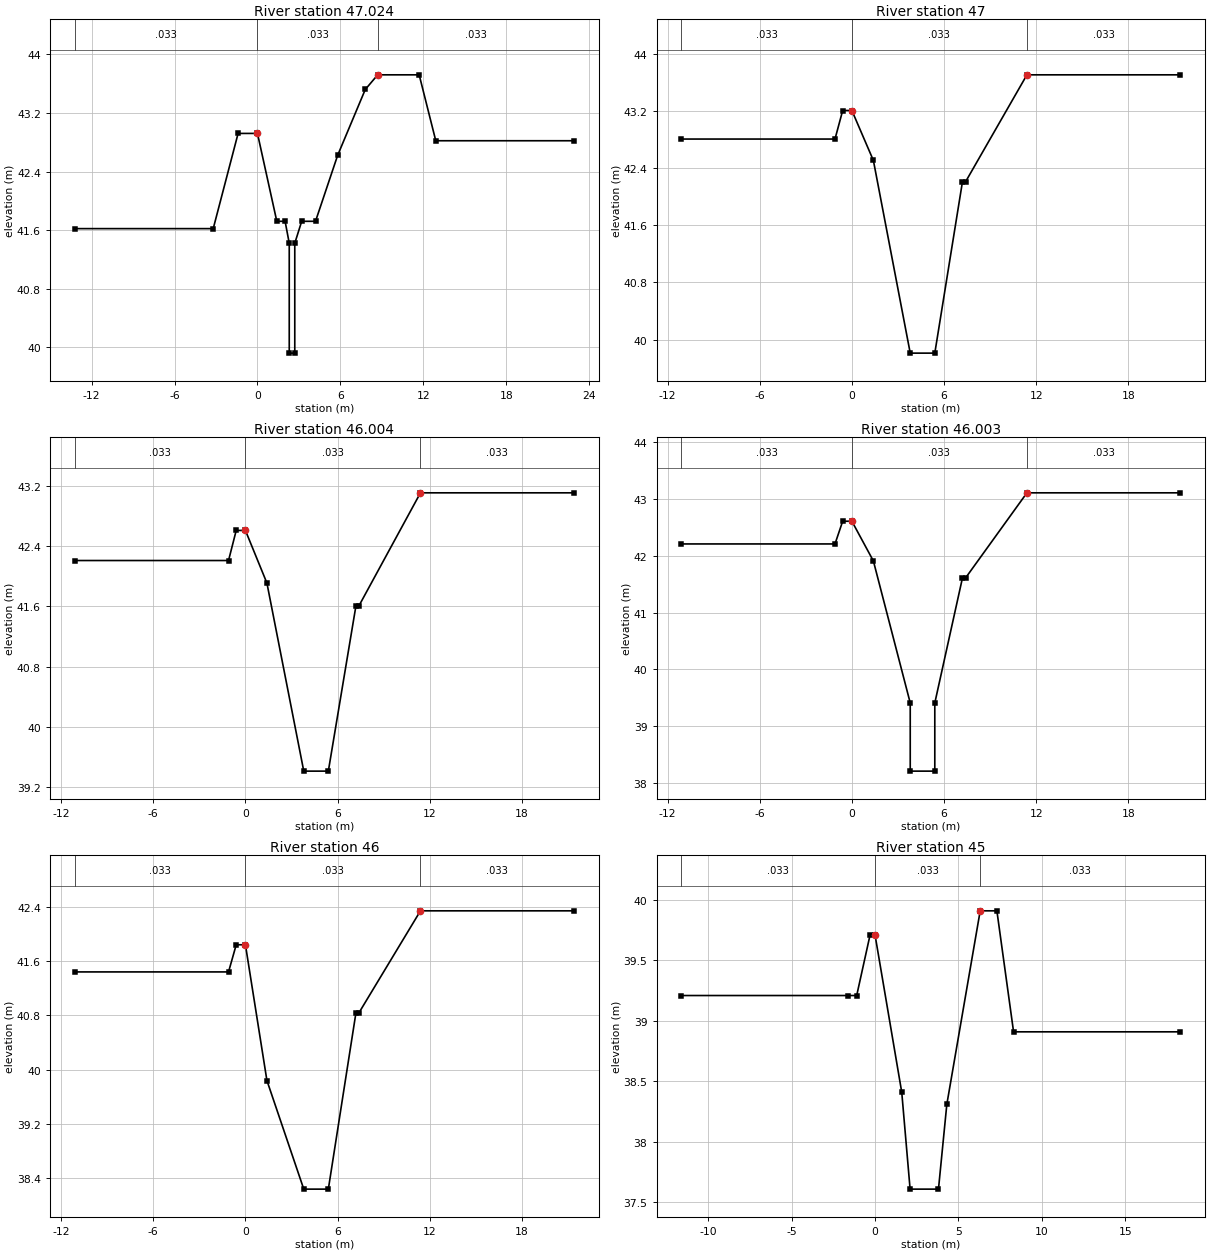
Type RM Length L Ch R = 1 ,47.024  ,24,24,24
#Sta/Elev= 18
   -13.2   41.62    -3.2   41.62    -1.4   42.92       0   42.92     1.4   41.72
       2   41.72     2.3   41.42     2.3   39.92     2.7   39.92     2.7   41.42
     3.2   41.72     4.2   41.72     5.8   42.62     7.8   43.52     8.7   43.72
    11.7   43.72    12.9   42.82    22.9   42.82
#Mann= 3 , 0 , 0
   -13.2    .033       0       0    .033       0     8.7    .033       0
Bank Sta=0,8.7
XS Rating Curve= 0
Exp/Cntr=.3,.1

Type RM Length L Ch R = 1 ,47      ,46,46,46
#Sta/Elev= 11
   -11.1   42.81    -1.1   42.81     -.6   43.21       0   43.21     1.4   42.51
     3.8   39.81     5.4   39.81     7.2   42.21     7.4   42.21    11.4   43.71
    21.4   43.71
#Mann= 3 , 0 , 0
   -11.1    .033       0       0    .033       0    11.4    .033       0
Bank Sta=0,11.4
XS Rating Curve= 0
Exp/Cntr=.3,.1

Type RM Length L Ch R = 1 ,46.004  ,1,1,1
#Sta/Elev= 11
   -11.1   42.21    -1.1   42.21     -.6   42.61       0   42.61     1.4   41.91
     3.8   39.41     5.4   39.41     7.2   41.61     7.4   41.61    11.4   43.11
    21.4   43.11
#Mann= 3 , 0 , 0
   -11.1    .033       0       0    .033       0    11.4    .033       0
Bank Sta=0,11.4
XS Rating Curve= 0
Exp/Cntr=.3,.1

Type RM Length L Ch R = 1 ,46.003  ,3,3,3
#Sta/Elev= 13
   -11.1   42.21    -1.1   42.21     -.6   42.61       0   42.61     1.4   41.91
     3.8   39.41     3.8   38.21     5.4   38.21     5.4   39.41     7.2   41.61
     7.4   41.61    11.4   43.11    21.4   43.11
#Mann= 3 , 0 , 0
   -11.1    .033       0       0    .033       0    11.4    .033       0
Bank Sta=0,11.4
XS Rating Curve= 0
Exp/Cntr=.3,.1

Type RM Length L Ch R = 1 ,46      ,50,50,50
#Sta/Elev= 11
   -11.1   41.44    -1.1   41.44     -.6   41.84       0   41.84     1.4   39.84
     3.8   38.24     5.4   38.24     7.2   40.84     7.4   40.84    11.4   42.34
    21.4   42.34
#Mann= 3 , 0 , 0
   -11.1    .033       0       0    .033       0    11.4    .033       0
Bank Sta=0,11.4
XS Rating Curve= 0
Exp/Cntr=.3,.1

Type RM Length L Ch R = 1 ,45      ,50,50,50
#Sta/Elev= 13
   -11.6   39.21    -1.6   39.21    -1.1   39.21     -.3   39.71       0   39.71
     1.6   38.41     2.1   37.61     3.8   37.61     4.3   38.31     6.3   39.91
     7.3   39.91     8.3   38.91    18.3   38.91
#Mann= 3 , 0 , 0
   -11.6    .033       0       0    .033       0     6.3    .033       0
Bank Sta=0,6.3
XS Rating Curve= 0
Exp/Cntr=.3,.1

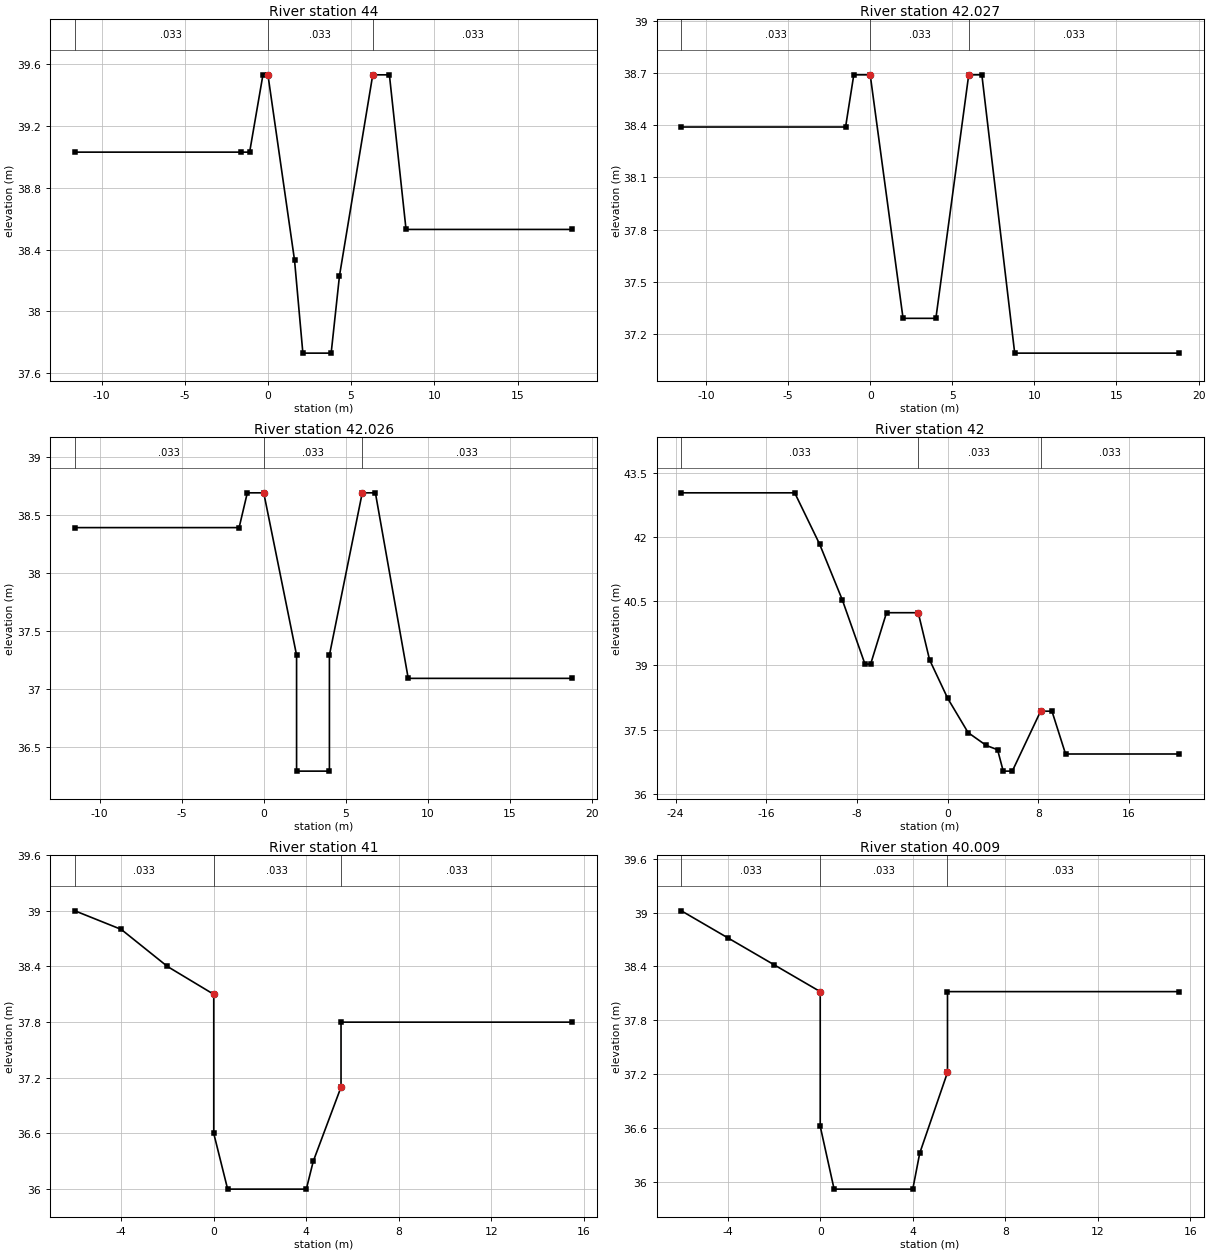
Type RM Length L Ch R = 1 ,44      ,23,23,23
#Sta/Elev= 13
   -11.6   39.03    -1.6   39.03    -1.1   39.03     -.3   39.53       0   39.53
     1.6   38.33     2.1   37.73     3.8   37.73     4.3   38.23     6.3   39.53
     7.3   39.53     8.3   38.53    18.3   38.53
#Mann= 3 , 0 , 0
   -11.6    .033       0       0    .033       0     6.3    .033       0
Bank Sta=0,6.3
XS Rating Curve= 0
Exp/Cntr=.3,.1

Type RM Length L Ch R = 1 ,42.027  ,1,1,1
#Sta/Elev= 10
   -11.5   38.39    -1.5   38.39      -1   38.69       0   38.69       2   37.29
       4   37.29       6   38.69     6.8   38.69     8.8   37.09    18.8   37.09
#Mann= 3 , 0 , 0
   -11.5    .033       0       0    .033       0       6    .033       0
Bank Sta=0,6
XS Rating Curve= 0
Exp/Cntr=.3,.1

Type RM Length L Ch R = 1 ,42.026  ,26,26,26
#Sta/Elev= 12
   -11.5   38.39    -1.5   38.39      -1   38.69       0   38.69       2   37.29
       2   36.29       4   36.29       4   37.29       6   38.69     6.8   38.69
     8.8   37.09    18.8   37.09
#Mann= 3 , 0 , 0
   -11.5    .033       0       0    .033       0       6    .033       0
Bank Sta=0,6
XS Rating Curve= 0
Exp/Cntr=.3,.1

Type RM Length L Ch R = 1 ,42      ,50,50,50
#Sta/Elev= 19
   -23.5   43.03   -13.5   43.03   -11.3   41.83    -9.3   40.53    -7.3   39.03
    -6.8   39.03    -5.4   40.23    -2.6   40.23    -1.6   39.13       0   38.23
     1.8   37.43     3.4   37.13     4.4   37.03     4.9   36.53     5.7   36.53
     8.2   37.93     9.2   37.93    10.4   36.93    20.4   36.93
#Mann= 3 , 0 , 0
   -23.5    .033       0    -2.6    .033       0     8.2    .033       0
Bank Sta=-2.6,8.2
XS Rating Curve= 0
Exp/Cntr=.3,.1

Type RM Length L Ch R = 1 ,41      ,41,41,41
#Sta/Elev= 11
      -6      39      -4    38.8      -2    38.4       0    38.1       0    36.6
      .6      36       4      36     4.3    36.3     5.5    37.1     5.5    37.8
    15.5    37.8
#Mann= 3 , 0 , 0
      -6    .033       0       0    .033       0     5.5    .033       0
Bank Sta=0,5.5
XS Rating Curve= 0
Exp/Cntr=.3,.1

Type RM Length L Ch R = 1 ,40.009  ,8,8,8
#Sta/Elev= 11
      -6   39.02      -4   38.72      -2   38.42       0   38.12       0   36.62
      .6   35.92       4   35.92     4.3   36.32     5.5   37.22     5.5   38.12
    15.5   38.12
#Mann= 3 , 0 , 0
      -6    .033       0       0    .033       0     5.5    .033       0
Bank Sta=0,5.5
XS Rating Curve= 0
Exp/Cntr=.3,.1

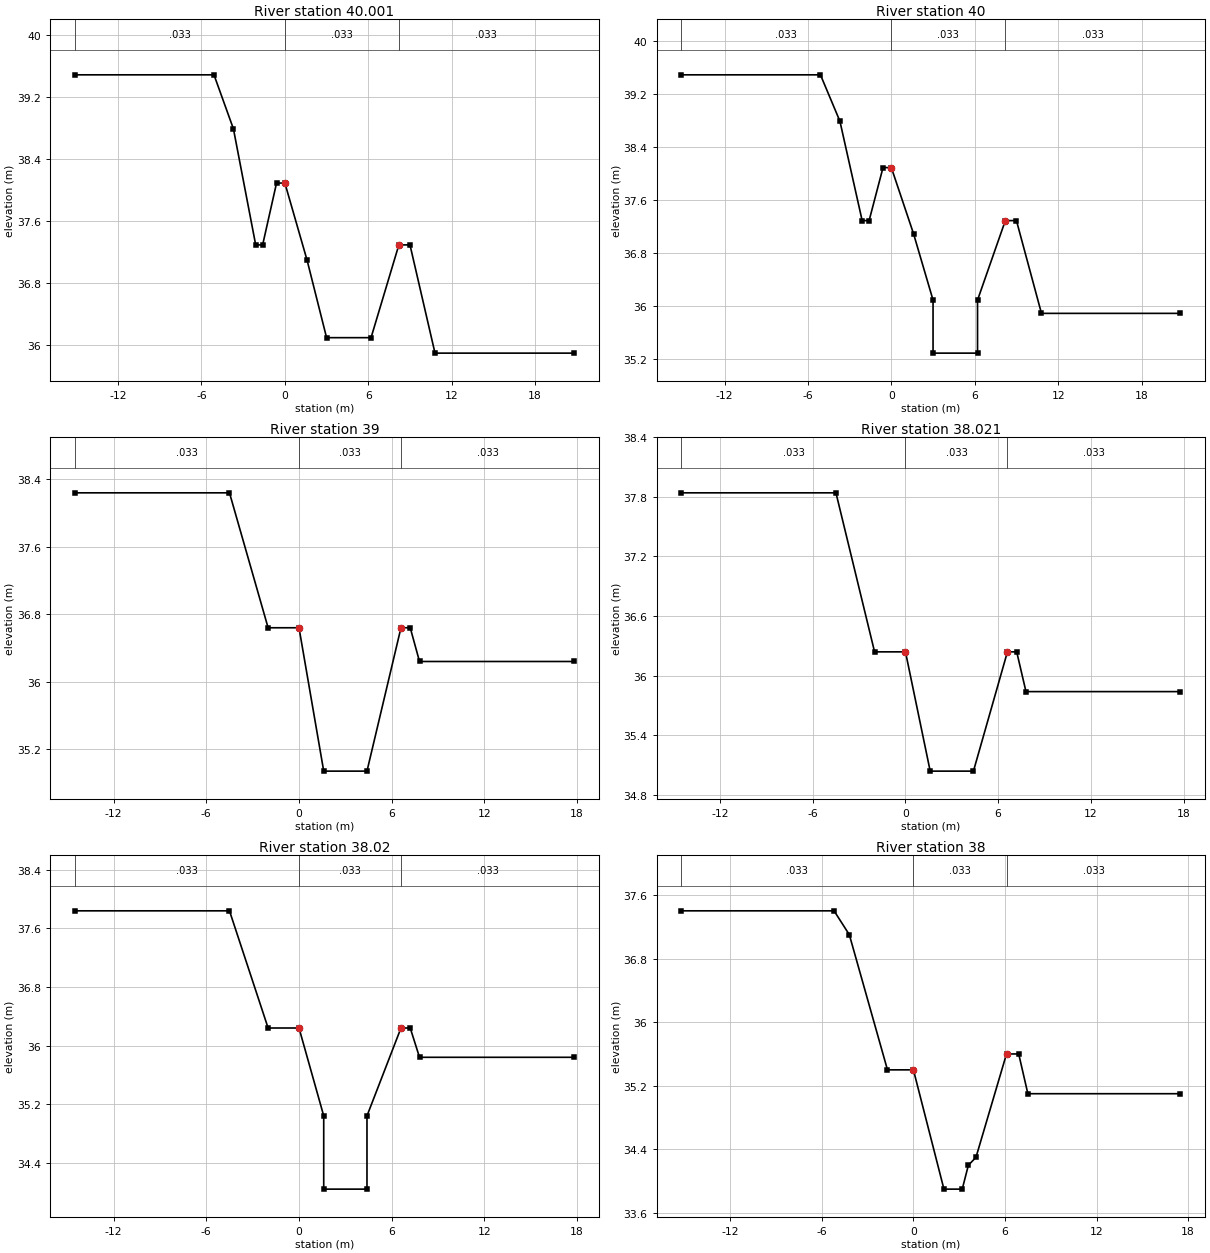
Type RM Length L Ch R = 1 ,40.001  ,1,1,1
#Sta/Elev= 14
   -15.1   39.49    -5.1   39.49    -3.7   38.79    -2.1   37.29    -1.6   37.29
     -.6   38.09       0   38.09     1.6   37.09       3   36.09     6.2   36.09
     8.2   37.29       9   37.29    10.8   35.89    20.8   35.89
#Mann= 3 , 0 , 0
   -15.1    .033       0       0    .033       0     8.2    .033       0
Bank Sta=0,8.2
XS Rating Curve= 0
Exp/Cntr=.3,.1

Type RM Length L Ch R = 1 ,40      ,50,50,50
#Sta/Elev= 16
   -15.1   39.49    -5.1   39.49    -3.7   38.79    -2.1   37.29    -1.6   37.29
     -.6   38.09       0   38.09     1.6   37.09       3   36.09       3   35.29
     6.2   35.29     6.2   36.09     8.2   37.29       9   37.29    10.8   35.89
    20.8   35.89
#Mann= 3 , 0 , 0
   -15.1    .033       0       0    .033       0     8.2    .033       0
Bank Sta=0,8.2
XS Rating Curve= 0
Exp/Cntr=.3,.1

Type RM Length L Ch R = 1 ,39      ,29,29,29
#Sta/Elev= 10
   -14.5   38.24    -4.5   38.24      -2   36.64       0   36.64     1.6   34.94
     4.4   34.94     6.6   36.64     7.2   36.64     7.8   36.24    17.8   36.24
#Mann= 3 , 0 , 0
   -14.5    .033       0       0    .033       0     6.6    .033       0
Bank Sta=0,6.6
XS Rating Curve= 0
Exp/Cntr=.3,.1

Type RM Length L Ch R = 1 ,38.021  ,1,1,1
#Sta/Elev= 10
   -14.5   37.84    -4.5   37.84      -2   36.24       0   36.24     1.6   35.04
     4.4   35.04     6.6   36.24     7.2   36.24     7.8   35.84    17.8   35.84
#Mann= 3 , 0 , 0
   -14.5    .033       0       0    .033       0     6.6    .033       0
Bank Sta=0,6.6
XS Rating Curve= 0
Exp/Cntr=.3,.1

Type RM Length L Ch R = 1 ,38.02   ,20,20,20
#Sta/Elev= 12
   -14.5   37.84    -4.5   37.84      -2   36.24       0   36.24     1.6   35.04
     1.6   34.04     4.4   34.04     4.4   35.04     6.6   36.24     7.2   36.24
     7.8   35.84    17.8   35.84
#Mann= 3 , 0 , 0
   -14.5    .033       0       0    .033       0     6.6    .033       0
Bank Sta=0,6.6
XS Rating Curve= 0
Exp/Cntr=.3,.1

Type RM Length L Ch R = 1 ,38      ,50,50,50
#Sta/Elev= 13
   -15.2    37.4    -5.2    37.4    -4.2    37.1    -1.7    35.4       0    35.4
       2    33.9     3.2    33.9     3.6    34.2     4.1    34.3     6.1    35.6
     6.9    35.6     7.5    35.1    17.5    35.1
#Mann= 3 , 0 , 0
   -15.2    .033       0       0    .033       0     6.1    .033       0
Bank Sta=0,6.1
XS Rating Curve= 0
Exp/Cntr=.3,.1

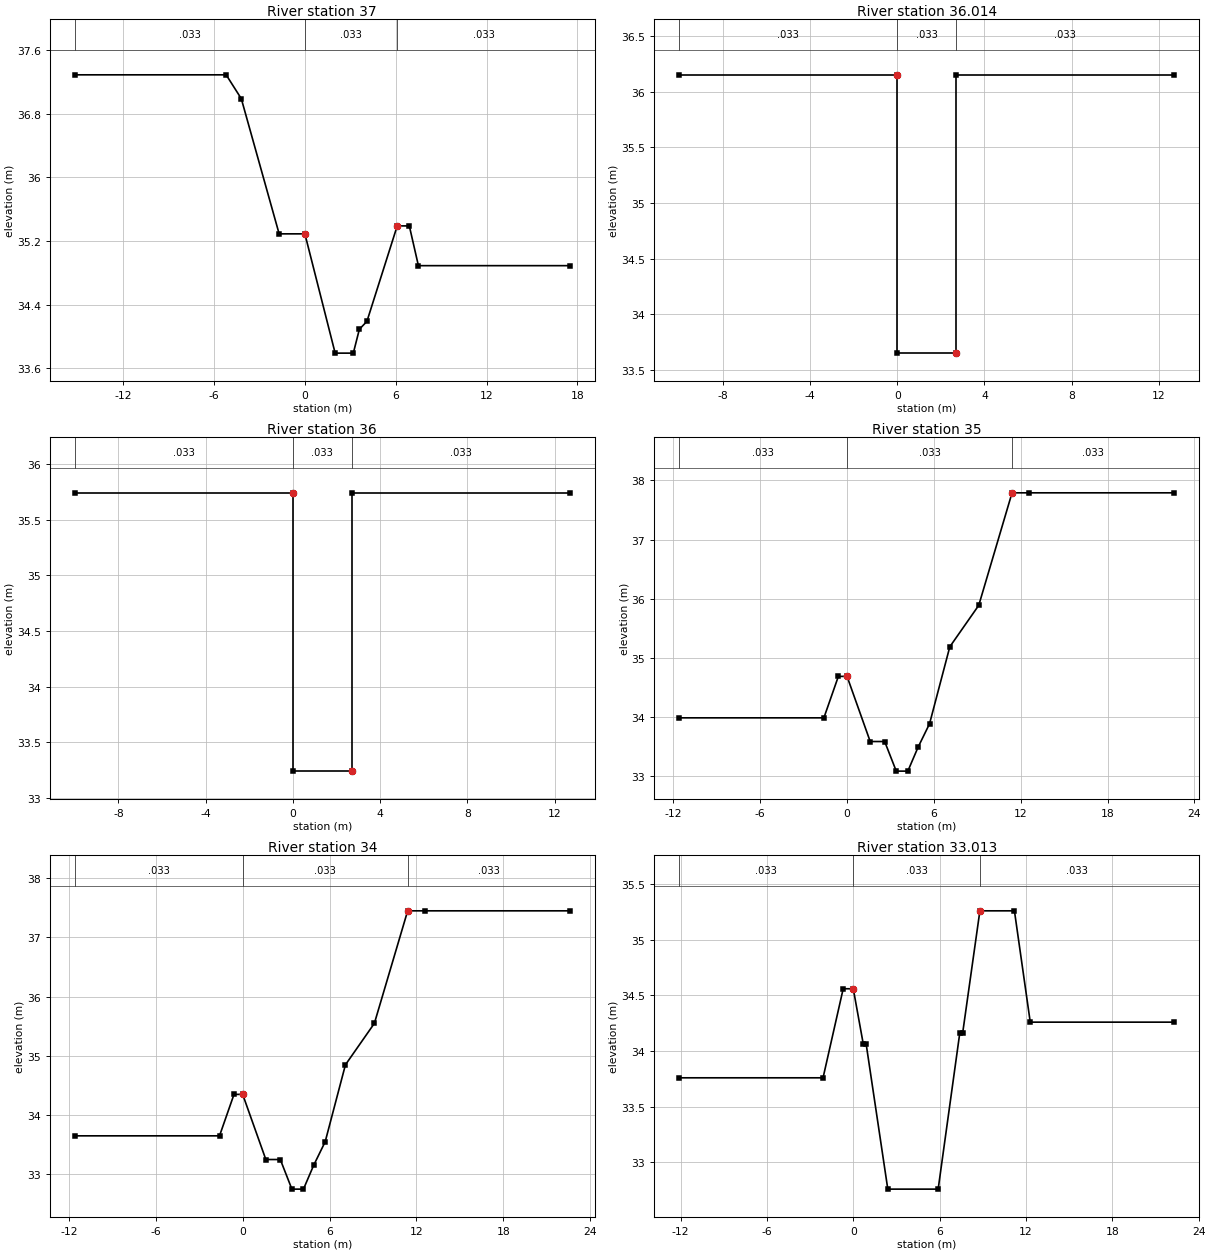
Type RM Length L Ch R = 1 ,37      ,36,36,36
#Sta/Elev= 13
   -15.2   37.29    -5.2   37.29    -4.2   36.99    -1.7   35.29       0   35.29
       2   33.79     3.2   33.79     3.6   34.09     4.1   34.19     6.1   35.39
     6.9   35.39     7.5   34.89    17.5   34.89
#Mann= 3 , 0 , 0
   -15.2    .033       0       0    .033       0     6.1    .033       0
Bank Sta=0,6.1
XS Rating Curve= 0
Exp/Cntr=.3,.1

Type RM Length L Ch R = 1 ,36.014  ,14,14,14
#Sta/Elev= 6
     -10   36.15       0   36.15       0   33.65     2.7   33.65     2.7   36.15
    12.7   36.15
#Mann= 3 , 0 , 0
     -10    .033       0       0    .033       0     2.7    .033       0
Bank Sta=0,2.7
XS Rating Curve= 0
Exp/Cntr=.3,.1

Type RM Length L Ch R = 1 ,36      ,50,50,50
#Sta/Elev= 6
     -10   35.74       0   35.74       0   33.24     2.7   33.24     2.7   35.74
    12.7   35.74
#Mann= 3 , 0 , 0
     -10    .033       0       0    .033       0     2.7    .033       0
Bank Sta=0,2.7
XS Rating Curve= 0
Exp/Cntr=.3,.1

Type RM Length L Ch R = 1 ,35      ,50,50,50
#Sta/Elev= 15
   -11.6   33.99    -1.6   33.99     -.6   34.69       0   34.69     1.6   33.59
     2.6   33.59     3.4   33.09     4.2   33.09     4.9   33.49     5.7   33.89
     7.1   35.19     9.1   35.89    11.4   37.79    12.6   37.79    22.6   37.79
#Mann= 3 , 0 , 0
   -11.6    .033       0       0    .033       0    11.4    .033       0
Bank Sta=0,11.4
XS Rating Curve= 0
Exp/Cntr=.3,.1

Type RM Length L Ch R = 1 ,34      ,37,37,37
#Sta/Elev= 15
   -11.6   33.65    -1.6   33.65     -.6   34.35       0   34.35     1.6   33.25
     2.6   33.25     3.4   32.75     4.2   32.75     4.9   33.15     5.7   33.55
     7.1   34.85     9.1   35.55    11.4   37.45    12.6   37.45    22.6   37.45
#Mann= 3 , 0 , 0
   -11.6    .033       0       0    .033       0    11.4    .033       0
Bank Sta=0,11.4
XS Rating Curve= 0
Exp/Cntr=.3,.1

Type RM Length L Ch R = 1 ,33.013  ,13,13,13
#Sta/Elev= 14
   -12.1   33.76    -2.1   33.76     -.7   34.56       0   34.56      .7   34.06
      .9   34.06     2.4   32.76     5.9   32.76     7.4   34.16     7.6   34.16
     8.8   35.26    11.2   35.26    12.3   34.26    22.3   34.26
#Mann= 3 , 0 , 0
   -12.1    .033       0       0    .033       0     8.8    .033       0
Bank Sta=0,8.8
XS Rating Curve= 0
Exp/Cntr=.3,.1

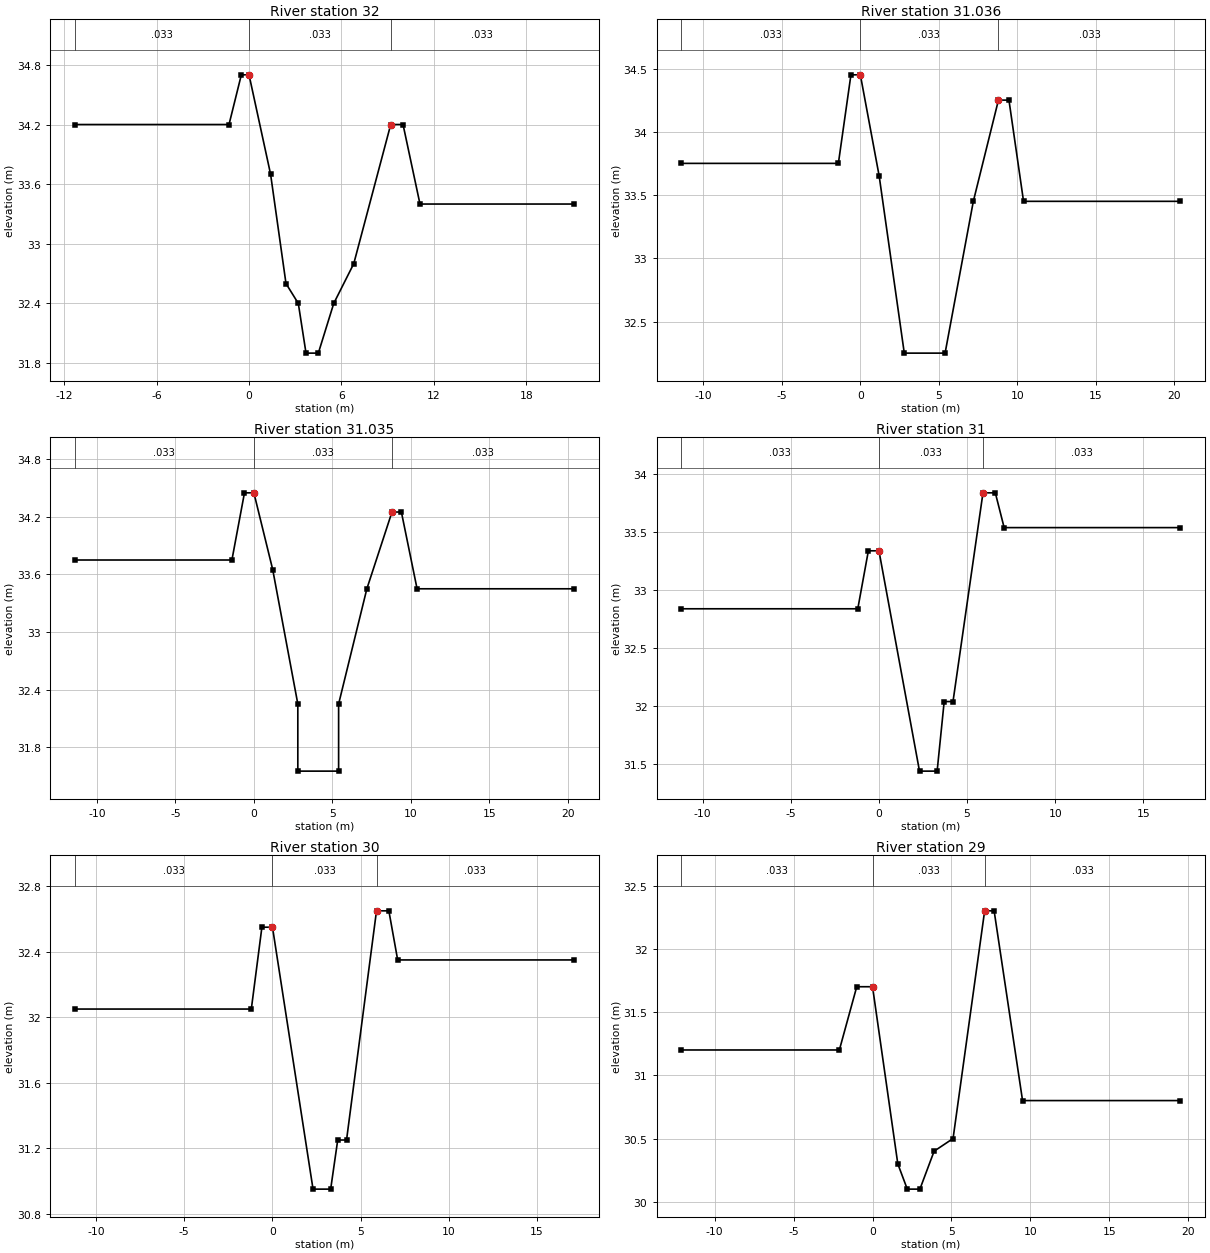
Type RM Length L Ch R = 1 ,32      ,14,14,14
#Sta/Elev= 15
   -11.3    34.2    -1.3    34.2     -.5    34.7       0    34.7     1.4    33.7
     2.4    32.6     3.2    32.4     3.7    31.9     4.5    31.9     5.5    32.4
     6.8    32.8     9.2    34.2      10    34.2    11.1    33.4    21.1    33.4
#Mann= 3 , 0 , 0
   -11.3    .033       0       0    .033       0     9.2    .033       0
Bank Sta=0,9.2
XS Rating Curve= 0
Exp/Cntr=.3,.1

Type RM Length L Ch R = 1 ,31.036  ,1,1,1
#Sta/Elev= 12
   -11.4   33.75    -1.4   33.75     -.6   34.45       0   34.45     1.2   33.65
     2.8   32.25     5.4   32.25     7.2   33.45     8.8   34.25    9.47   34.25
    10.4   33.45    20.4   33.45
#Mann= 3 , 0 , 0
   -11.4    .033       0       0    .033       0     8.8    .033       0
Bank Sta=0,8.8
XS Rating Curve= 0
Exp/Cntr=.3,.1

Type RM Length L Ch R = 1 ,31.035  ,35,35,35
#Sta/Elev= 14
   -11.4   33.75    -1.4   33.75     -.6   34.45       0   34.45     1.2   33.65
     2.8   32.25     2.8   31.55     5.4   31.55     5.4   32.25     7.2   33.45
     8.8   34.25     9.4   34.25    10.4   33.45    20.4   33.45
#Mann= 3 , 0 , 0
   -11.4    .033       0       0    .033       0     8.8    .033       0
Bank Sta=0,8.8
XS Rating Curve= 0
Exp/Cntr=.3,.1

Type RM Length L Ch R = 1 ,31      ,50,50,50
#Sta/Elev= 12
   -11.2   32.84    -1.2   32.84     -.6   33.34       0   33.34     2.3   31.44
     3.3   31.44     3.7   32.04     4.2   32.04     5.9   33.84     6.6   33.84
     7.1   33.54    17.1   33.54
#Mann= 3 , 0 , 0
   -11.2    .033       0       0    .033       0     5.9    .033       0
Bank Sta=0,5.9
XS Rating Curve= 0
Exp/Cntr=.3,.1

Type RM Length L Ch R = 1 ,30      ,50,50,50
#Sta/Elev= 12
   -11.2   32.05    -1.2   32.05     -.6   32.55       0   32.55     2.3   30.95
     3.3   30.95     3.7   31.25     4.2   31.25     5.9   32.65     6.6   32.65
     7.1   32.35    17.1   32.35
#Mann= 3 , 0 , 0
   -11.2    .033       0       0    .033       0     5.9    .033       0
Bank Sta=0,5.9
XS Rating Curve= 0
Exp/Cntr=.3,.1

Type RM Length L Ch R = 1 ,29      ,50,50,50
#Sta/Elev= 13
   -12.1    31.2    -2.1    31.2      -1    31.7       0    31.7     1.6    30.3
     2.2    30.1       3    30.1     3.9    30.4     5.1    30.5     7.1    32.3
     7.7    32.3     9.5    30.8    19.5    30.8
#Mann= 3 , 0 , 0
   -12.1    .033       0       0    .033       0     7.1    .033       0
Bank Sta=0,7.1
XS Rating Curve= 0
Exp/Cntr=.3,.1

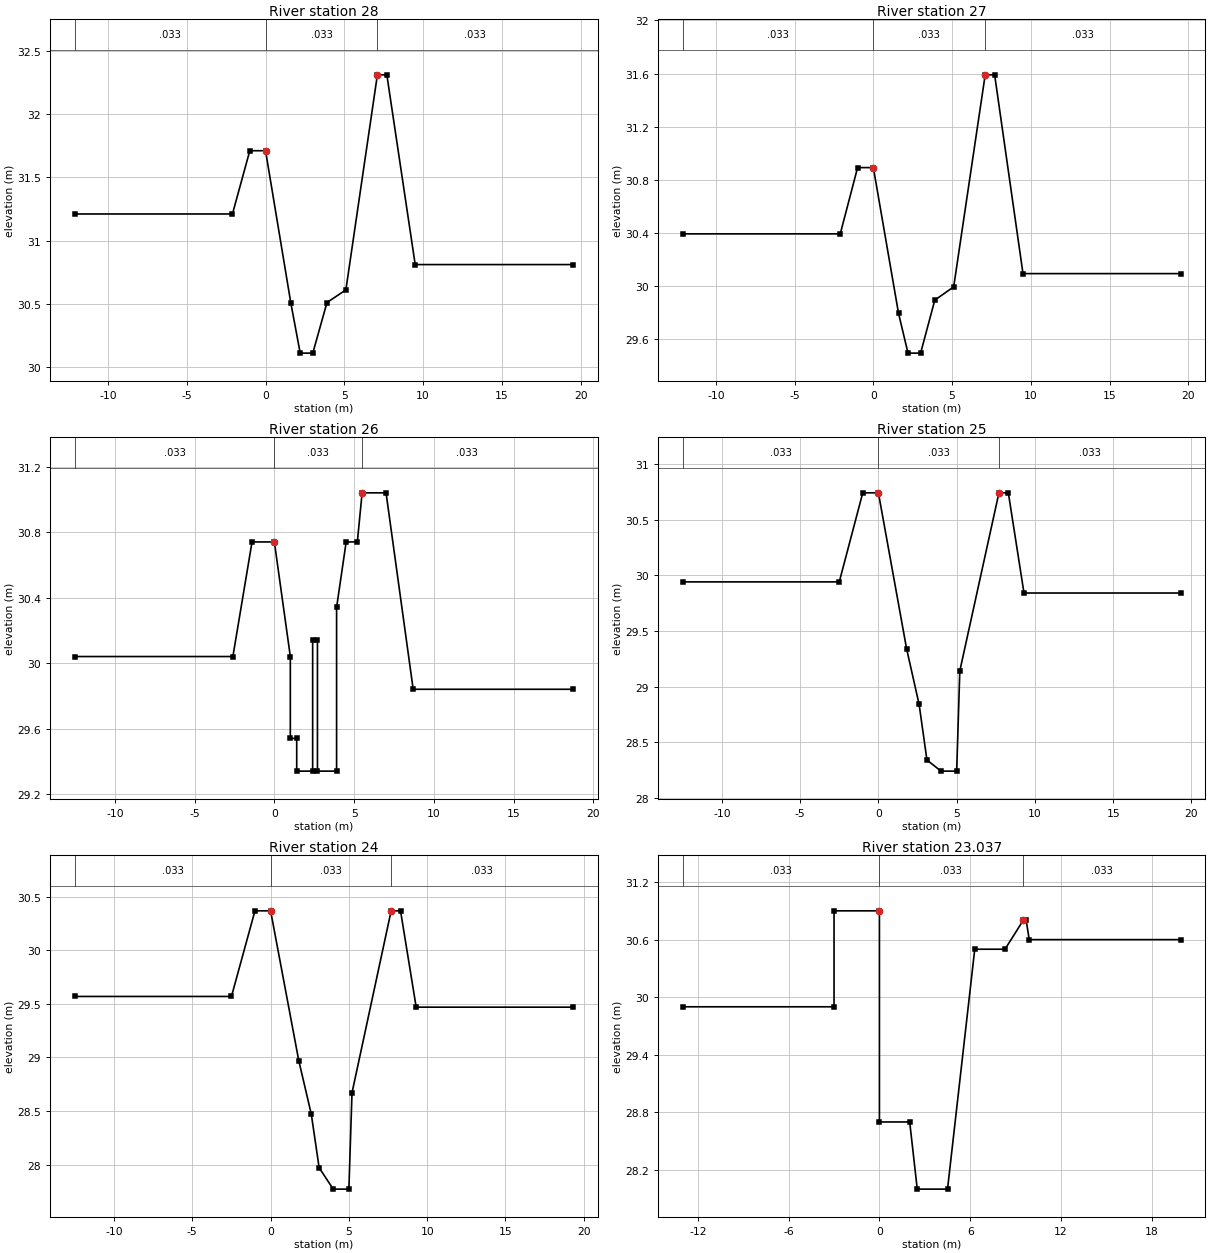
Type RM Length L Ch R = 1 ,28      ,50,50,50
#Sta/Elev= 13
   -12.1   31.21    -2.1   31.21      -1   31.71       0   31.71     1.6   30.51
     2.2   30.11       3   30.11     3.9   30.51     5.1   30.61     7.1   32.31
     7.7   32.31     9.5   30.81    19.5   30.81
#Mann= 3 , 0 , 0
   -12.1    .033       0       0    .033       0     7.1    .033       0
Bank Sta=0,7.1
XS Rating Curve= 0
Exp/Cntr=.3,.1

Type RM Length L Ch R = 1 ,27      ,50,50,50
#Sta/Elev= 13
   -12.1   30.39    -2.1   30.39      -1   30.89       0   30.89     1.6   29.79
     2.2   29.49       3   29.49     3.9   29.89     5.1   29.99     7.1   31.59
     7.7   31.59     9.5   30.09    19.5   30.09
#Mann= 3 , 0 , 0
   -12.1    .033       0       0    .033       0     7.1    .033       0
Bank Sta=0,7.1
XS Rating Curve= 0
Exp/Cntr=.3,.1

Type RM Length L Ch R = 1 ,26      ,50,50,50
#Sta/Elev= 20
   -12.5   30.04    -2.6   30.04    -1.4   30.74       0   30.74       1   30.04
       1   29.54     1.4   29.54     1.4   29.34     2.4   29.34     2.4   30.14
     2.7   30.14     2.7   29.34     3.9   29.34     3.9   30.34     4.5   30.74
     5.2   30.74     5.5   31.04       7   31.04     8.7   29.84    18.7   29.84
#Mann= 3 , 0 , 0
   -12.5    .033       0       0    .033       0     5.5    .033       0
Bank Sta=0,5.5
XS Rating Curve= 0
Exp/Cntr=.3,.1

Type RM Length L Ch R = 1 ,25      ,50,50,50
#Sta/Elev= 14
   -12.5   29.94    -2.5   29.94      -1   30.74       0   30.74     1.8   29.34
     2.6   28.84     3.1   28.34       4   28.24       5   28.24     5.2   29.14
     7.7   30.74     8.3   30.74     9.3   29.84    19.3   29.84
#Mann= 3 , 0 , 0
   -12.5    .033       0       0    .033       0     7.7    .033       0
Bank Sta=0,7.7
XS Rating Curve= 0
Exp/Cntr=.3,.1

Type RM Length L Ch R = 1 ,24      ,13,13,13
#Sta/Elev= 14
   -12.5   29.57    -2.5   29.57      -1   30.37       0   30.37     1.8   28.97
     2.6   28.47     3.1   27.97       4   27.77       5   27.77     5.2   28.67
     7.7   30.37     8.3   30.37     9.3   29.47    19.3   29.47
#Mann= 3 , 0 , 0
   -12.5    .033       0       0    .033       0     7.7    .033       0
Bank Sta=0,7.7
XS Rating Curve= 0
Exp/Cntr=.3,.1

Type RM Length L Ch R = 1 ,23.037  ,37,37,37
#Sta/Elev= 14
     -13    29.9      -3    29.9      -3    30.9       0    30.9       0    28.7
       2    28.7     2.5      28     4.5      28     6.3    30.5     8.3    30.5
     9.5    30.8     9.7    30.8     9.9    30.6    19.9    30.6
#Mann= 3 , 0 , 0
     -13    .033       0       0    .033       0     9.5    .033       0
Bank Sta=0,9.5
XS Rating Curve= 0
Exp/Cntr=.3,.1

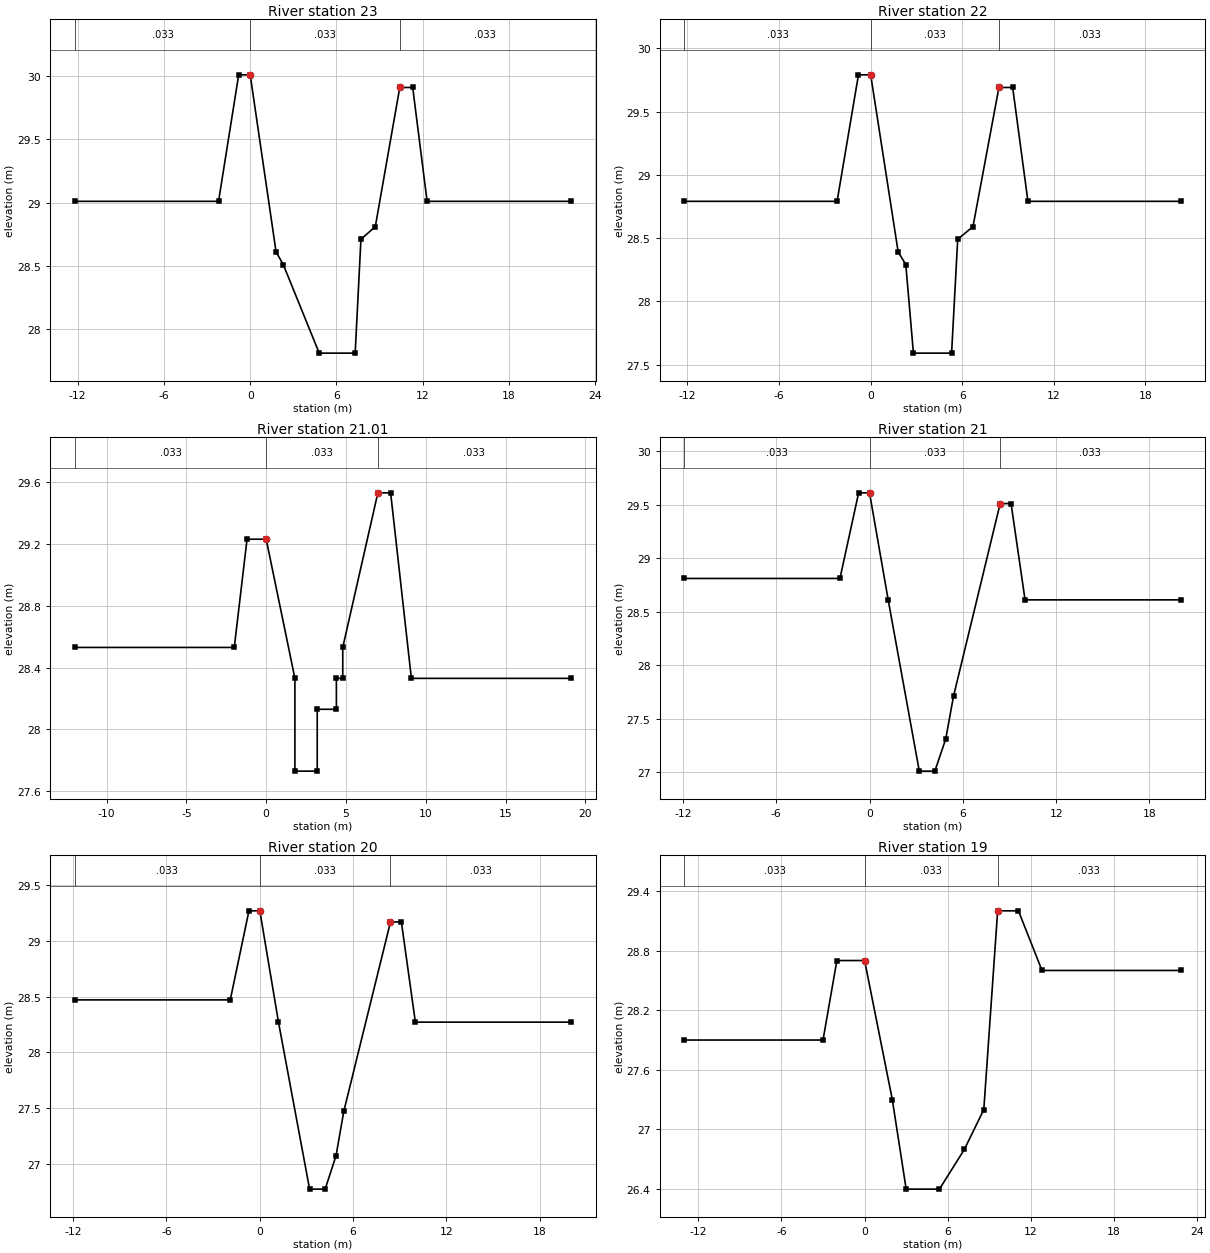
Type RM Length L Ch R = 1 ,23      ,50,50,50
#Sta/Elev= 14
   -12.2   29.01    -2.2   29.01     -.8   30.01       0   30.01     1.8   28.61
     2.3   28.51     4.8   27.81     7.3   27.81     7.7   28.71     8.7   28.81
    10.4   29.91    11.3   29.91    12.3   29.01    22.3   29.01
#Mann= 3 , 0 , 0
   -12.2    .033       0       0    .033       0    10.4    .033       0
Bank Sta=0,10.4
XS Rating Curve= 0
Exp/Cntr=.3,.1

Type RM Length L Ch R = 1 ,22      ,40,40,40
#Sta/Elev= 14
   -12.2   28.79    -2.2   28.79     -.8   29.79       0   29.79     1.8   28.39
     2.3   28.29     2.8   27.59     5.3   27.59     5.7   28.49     6.7   28.59
     8.4   29.69     9.3   29.69    10.3   28.79    20.3   28.79
#Mann= 3 , 0 , 0
   -12.2    .033       0       0    .033       0     8.4    .033       0
Bank Sta=0,8.4
XS Rating Curve= 0
Exp/Cntr=.3,.1

Type RM Length L Ch R = 1 ,21.01   ,10,10,10
#Sta/Elev= 16
     -12   28.53      -2   28.53    -1.2   29.23       0   29.23     1.8   28.33
     1.8   27.73     3.2   27.73     3.2   28.13     4.4   28.13     4.4   28.33
     4.8   28.33     4.8   28.53       7   29.53     7.8   29.53     9.1   28.33
    19.1   28.33
#Mann= 3 , 0 , 0
     -12    .033       0       0    .033       0       7    .033       0
Bank Sta=0,7
XS Rating Curve= 0
Exp/Cntr=.3,.1

Type RM Length L Ch R = 1 ,21      ,50,50,50
#Sta/Elev= 13
   -11.9   28.81    -1.9   28.81     -.7   29.61       0   29.61     1.2   28.61
     3.2   27.01     4.2   27.01     4.9   27.31     5.4   27.71     8.4   29.51
     9.1   29.51      10   28.61      20   28.61
#Mann= 3 , 0 , 0
   -11.9    .033       0       0    .033       0     8.4    .033       0
Bank Sta=0,8.4
XS Rating Curve= 0
Exp/Cntr=.3,.1

Type RM Length L Ch R = 1 ,20      ,50,50,50
#Sta/Elev= 13
   -11.9   28.47    -1.9   28.47     -.7   29.27       0   29.27     1.2   28.27
     3.2   26.77     4.2   26.77     4.9   27.07     5.4   27.47     8.4   29.17
     9.1   29.17      10   28.27      20   28.27
#Mann= 3 , 0 , 0
   -11.9    .033       0       0    .033       0     8.4    .033       0
Bank Sta=0,8.4
XS Rating Curve= 0
Exp/Cntr=.3,.1

Type RM Length L Ch R = 1 ,19      ,12,12,12
#Sta/Elev= 13
     -13    27.9      -3    27.9      -2    28.7       0    28.7       2    27.3
       3    26.4     5.4    26.4     7.2    26.8     8.6    27.2     9.6    29.2
    11.1    29.2    12.8    28.6    22.8    28.6
#Mann= 3 , 0 , 0
     -13    .033       0       0    .033       0     9.6    .033       0
Bank Sta=0,9.6
XS Rating Curve= 0
Exp/Cntr=.3,.1