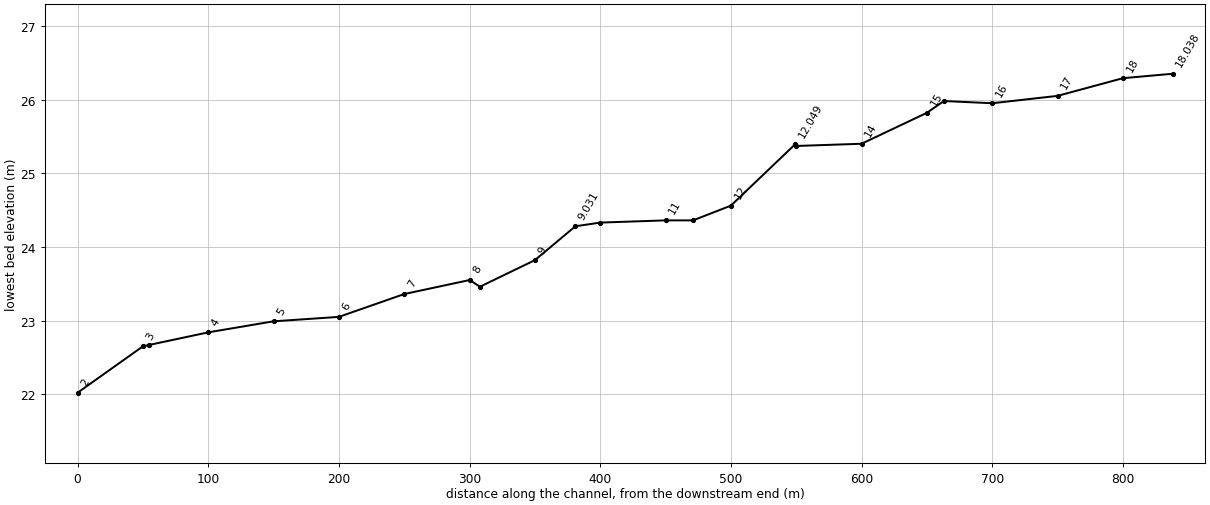
HEC-RAS study DONGSIL.prj: DONGSIL

--- DONGSIL.g01 (geometry) --- (continued)

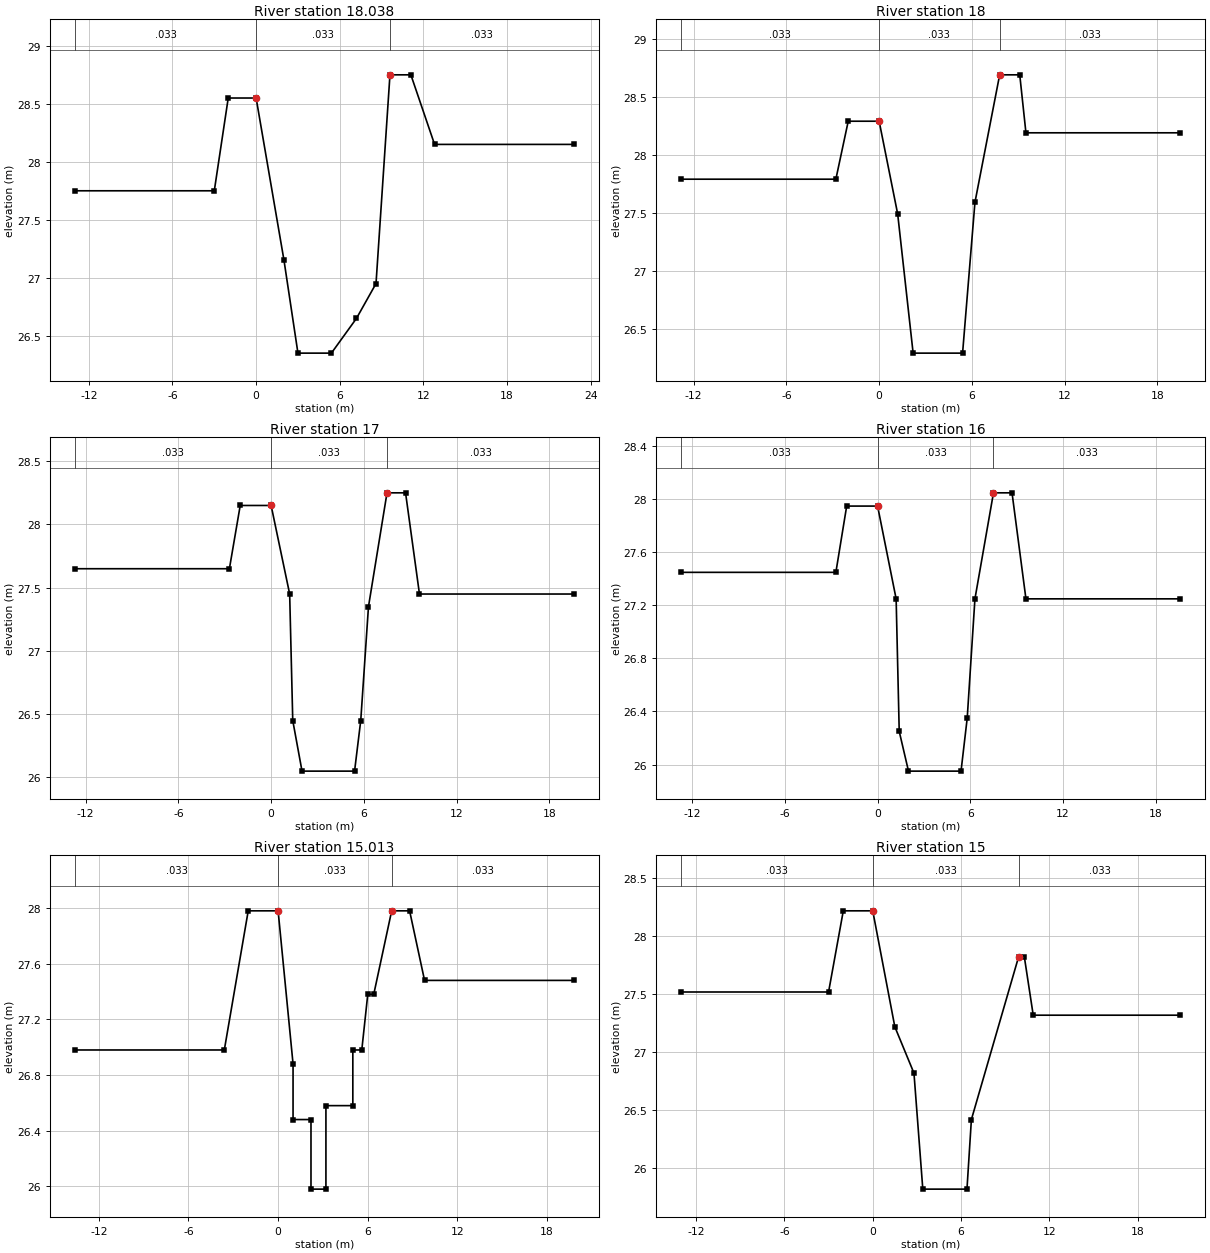
Type RM Length L Ch R = 1 ,18.038  ,38,38,38
#Sta/Elev= 13
     -13   27.75      -3   27.75      -2   28.55       0   28.55       2   27.15
       3   26.35     5.4   26.35     7.2   26.65     8.6   26.95     9.6   28.75
    11.1   28.75    12.8   28.15    22.8   28.15
#Mann= 3 , 0 , 0
     -13    .033       0       0    .033       0     9.6    .033       0
Bank Sta=0,9.6
XS Rating Curve= 0
Exp/Cntr=.3,.1

Type RM Length L Ch R = 1 ,18      ,50,50,50
#Sta/Elev= 12
   -12.8   27.79    -2.8   27.79      -2   28.29       0   28.29     1.2   27.49
     2.2   26.29     5.4   26.29     6.2   27.59     7.8   28.69     9.1   28.69
     9.5   28.19    19.5   28.19
#Mann= 3 , 0 , 0
   -12.8    .033       0       0    .033       0     7.8    .033       0
Bank Sta=0,7.8
XS Rating Curve= 0
Exp/Cntr=.3,.1

Type RM Length L Ch R = 1 ,17      ,50,50,50
#Sta/Elev= 14
   -12.7   27.65    -2.7   27.65      -2   28.15       0   28.15     1.2   27.45
     1.4   26.45       2   26.05     5.4   26.05     5.8   26.45     6.3   27.35
     7.5   28.25     8.7   28.25     9.6   27.45    19.6   27.45
#Mann= 3 , 0 , 0
   -12.7    .033       0       0    .033       0     7.5    .033       0
Bank Sta=0,7.5
XS Rating Curve= 0
Exp/Cntr=.3,.1

Type RM Length L Ch R = 1 ,16      ,37,37,37
#Sta/Elev= 14
   -12.7   27.45    -2.7   27.45      -2   27.95       0   27.95     1.2   27.25
     1.4   26.25       2   25.95     5.4   25.95     5.8   26.35     6.3   27.25
     7.5   28.05     8.7   28.05     9.6   27.25    19.6   27.25
#Mann= 3 , 0 , 0
   -12.7    .033       0       0    .033       0     7.5    .033       0
Bank Sta=0,7.5
XS Rating Curve= 0
Exp/Cntr=.3,.1

Type RM Length L Ch R = 1 ,15.013  ,13,13,13
#Sta/Elev= 19
   -13.6   26.98    -3.6   26.98      -2   27.98       0   27.98       1   26.88
       1   26.48     2.2   26.48     2.2   25.98     3.2   25.98     3.2   26.58
       5   26.58       5   26.98     5.6   26.98       6   27.38     6.4   27.38
     7.6   27.98     8.8   27.98     9.8   27.48    19.8   27.48
#Mann= 3 , 0 , 0
   -13.6    .033       0       0    .033       0     7.6    .033       0
Bank Sta=0,7.6
XS Rating Curve= 0
Exp/Cntr=.3,.1

Type RM Length L Ch R = 1 ,15      ,50,50,50
#Sta/Elev= 13
     -13   27.52      -3   27.52      -2   28.22       0   28.22     1.5   27.22
     2.8   26.82     3.4   25.82     6.4   25.82     6.7   26.42     9.9   27.82
    10.3   27.82    10.9   27.32    20.9   27.32
#Mann= 3 , 0 , 0
     -13    .033       0       0    .033       0     9.9    .033       0
Bank Sta=0,9.9
XS Rating Curve= 0
Exp/Cntr=.3,.1

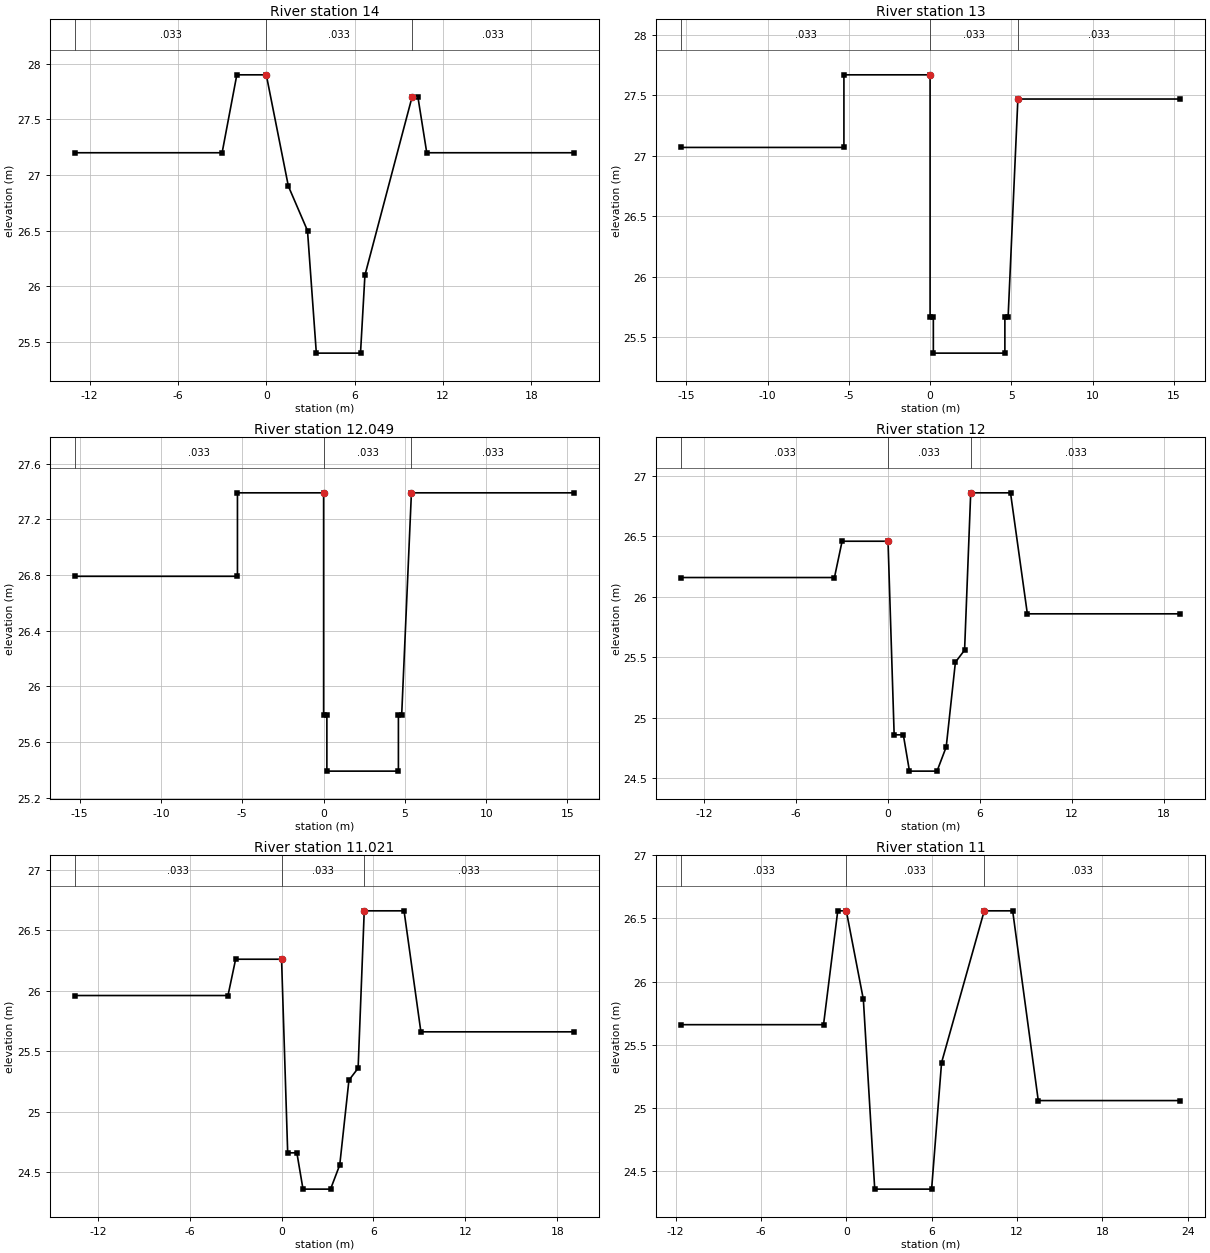
Type RM Length L Ch R = 1 ,14      ,50,50,50
#Sta/Elev= 13
     -13    27.2      -3    27.2      -2    27.9       0    27.9     1.5    26.9
     2.8    26.5     3.4    25.4     6.4    25.4     6.7    26.1     9.9    27.7
    10.3    27.7    10.9    27.2    20.9    27.2
#Mann= 3 , 0 , 0
     -13    .033       0       0    .033       0     9.9    .033       0
Bank Sta=0,9.9
XS Rating Curve= 0
Exp/Cntr=.3,.1

Type RM Length L Ch R = 1 ,13      ,1,1,1
#Sta/Elev= 12
   -15.3   27.07    -5.3   27.07    -5.3   27.67       0   27.67       0   25.67
      .2   25.67      .2   25.37     4.6   25.37     4.6   25.67     4.8   25.67
     5.4   27.47    15.4   27.47
#Mann= 3 , 0 , 0
   -15.3    .033       0       0    .033       0     5.4    .033       0
Bank Sta=0,5.4
XS Rating Curve= 0
Exp/Cntr=.3,.1

Type RM Length L Ch R = 1 ,12.049  ,49,49,49
#Sta/Elev= 12
   -15.3   26.79    -5.3   26.79    -5.3   27.39       0   27.39       0   25.79
      .2   25.79      .2   25.39     4.6   25.39     4.6   25.79     4.8   25.79
     5.4   27.39    15.4   27.39
#Mann= 3 , 0 , 0
   -15.3    .033       0       0    .033       0     5.4    .033       0
Bank Sta=0,5.4
XS Rating Curve= 0
Exp/Cntr=.3,.1

Type RM Length L Ch R = 1 ,12      ,29,29,29
#Sta/Elev= 15
   -13.5   26.16    -3.5   26.16      -3   26.46       0   26.46      .4   24.86
       1   24.86     1.4   24.56     3.2   24.56     3.8   24.76     4.4   25.46
       5   25.56     5.4   26.86       8   26.86     9.1   25.86    19.1   25.86
#Mann= 3 , 0 , 0
   -13.5    .033       0       0    .033       0     5.4    .033       0
Bank Sta=0,5.4
XS Rating Curve= 0
Exp/Cntr=.3,.1

Type RM Length L Ch R = 1 ,11.021  ,21,21,21
#Sta/Elev= 15
   -13.5   25.96    -3.5   25.96      -3   26.26       0   26.26      .4   24.66
       1   24.66     1.4   24.36     3.2   24.36     3.8   24.56     4.4   25.26
       5   25.36     5.4   26.66       8   26.66     9.1   25.66    19.1   25.66
#Mann= 3 , 0 , 0
   -13.5    .033       0       0    .033       0     5.4    .033       0
Bank Sta=0,5.4
XS Rating Curve= 0
Exp/Cntr=.3,.1

Type RM Length L Ch R = 1 ,11      ,50,50,50
#Sta/Elev= 12
   -11.6   25.66    -1.6   25.66     -.6   26.56       0   26.56     1.2   25.86
       2   24.36       6   24.36     6.7   25.36     9.7   26.56    11.7   26.56
    13.5   25.06    23.5   25.06
#Mann= 3 , 0 , 0
   -11.6    .033       0       0    .033       0     9.7    .033       0
Bank Sta=0,9.7
XS Rating Curve= 0
Exp/Cntr=.3,.1

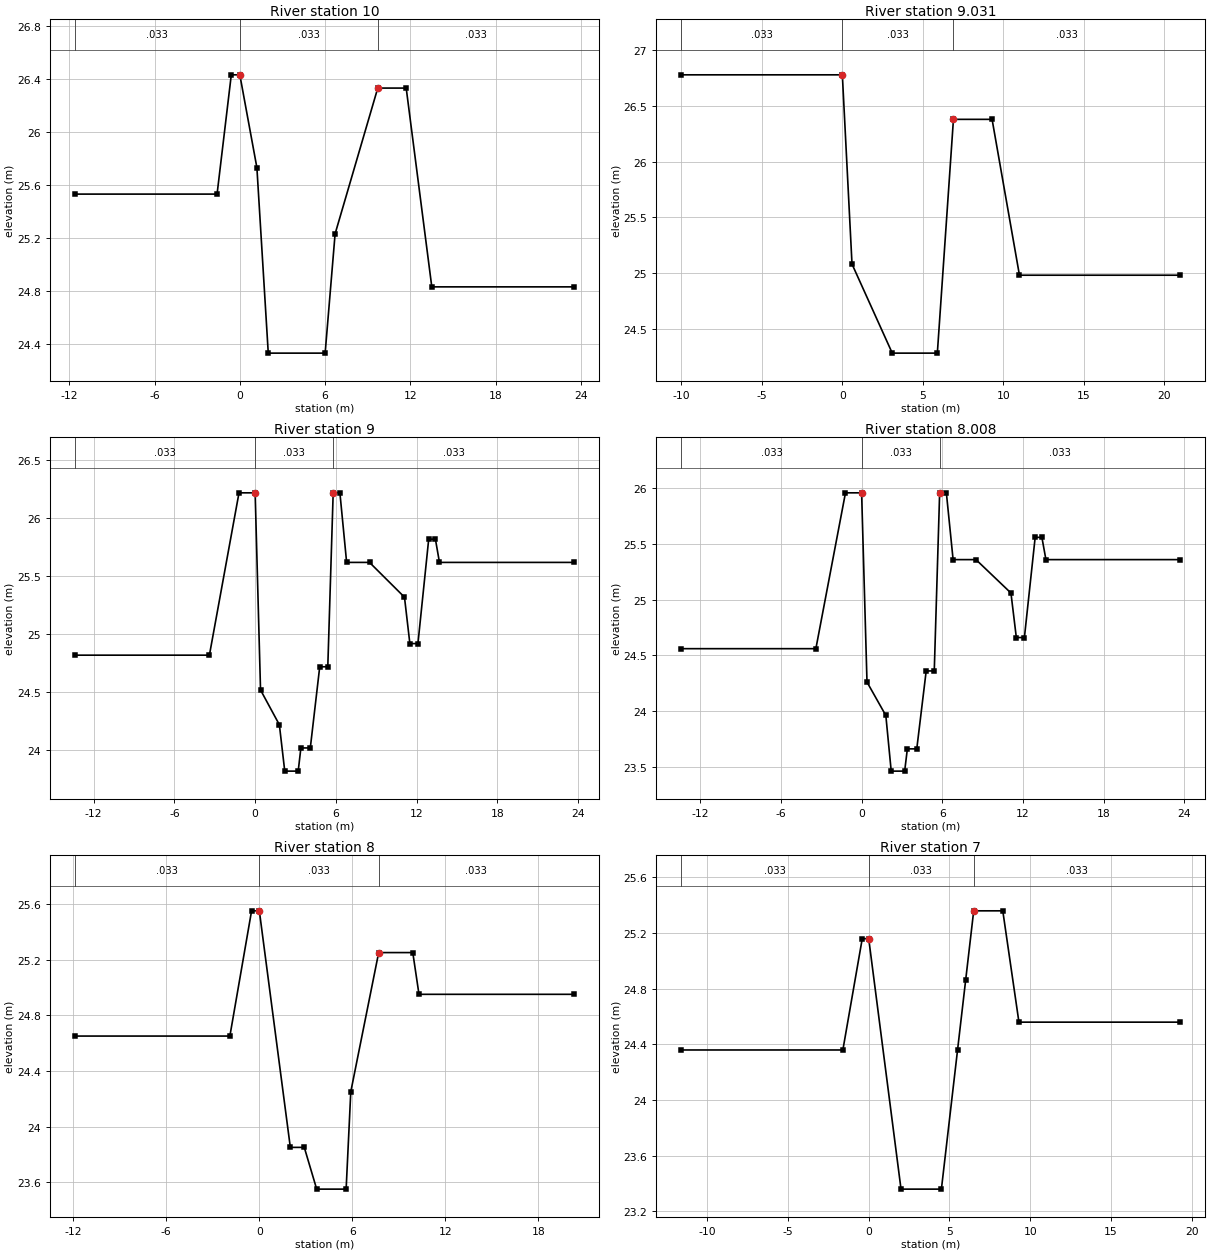
Type RM Length L Ch R = 1 ,10      ,19,19,19
#Sta/Elev= 12
   -11.6   25.53    -1.6   25.53     -.6   26.43       0   26.43     1.2   25.73
       2   24.33       6   24.33     6.7   25.23     9.7   26.33    11.7   26.33
    13.5   24.83    23.5   24.83
#Mann= 3 , 0 , 0
   -11.6    .033       0       0    .033       0     9.7    .033       0
Bank Sta=0,9.7
XS Rating Curve= 0
Exp/Cntr=.3,.1

Type RM Length L Ch R = 1 ,9.031   ,31,31,31
#Sta/Elev= 9
     -10   26.78       0   26.78      .6   25.08     3.1   24.28     5.9   24.28
     6.9   26.38     9.3   26.38      11   24.98      21   24.98
#Mann= 3 , 0 , 0
     -10    .033       0       0    .033       0     6.9    .033       0
Bank Sta=0,6.9
XS Rating Curve= 0
Exp/Cntr=.3,.1

Type RM Length L Ch R = 1 ,9       ,42,42,42
#Sta/Elev= 23
   -13.4   24.82    -3.4   24.82    -1.2   26.22       0   26.22      .4   24.52
     1.8   24.22     2.2   23.82     3.2   23.82     3.4   24.02     4.1   24.02
     4.8   24.72     5.4   24.72     5.8   26.22     6.3   26.22     6.8   25.62
     8.5   25.62    11.1   25.32    11.5   24.92    12.1   24.92    12.9   25.82
    13.4   25.82    13.7   25.62    23.7   25.62
#Mann= 3 , 0 , 0
   -13.4    .033       0       0    .033       0     5.8    .033       0
Bank Sta=0,5.8
XS Rating Curve= 0
Exp/Cntr=.3,.1

Type RM Length L Ch R = 1 ,8.008   ,8,8,8
#Sta/Elev= 23
   -13.4   24.56    -3.4   24.56    -1.2   25.96       0   25.96      .4   24.26
     1.8   23.96     2.2   23.46     3.2   23.46     3.4   23.66     4.1   23.66
     4.8   24.36     5.4   24.36     5.8   25.96     6.3   25.96     6.8   25.36
     8.5   25.36    11.1   25.06    11.5   24.66    12.1   24.66    12.9   25.56
    13.4   25.56    13.7   25.36    23.7   25.36
#Mann= 3 , 0 , 0
   -13.4    .033       0       0    .033       0     5.8    .033       0
Bank Sta=0,5.8
XS Rating Curve= 0
Exp/Cntr=.3,.1

Type RM Length L Ch R = 1 ,8       ,50,50,50
#Sta/Elev= 13
   -11.9   24.65    -1.9   24.65     -.5   25.55       0   25.55       2   23.85
     2.9   23.85     3.7   23.55     5.6   23.55     5.9   24.25     7.7   25.25
     9.9   25.25    10.3   24.95    20.3   24.95
#Mann= 3 , 0 , 0
   -11.9    .033       0       0    .033       0     7.7    .033       0
Bank Sta=0,7.7
XS Rating Curve= 0
Exp/Cntr=.3,.1

Type RM Length L Ch R = 1 ,7       ,50,50,50
#Sta/Elev= 12
   -11.6   24.36    -1.6   24.36     -.4   25.16       0   25.16       2   23.36
     4.5   23.36     5.5   24.36       6   24.86     6.5   25.36     8.3   25.36
     9.3   24.56    19.3   24.56
#Mann= 3 , 0 , 0
   -11.6    .033       0       0    .033       0     6.5    .033       0
Bank Sta=0,6.5
XS Rating Curve= 0
Exp/Cntr=.3,.1

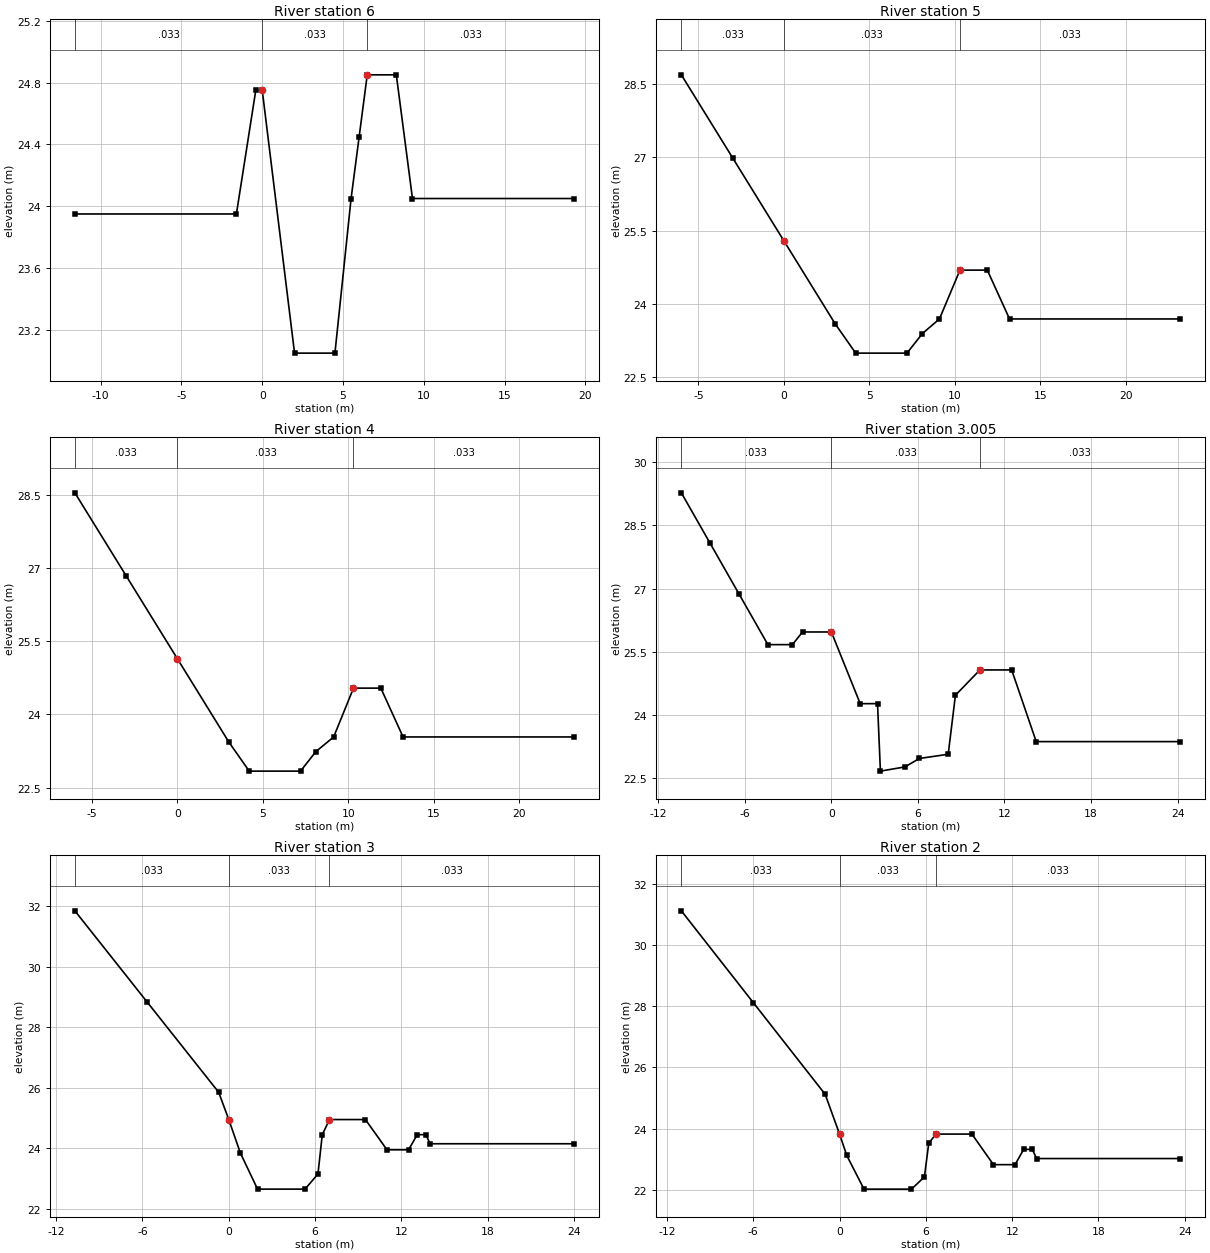
Type RM Length L Ch R = 1 ,6       ,50,50,50
#Sta/Elev= 12
   -11.6   23.95    -1.6   23.95     -.4   24.75       0   24.75       2   23.05
     4.5   23.05     5.5   24.05       6   24.45     6.5   24.85     8.3   24.85
     9.3   24.05    19.3   24.05
#Mann= 3 , 0 , 0
   -11.6    .033       0       0    .033       0     6.5    .033       0
Bank Sta=0,6.5
XS Rating Curve= 0
Exp/Cntr=.3,.1

Type RM Length L Ch R = 1 ,5       ,50,50,50
#Sta/Elev= 12
      -6   28.69      -3   26.99       0   25.29       3   23.59     4.2   22.99
     7.2   22.99     8.1   23.39     9.1   23.69    10.3   24.69    11.9   24.69
    13.2   23.69    23.2   23.69
#Mann= 3 , 0 , 0
      -6    .033       0       0    .033       0    10.3    .033       0
Bank Sta=0,10.3
XS Rating Curve= 0
Exp/Cntr=.3,.1

Type RM Length L Ch R = 1 ,4       ,45,45,45
#Sta/Elev= 12
      -6   28.54      -3   26.84       0   25.14       3   23.44     4.2   22.84
     7.2   22.84     8.1   23.24    9.14   23.54    10.3   24.54    11.9   24.54
    13.2   23.54    23.2   23.54
#Mann= 3 , 0 , 0
      -6    .033       0       0    .033       0    10.3    .033       0
Bank Sta=0,10.3
XS Rating Curve= 0
Exp/Cntr=.3,.1

Type RM Length L Ch R = 1 ,3.005   ,5,5,5
#Sta/Elev= 18
   -10.4   29.27    -8.4   28.07    -6.4   26.87    -4.4   25.67    -2.7   25.67
      -2   25.97       0   25.97       2   24.27     3.2   24.27     3.4   22.67
     5.1   22.77     6.1   22.97     8.1   23.07     8.6   24.47    10.3   25.07
    12.5   25.07    14.2   23.37    24.2   23.37
#Mann= 3 , 0 , 0
   -10.4    .033       0       0    .033       0    10.3    .033       0
Bank Sta=0,10.3
XS Rating Curve= 0
Exp/Cntr=.3,.1

Type RM Length L Ch R = 1 ,3       ,50,50,50
#Sta/Elev= 17
   -10.7   31.85    -5.7   28.85     -.7   25.85       0   24.95      .8   23.85
       2   22.65     5.3   22.65     6.2   23.15     6.5   24.45       7   24.95
     9.5   24.95      11   23.95    12.5   23.95    13.1   24.45    13.7   24.45
      14   24.15      24   24.15
#Mann= 3 , 0 , 0
   -10.7    .033       0       0    .033       0       7    .033       0
Bank Sta=0,7
XS Rating Curve= 0
Exp/Cntr=.3,.1

Type RM Length L Ch R = 1 ,2       ,50,50,50
#Sta/Elev= 17
     -11   31.12      -6   28.12      -1   25.12       0   23.82      .5   23.12
     1.7   22.02       5   22.02     5.9   22.42     6.2   23.52     6.7   23.82
     9.2   23.82    10.7   22.82    12.2   22.82    12.8   23.32    13.4   23.32
    13.7   23.02    23.7   23.02
#Mann= 3 , 0 , 0
     -11    .033       0       0    .033       0     6.7    .033       0
Bank Sta=0,6.7
XS Rating Curve= 0
Exp/Cntr=.3,.1