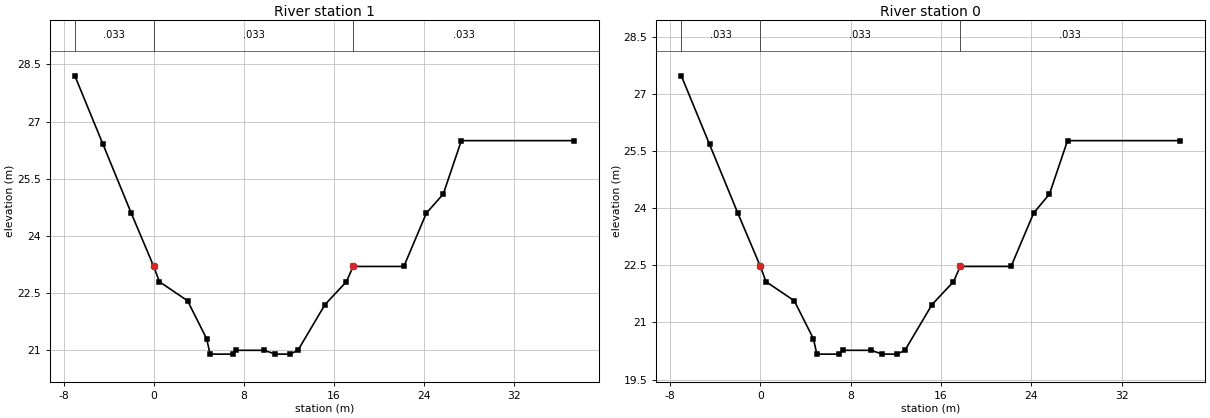
HEC-RAS study DONGSIL.prj: DONGSIL

--- DONGSIL.g01 (geometry) --- (continued)

Type RM Length L Ch R = 1 ,1       ,50,50,50
#Sta/Elev= 22
      -7    28.2    -4.5    26.4      -2    24.6       0    23.2      .5    22.8
       3    22.3     4.7    21.3       5    20.9       7    20.9     7.3      21
     9.8      21    10.8    20.9    12.1    20.9    12.8      21    15.2    22.2
    17.1    22.8    17.7    23.2    22.2    23.2    24.2    24.6    25.7    25.1
    27.3    26.5    37.3    26.5
#Mann= 3 , 0 , 0
      -7    .033       0       0    .033       0    17.7    .033       0
Bank Sta=0,17.7
XS Rating Curve= 0
Exp/Cntr=.3,.1

Type RM Length L Ch R = 1 ,0       ,0,0,0
#Sta/Elev= 22
      -7   27.47    -4.5   25.67      -2   23.87       0   22.47      .5   22.07
       3   21.57     4.7   20.57       5   20.17       7   20.17     7.3   20.27
     9.8   20.27    10.8   20.17    12.1   20.17    12.8   20.27    15.2   21.47
    17.1   22.07    17.7   22.47    22.2   22.47    24.2   23.87    25.6   24.37
    27.2   25.77    37.2   25.77
#Mann= 3 , 0 , 0
      -7    .033       0       0    .033       0    17.7    .033       0
Bank Sta=0,17.7
XS Rating Curve= 0
Exp/Cntr=.3,.1

Chan Stop Cuts=-1