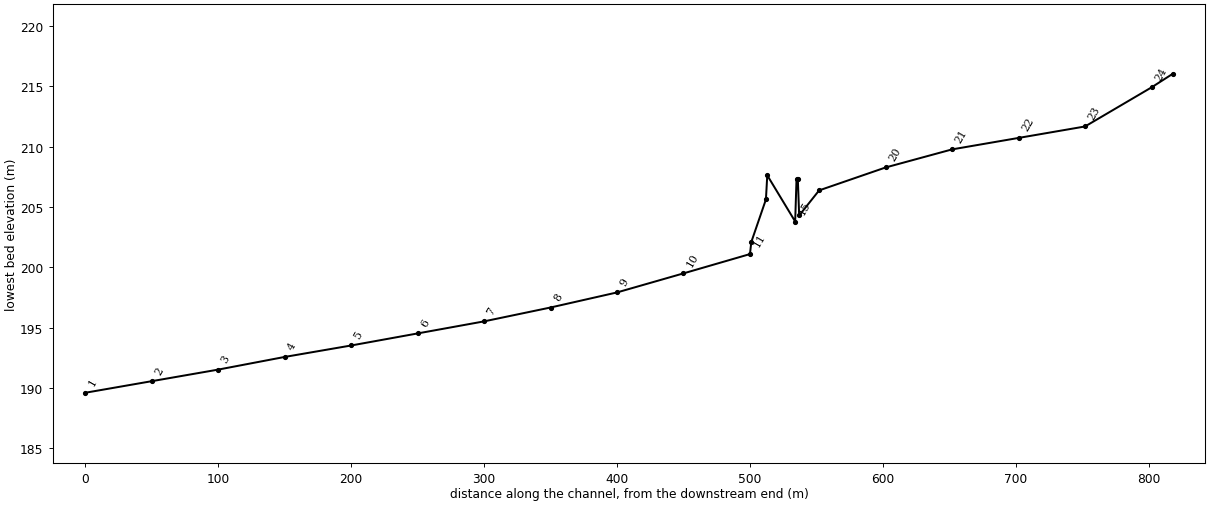
--- makwoon-ch.prj (project) ---

Proj Title=makwoon-ch
Current Plan=p01
Default Exp/Contr=.3,.1
SI Units
Geom File=g01
Flow File=f01
Plan File=p01
Y Axis Title=Elevation
X Axis Title(PF)=Main Channel Distance
X Axis Title(XS)=Station
BEGIN DESCRIPTION:
           BACK WATER COMPUTATION
      APPLICATION OF HEC-2 BY Samju Construction Engineering
      makwoon-ch: 10,20,30,50,80 yr
END DESCRIPTION:
DSS Export Rating Curves= 0
DSS Export Rating Curve Sorted= 0
DSS Export Volume Flow Curves= 0
DXF OffsetX= 0
DXF OffsetY= 0
DXF ScaleX= 1
DXF ScaleY= 10

--- makwoon-ch.p01 (plan) ---

Plan Title=Imported Plan 01
Version=Version 3.0.1  Mar 2001
Short Identifier=Imported Pla
Geom File=g01
Flow File=f01
Subcritical Flow
K Sum by GR= 0
Std Step Tol= 0.003
Critical Tol= 0.003
Num of Std Step Trials= 20
Max Error Tol= 0.1
Flow Tol Ratio= 0.001
Split Flow NTrial= 30
Split Flow Tol= 0.02
Split Flow Ratio= 0.02
Log Output Level= 0
Friction Slope Method= 1
Unsteady Friction Slope Method= 2
Parabolic Critical Depth
Global Vel Dist= 0 , 0 , 0
Global Log Level= 0
CheckData=True
Encroach Param=-1 ,0,0, 0
Computation Interval=1HOUR
Output Interval=1HOUR
Run HTab= 0
Run UNet= 0
Run PostProcess= 0
UNET Theta= 1
UNET ZTol= 0.02
UNET ZSATol= 0.1
UNET MxIter= 20
UNET MaxInSteps= 20
UNET DtIC= 0
UNET DtMin= 0
UNET MaxCRTS= 20
UNET WFStab= 2
UNET SFStab= 1
UNET WFX= 1
UNET SFX= 1
UNET Convert EG Bridges=-1
UNET Use Existing IB Tables=-1
Instantaneous Interval=1HOUR
Write IC File= 0
Write Velocity= 0
Write Detailed= 0

--- makwoon-ch.f01 (steady flow) ---

Flow Title=Imported Flow 01
Version=Version 3.0.1  Mar 2001
Number of Profiles= 5
Profile Names=PF 1,PF 2,PF 3,PF 4,PF 5
River Rch & RM=RIVER-1,Reach-1         ,25
     180     200     220     230     240
Boundary for River Rch & Prof#=RIVER-1,Reach-1         , 1
Up Type= 0
Dn Type= 3
Dn Slope=.0109
Boundary for River Rch & Prof#=RIVER-1,Reach-1         , 2
Up Type= 0
Dn Type= 3
Dn Slope=.0109
Boundary for River Rch & Prof#=RIVER-1,Reach-1         , 3
Up Type= 0
Dn Type= 3
Dn Slope=.0109
Boundary for River Rch & Prof#=RIVER-1,Reach-1         , 4
Up Type= 0
Dn Type= 3
Dn Slope=.0109
Boundary for River Rch & Prof#=RIVER-1,Reach-1         , 5
Up Type= 0
Dn Type= 3
Dn Slope=.0109
DSS Import GetInterval= 0
DSS Import GetPeak= 0
DSS Import FillOption= 0

--- makwoon-ch.g01 (geometry) ---

Geom Title=Imported Geom 01
Version=Version 3.0.1  Mar 2001

River Reach=RIVER-1         ,Reach-1
Reach XY= 2
              .5             .95              .5             .05

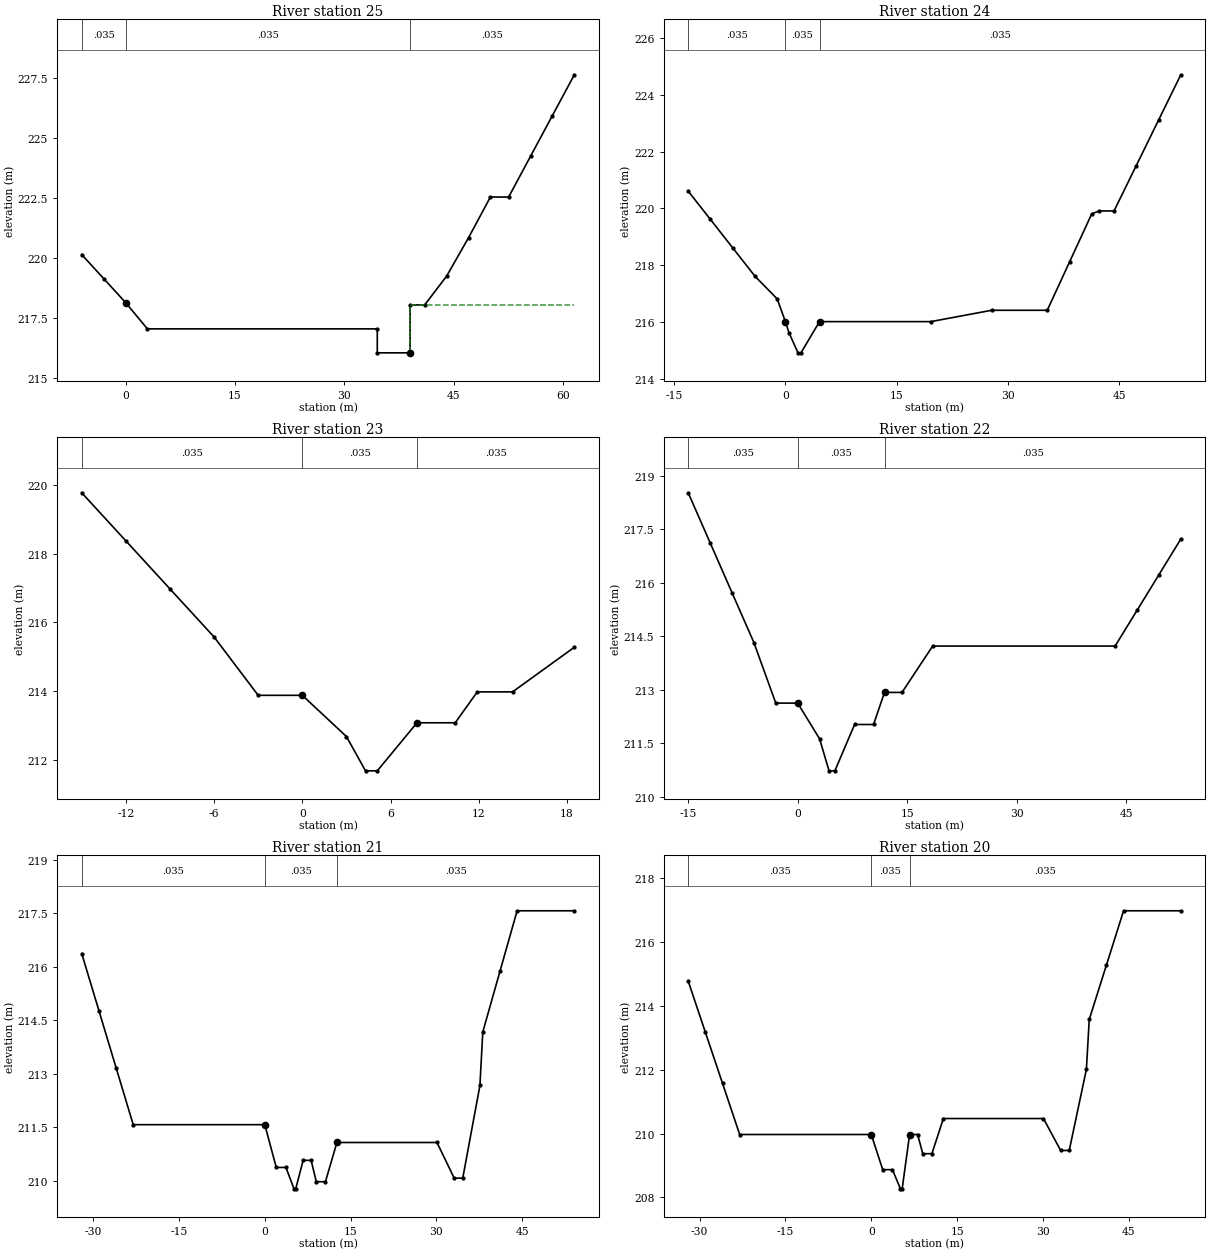
Type RM Length L Ch R = 1 ,25      ,16,16,16
BEGIN DESCRIPTION:
16.016
END DESCRIPTION:
#Sta/Elev= 16
      -6  220.14      -3  219.14       0  218.14       3  217.04    34.5  217.04
    34.5  216.04      39  216.04      39  218.04      41  218.04      44  219.24
      47  220.84      50  222.54    52.5  222.54    55.5  224.24    58.5  225.94
    61.5  227.64
#Mann= 3 , 0 , 0
      -6    .035       0       0    .035       0      39    .035       0
#XS Ineff= 2 , 0
               0  218.14      39          218.04
Permanent Ineff=
       F       F
Bank Sta=0,39
XS Rating Curve= 0
Exp/Cntr=.3,.1

Type RM Length L Ch R = 1 ,24      ,50,50,50
BEGIN DESCRIPTION:
16
END DESCRIPTION:
#Sta/Elev= 20
   -13.1  220.61   -10.1  219.61    -7.1  218.61    -4.1  217.61    -1.1  216.81
       0  216.01      .5  215.61     1.7  214.91     2.1  214.91     4.6  216.01
    19.6  216.01    27.8  216.41    35.3  216.41    38.3  218.11    41.3  219.81
    42.3  219.91    44.3  219.91    47.3  221.51    50.3  223.11    53.3  224.71
#Mann= 3 , 0 , 0
   -13.1    .035       0       0    .035       0     4.6    .035       0
#XS Ineff= 2 , 0
               0  216.01     4.6          216.01
Permanent Ineff=
       F       F
Bank Sta=0,4.6
XS Rating Curve= 0
Exp/Cntr=.3,.1

Type RM Length L Ch R = 1 ,23      ,50,50,50
BEGIN DESCRIPTION:
15
END DESCRIPTION:
#Sta/Elev= 14
     -15  219.77     -12  218.37      -9  216.97      -6  215.57      -3  213.87
       0  213.87       3  212.67     4.3  211.67     5.1  211.67     7.8  213.07
    10.4  213.07    11.9  213.97    14.3  213.97    18.5  215.27
#Mann= 3 , 0 , 0
     -15    .035       0       0    .035       0     7.8    .035       0
#XS Ineff= 2 , 0
               0  213.87     7.8          213.07
Permanent Ineff=
       F       F
Bank Sta=0,7.8
XS Rating Curve= 0
Exp/Cntr=.3,.1

Type RM Length L Ch R = 1 ,22      ,50,50,50
BEGIN DESCRIPTION:
14
END DESCRIPTION:
#Sta/Elev= 18
     -15  218.52     -12  217.12      -9  215.72      -6  214.32      -3  212.62
       0  212.62       3  211.62     4.3  210.72     5.1  210.72     7.8  212.02
    10.4  212.02    11.9  212.92    14.3  212.92    18.5  214.22    43.5  214.22
    46.5  215.22    49.5  216.22    52.5  217.22
#Mann= 3 , 0 , 0
     -15    .035       0       0    .035       0    11.9    .035       0
#XS Ineff= 2 , 0
               0  212.62    11.9          212.92
Permanent Ineff=
       F       F
Bank Sta=0,11.9
XS Rating Curve= 0
Exp/Cntr=.3,.1

Type RM Length L Ch R = 1 ,21      ,50,50,50
BEGIN DESCRIPTION:
13
END DESCRIPTION:
#Sta/Elev= 22
     -32  216.37     -29  214.77     -26  213.17     -23  211.57       0  211.57
       2  210.37     3.7  210.37     5.1  209.77     5.4  209.77     6.7  210.57
     8.1  210.57       9  209.97    10.6  209.97    12.6  211.07    30.1  211.07
    33.1  210.07    34.6  210.07    37.6  212.67    38.1  214.17    41.1  215.87
    44.1  217.57    54.1  217.57
#Mann= 3 , 0 , 0
     -32    .035       0       0    .035       0    12.6    .035       0
#XS Ineff= 2 , 0
               0  211.57    12.6          211.07
Permanent Ineff=
       F       F
Bank Sta=0,12.6
XS Rating Curve= 0
Exp/Cntr=.3,.1

Type RM Length L Ch R = 1 ,20      ,50,50,50
BEGIN DESCRIPTION:
12
END DESCRIPTION:
#Sta/Elev= 22
     -32  214.77     -29  213.17     -26  211.57     -23  209.97       0  209.97
       2  208.87     3.7  208.87     5.1  208.27     5.4  208.27     6.7  209.97
     8.1  209.97       9  209.37    10.6  209.37    12.6  210.47    30.1  210.47
    33.1  209.47    34.6  209.47    37.6 212.007    38.1  213.57    41.1  215.27
    44.1  216.97    54.1  216.97
#Mann= 3 , 0 , 0
     -32    .035       0       0    .035       0     6.7    .035       0
#XS Ineff= 2 , 0
               0  209.97     6.7          209.97
Permanent Ineff=
       F       F
Bank Sta=0,6.7
XS Rating Curve= 0
Exp/Cntr=.3,.1

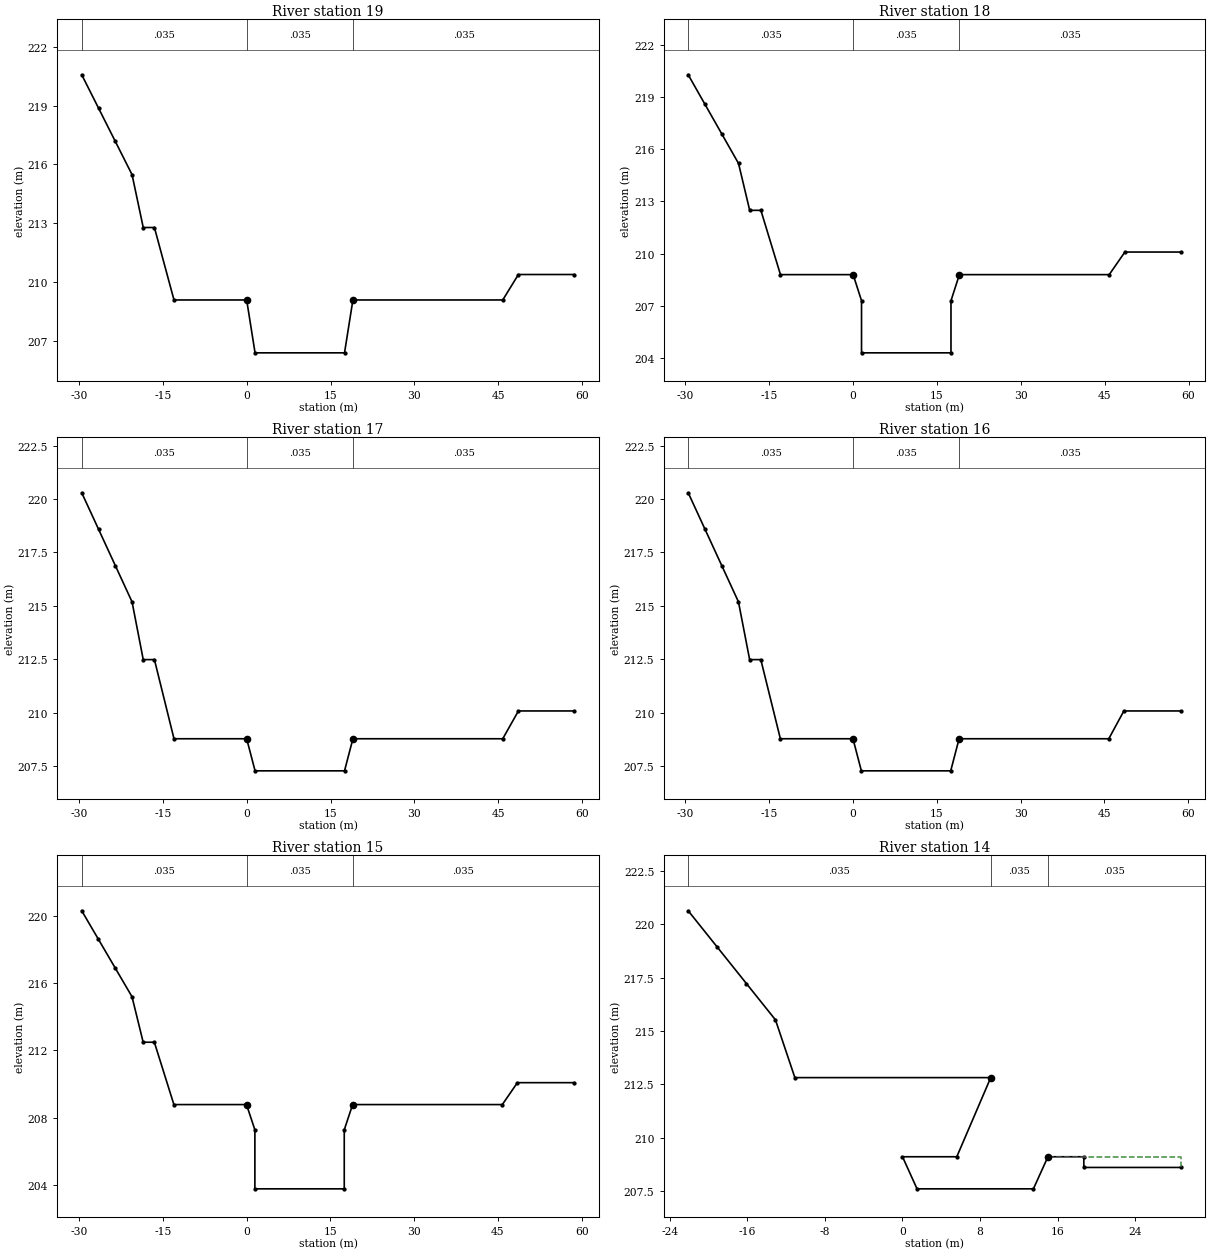
Type RM Length L Ch R = 1 ,19      ,15,15,15
BEGIN DESCRIPTION:
11
END DESCRIPTION:
#Sta/Elev= 14
   -29.5  220.57   -26.5  218.87   -23.5  217.17   -20.5  215.47   -18.5  212.77
   -16.5  212.77     -13  209.07       0  209.07     1.5  206.37    17.5  206.37
      19  209.07    45.8  209.07    48.6  210.37    58.6  210.37
#Mann= 3 , 0 , 0
   -29.5    .035       0       0    .035       0      19    .035       0
#XS Ineff= 2 , 0
               0  209.07      19          209.07
Permanent Ineff=
       F       F
Bank Sta=0,19
XS Rating Curve= 0
Exp/Cntr=.3,.1

Type RM Length L Ch R = 1 ,18      ,1,1,1
BEGIN DESCRIPTION:
10.036
END DESCRIPTION:
#Sta/Elev= 16
   -29.5  220.29   -26.5  218.59   -23.5  216.89   -20.5  215.19   -18.5  212.49
   -16.5  212.49     -13  208.79       0  208.79     1.5  207.29     1.5  204.29
    17.5  204.29    17.5  207.29      19  208.79    45.8  208.79    48.6  210.09
    58.6  210.09
#Mann= 3 , 0 , 0
   -29.5    .035       0       0    .035       0      19    .035       0
#XS Ineff= 2 , 0
               0  208.79      19          208.79
Permanent Ineff=
       F       F
Bank Sta=0,19
XS Rating Curve= 0
Exp/Cntr=.3,.1

Type RM Length L Ch R = 1 ,17      ,1,1,1
BEGIN DESCRIPTION:
10.035
END DESCRIPTION:
#Sta/Elev= 14
   -29.5  220.29   -26.5  218.59   -23.5  216.89   -20.5  215.19   -18.5  212.49
   -16.5  212.49     -13  208.79       0  208.79     1.5  207.29    17.5  207.29
      19  208.79    45.8  208.79    48.6  210.09    58.6  210.09
#Mann= 3 , 0 , 0
   -29.5    .035       0       0    .035       0      19    .035       0
#XS Ineff= 2 , 0
               0  208.79      19          208.79
Permanent Ineff=
       F       F
Bank Sta=0,19
XS Rating Curve= 0
Exp/Cntr=.3,.1

Type RM Length L Ch R = 1 ,16      ,1,1,1
BEGIN DESCRIPTION:
10.035
END DESCRIPTION:
#Sta/Elev= 14
   -29.5  220.29   -26.5  218.59   -23.5  216.89   -20.5  215.19   -18.5  212.49
   -16.5  212.49     -13  208.79       0  208.79     1.5  207.29    17.5  207.29
      19  208.79    45.8  208.79    48.5  210.09   58.69  210.09
#Mann= 3 , 0 , 0
   -29.5    .035       0       0    .035       0      19    .035       0
#XS Ineff= 2 , 0
               0  208.79      19          208.79
Permanent Ineff=
       F       F
Bank Sta=0,19
XS Rating Curve= 0
Exp/Cntr=.3,.1

Type RM Length L Ch R = 1 ,15      ,21,21,21
BEGIN DESCRIPTION:
10.034
END DESCRIPTION:
#Sta/Elev= 16
   -29.5  220.29   -26.5  218.59   -23.5  216.89   -20.5  215.19   -18.5  212.49
   -16.5  212.49     -13  208.79       0  208.79     1.5  207.29     1.5  203.79
    17.5  203.79    17.5  207.29      19  208.79    45.8  208.79    48.5  210.09
   58.69  210.09
#Mann= 3 , 0 , 0
   -29.5    .035       0       0    .035       0      19    .035       0
#XS Ineff= 2 , 0
               0  208.79      19          208.79
Permanent Ineff=
       F       F
Bank Sta=0,19
XS Rating Curve= 0
Exp/Cntr=.3,.1

Type RM Length L Ch R = 1 ,14      ,1,1,1
BEGIN DESCRIPTION:
10.013
END DESCRIPTION:
#Sta/Elev= 14
   -22.1  220.62   -19.1  218.92   -16.1  217.22   -13.1  215.52   -11.1  212.82
     9.1  212.82     5.6  209.12       0  209.12     1.5  207.62    13.5  207.62
      15  209.12    18.7  209.12    18.7  208.62    28.7  208.62
#Mann= 3 , 0 , 0
   -22.1    .035       0     9.1    .035       0      15    .035       0
#XS Ineff= 2 , 0
             9.1  212.82      15          209.12
Permanent Ineff=
       F       F
Bank Sta=9.1,15
XS Rating Curve= 0
Exp/Cntr=.3,.1

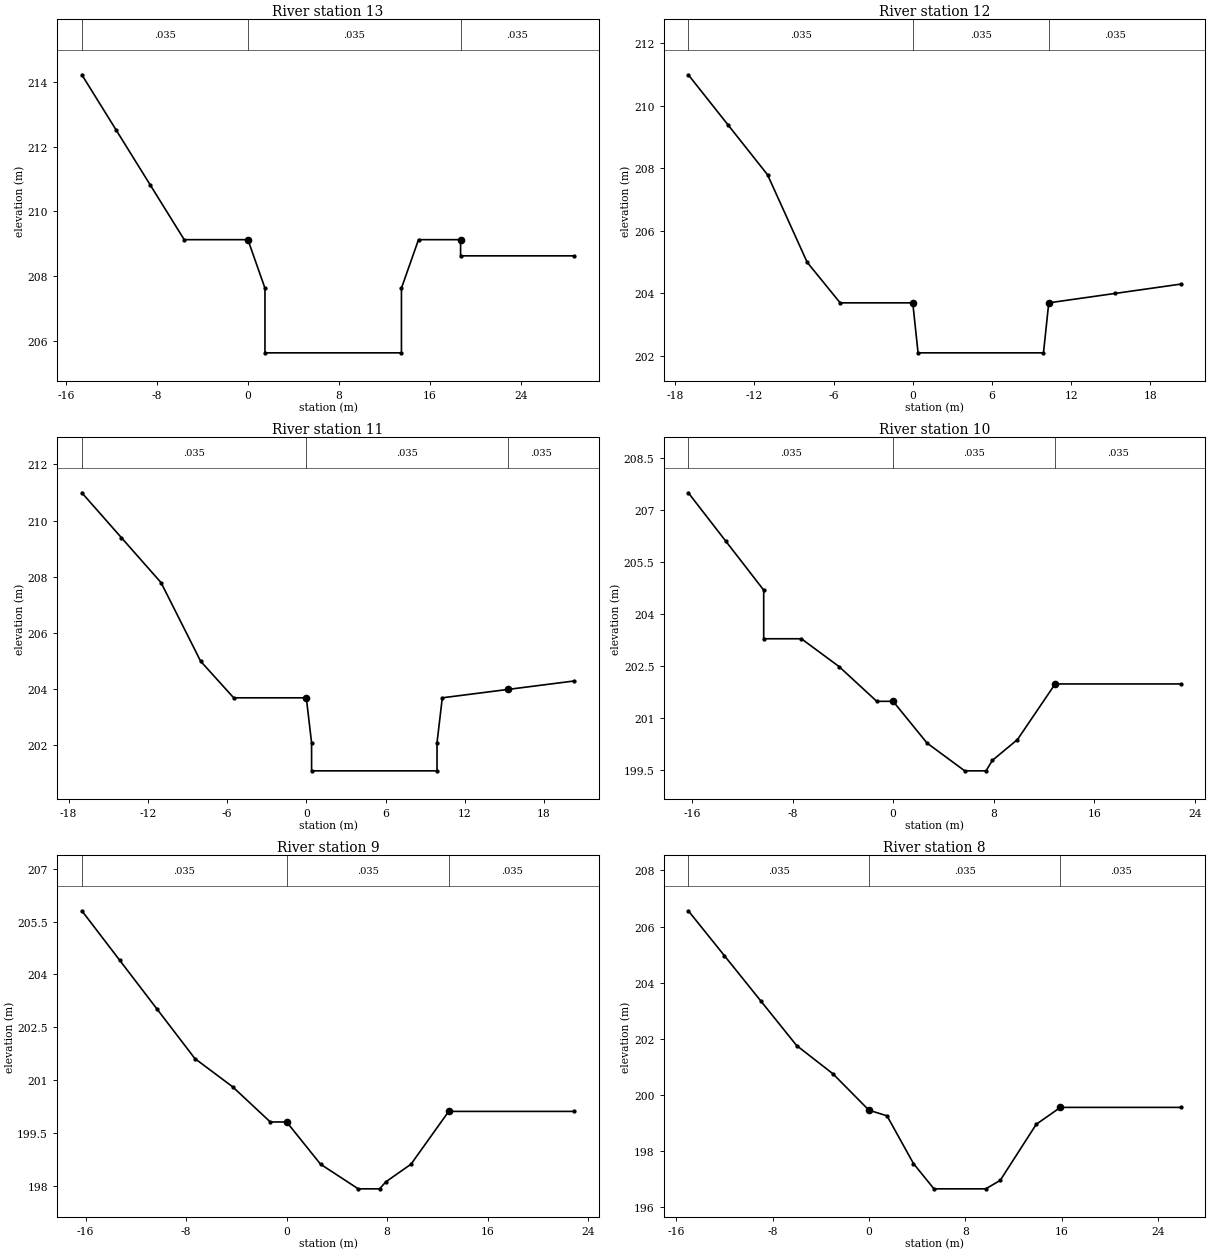
Type RM Length L Ch R = 1 ,13      ,11,11,11
BEGIN DESCRIPTION:
10.012
END DESCRIPTION:
#Sta/Elev= 13
   -14.6  214.22   -11.6  212.52    -8.6  210.82    -5.6  209.12       0  209.12
     1.5  207.62     1.5  205.62    13.5  205.62    13.5  207.62      15  209.12
    18.7  209.12    18.7  208.62    28.7  208.62
#Mann= 3 , 0 , 0
   -14.6    .035       0       0    .035       0    18.7    .035       0
#XS Ineff= 2 , 0
               0  209.12    18.7          208.62
Permanent Ineff=
       F       F
Bank Sta=0,18.7
XS Rating Curve= 0
Exp/Cntr=.3,.1

Type RM Length L Ch R = 1 ,12      ,1,1,1
BEGIN DESCRIPTION:
10.001
END DESCRIPTION:
#Sta/Elev= 11
     -17  210.99     -14  209.39     -11  207.79      -8  204.99    -5.5  203.69
       0  203.69      .4  202.09     9.9  202.09    10.3  203.69    15.3  203.99
    20.3  204.29
#Mann= 3 , 0 , 0
     -17    .035       0       0    .035       0    10.3    .035       0
#XS Ineff= 2 , 0
               0  203.69    10.3          203.69
Permanent Ineff=
       F       F
Bank Sta=0,10.3
XS Rating Curve= 0
Exp/Cntr=.3,.1

Type RM Length L Ch R = 1 ,11      ,50,50,50
BEGIN DESCRIPTION:
10
END DESCRIPTION:
#Sta/Elev= 13
     -17  210.99     -14  209.39     -11  207.79      -8  204.99    -5.5  203.69
       0  203.69      .4  202.09      .4  201.09     9.9  201.09     9.9  202.09
    10.3  203.69    15.3  203.99    20.3  204.29
#Mann= 3 , 0 , 0
     -17    .035       0       0    .035       0    15.3    .035       0
#XS Ineff= 2 , 0
               0  203.69    15.3          203.99
Permanent Ineff=
       F       F
Bank Sta=0,15.3
XS Rating Curve= 0
Exp/Cntr=.3,.1

Type RM Length L Ch R = 1 ,10      ,50,50,50
BEGIN DESCRIPTION:
9
END DESCRIPTION:
#Sta/Elev= 15
   -16.3  207.49   -13.3  206.09   -10.3  204.69   -10.3  203.29    -7.3  203.29
    -4.3  202.49    -1.3  201.49       0  201.49     2.7  200.29     5.7  199.49
     7.4  199.49     7.9  199.79     9.9  200.39    12.9  201.99    22.9  201.99
#Mann= 3 , 0 , 0
   -16.3    .035       0       0    .035       0    12.9    .035       0
#XS Ineff= 2 , 0
               0  201.49    12.9          201.99
Permanent Ineff=
       F       F
Bank Sta=0,12.9
XS Rating Curve= 0
Exp/Cntr=.3,.1

Type RM Length L Ch R = 1 ,9       ,50,50,50
BEGIN DESCRIPTION:
8
END DESCRIPTION:
#Sta/Elev= 14
   -16.3  205.81   -13.3  204.41   -10.3  203.01    -7.3  201.61    -4.3  200.81
    -1.3  199.81       0  199.81     2.7  198.61     5.7  197.91     7.4  197.91
     7.9  198.11     9.9  198.61    12.9  200.11    22.9  200.11
#Mann= 3 , 0 , 0
   -16.3    .035       0       0    .035       0    12.9    .035       0
#XS Ineff= 2 , 0
               0  199.81    12.9          200.11
Permanent Ineff=
       F       F
Bank Sta=0,12.9
XS Rating Curve= 0
Exp/Cntr=.3,.1

Type RM Length L Ch R = 1 ,8       ,50,50,50
BEGIN DESCRIPTION:
7
END DESCRIPTION:
#Sta/Elev= 14
     -15  206.56     -12  204.96      -9  203.36      -6  201.76      -3  200.76
       0  199.46     1.5  199.26     3.7  197.56     5.4  196.66     9.7  196.66
    10.9  196.96    13.9  198.96    15.9  199.56    25.9  199.56
#Mann= 3 , 0 , 0
     -15    .035       0       0    .035       0    15.9    .035       0
#XS Ineff= 2 , 0
               0  199.46    15.9          199.56
Permanent Ineff=
       F       F
Bank Sta=0,15.9
XS Rating Curve= 0
Exp/Cntr=.3,.1

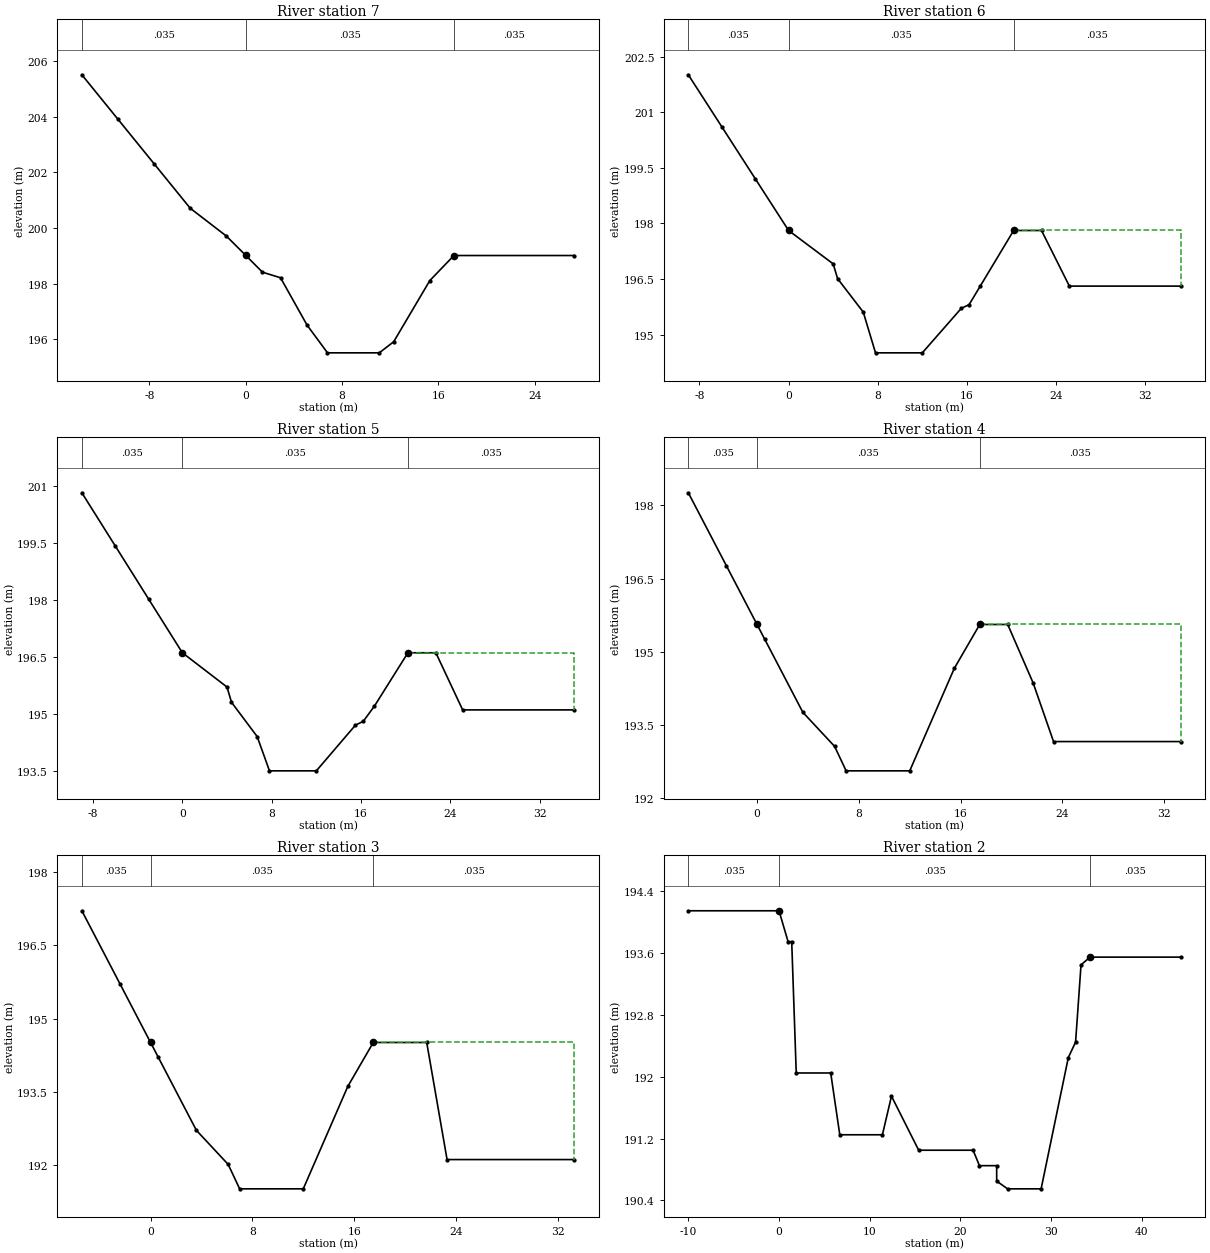
Type RM Length L Ch R = 1 ,7       ,50,50,50
BEGIN DESCRIPTION:
6
END DESCRIPTION:
#Sta/Elev= 15
   -13.6  205.51   -10.6  203.91    -7.6  202.31    -4.6  200.71    -1.6  199.71
       0  199.02     1.4  198.41     2.9  198.21     5.1  196.51     6.8  195.51
    11.1  195.51    12.3  195.91    15.3  198.11    17.3  199.01    27.3  199.01
#Mann= 3 , 0 , 0
   -13.6    .035       0       0    .035       0    17.3    .035       0
#XS Ineff= 2 , 0
               0  199.02    17.3          199.01
Permanent Ineff=
       F       F
Bank Sta=0,17.3
XS Rating Curve= 0
Exp/Cntr=.3,.1

Type RM Length L Ch R = 1 ,6       ,50,50,50
BEGIN DESCRIPTION:
5
END DESCRIPTION:
#Sta/Elev= 16
      -9  202.01      -6  200.61      -3  199.21       0  197.81       4  196.91
     4.4  196.51     6.7  195.61     7.8  194.51      12  194.51    15.5  195.71
    16.2  195.81    17.2  196.31    20.2  197.81    22.7  197.81    25.2  196.31
    35.2  196.31
#Mann= 3 , 0 , 0
      -9    .035       0       0    .035       0    20.2    .035       0
#XS Ineff= 2 , 0
               0  197.81    20.2          197.81
Permanent Ineff=
       F       F
Bank Sta=0,20.2
XS Rating Curve= 0
Exp/Cntr=.3,.1

Type RM Length L Ch R = 1 ,5       ,50,50,50
BEGIN DESCRIPTION:
4
END DESCRIPTION:
#Sta/Elev= 17
      -9  200.81      -6  199.41      -3  198.01       0  196.61       0  196.61
       4  195.71     4.4  195.31     6.7  194.41     7.8  193.51      12  193.51
    15.5  194.71    16.2  194.81    17.2  195.21    20.2  196.61    22.7  196.61
    25.1  195.11    35.1  195.11
#Mann= 3 , 0 , 0
      -9    .035       0       0    .035       0    20.2    .035       0
#XS Ineff= 2 , 0
               0  196.61    20.2          196.61
Permanent Ineff=
       F       F
Bank Sta=0,20.2
XS Rating Curve= 0
Exp/Cntr=.3,.1

Type RM Length L Ch R = 1 ,4       ,50,50,50
BEGIN DESCRIPTION:
3
END DESCRIPTION:
#Sta/Elev= 14
    -5.4  198.26    -2.4  196.76       0  195.56      .6  195.26     3.6  193.76
     6.1  193.06       7  192.56      12  192.56    15.5  194.66    17.5  195.56
    19.7  195.56    21.7  194.36    23.3  193.16    33.3  193.16
#Mann= 3 , 0 , 0
    -5.4    .035       0       0    .035       0    17.5    .035       0
#XS Ineff= 2 , 0
               0  195.56    17.5          195.56
Permanent Ineff=
       F       F
Bank Sta=0,17.5
XS Rating Curve= 0
Exp/Cntr=.3,.1

Type RM Length L Ch R = 1 ,3       ,50,50,50
BEGIN DESCRIPTION:
2
END DESCRIPTION:
#Sta/Elev= 13
    -5.4  197.21    -2.4  195.71       0  194.51      .6  194.21     3.6  192.71
     6.1  192.01       7  191.51      12  191.51    15.5  193.61    17.5  194.51
    21.7  194.51    23.3  192.11    33.3  192.11
#Mann= 3 , 0 , 0
    -5.4    .035       0       0    .035       0    17.5    .035       0
#XS Ineff= 2 , 0
               0  194.51    17.5          194.51
Permanent Ineff=
       F       F
Bank Sta=0,17.5
XS Rating Curve= 0
Exp/Cntr=.3,.1

Type RM Length L Ch R = 1 ,2       ,50,50,50
BEGIN DESCRIPTION:
1
END DESCRIPTION:
#Sta/Elev= 21
     -10  194.15       0  194.15       1  193.75     1.4  193.75     1.9  192.05
     5.7  192.05     6.7  191.25    11.4  191.25    12.4  191.75    15.4  191.05
    21.4  191.05    22.1  190.85      24  190.85      24  190.65    25.2  190.55
    28.9  190.55    31.9  192.25    32.7  192.45    33.3  193.45    34.3  193.55
    44.3  193.55
#Mann= 3 , 0 , 0
     -10    .035       0       0    .035       0    34.3    .035       0
#XS Ineff= 2 , 0
               0  194.15    34.3          193.55
Permanent Ineff=
       F       F
Bank Sta=0,34.3
XS Rating Curve= 0
Exp/Cntr=.3,.1

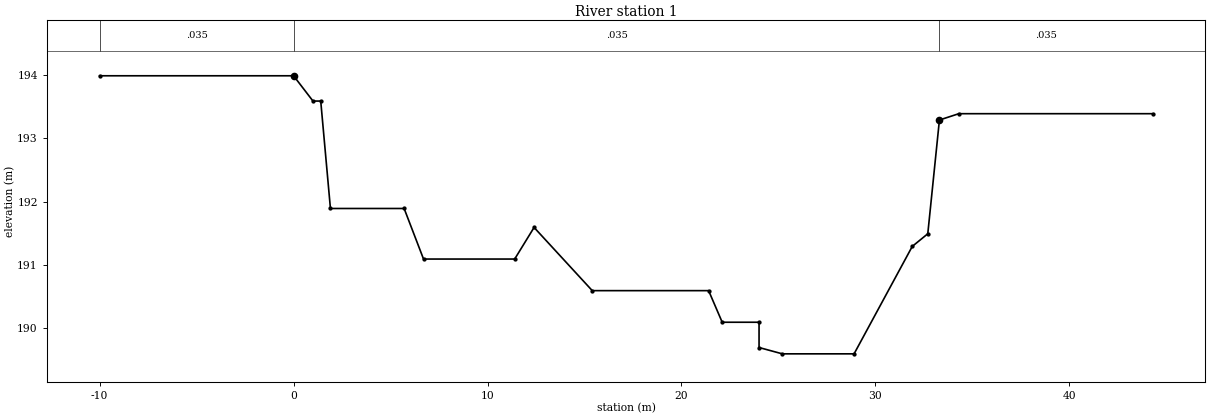
Type RM Length L Ch R = 1 ,1       ,0,0,0
BEGIN DESCRIPTION:
0
END DESCRIPTION:
#Sta/Elev= 21
     -10  193.99       0  193.99       1  193.59     1.4  193.59     1.9  191.89
     5.7  191.89     6.7  191.09    11.4  191.09    12.4  191.59    15.4  190.59
    21.4  190.59    22.1  190.09      24  190.09      24  189.69    25.2  189.59
    28.9  189.59    31.9  191.29    32.7  191.49    33.3  193.29    34.3  193.39
    44.3  193.39
#Mann= 3 , 0 , 0
     -10    .035       0       0    .035       0    33.3    .035       0
#XS Ineff= 2 , 0
               0  193.99    33.3          193.29
Permanent Ineff=
       F       F
Bank Sta=0,33.3
XS Rating Curve= 0
Exp/Cntr=.3,.1

Chan Stop Cuts=-1