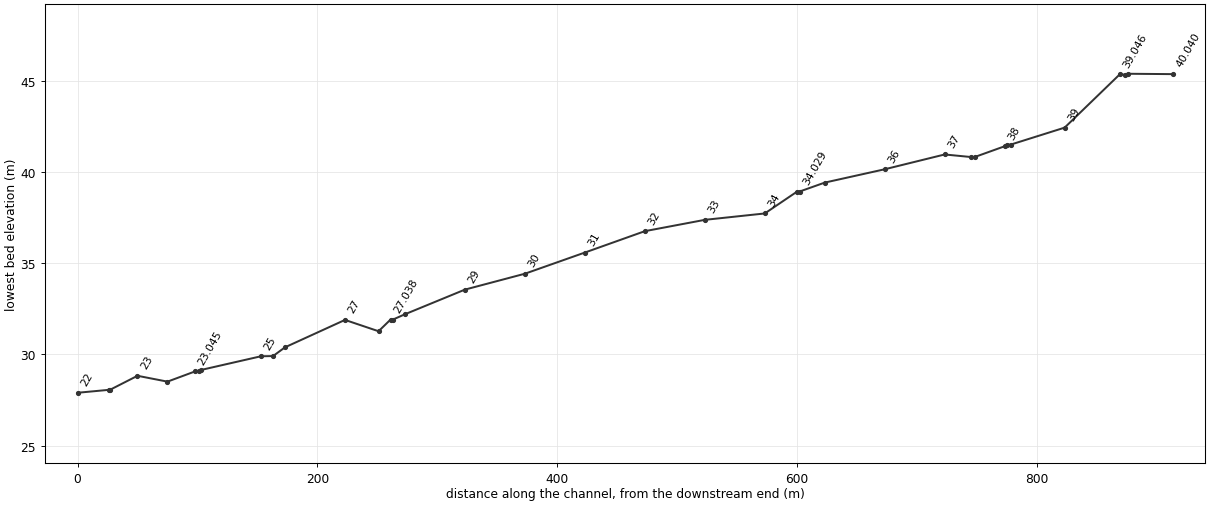
--- DAEKOK.prj (project) ---

Proj Title=DAEKOK
Current Plan=p01
Default Exp/Contr=.3,.1
SI Units
Geom File=g01
Flow File=f01
Plan File=p01
Y Axis Title=Elevation
X Axis Title(PF)=Main Channel Distance
X Axis Title(XS)=Station
BEGIN DESCRIPTION:
           BACK WATER COMPUTATION
      APPLICATION OF HEC-2 BY Samju Construction Engineering
      DAEGOK-STREEM : 30 YR
END DESCRIPTION:
DSS Export Rating Curves= 0
DSS Export Rating Curve Sorted= 0
DSS Export Volume Flow Curves= 0
DXF OffsetX= 0
DXF OffsetY= 0
DXF ScaleX= 1
DXF ScaleY= 10

--- DAEKOK.p01 (plan) ---

Plan Title=Imported Plan 01
Version=Version 3.0.1  Mar 2001
Short Identifier=Imported Pla
Geom File=g01
Flow File=f01
Subcritical Flow
K Sum by GR= 0
Std Step Tol= 0.003
Critical Tol= 0.003
Num of Std Step Trials= 20
Max Error Tol= 0.1
Flow Tol Ratio= 0.001
Split Flow NTrial= 30
Split Flow Tol= 0.02
Split Flow Ratio= 0.02
Log Output Level= 0
Friction Slope Method= 1
Unsteady Friction Slope Method= 2
Parabolic Critical Depth
Global Vel Dist= 0 , 0 , 0
Global Log Level= 0
CheckData=True
Encroach Param=-1 ,0,0, 0
Computation Interval=1HOUR
Output Interval=1HOUR
Run HTab= 0
Run UNet= 0
Run PostProcess= 0
UNET Theta= 1
UNET ZTol= 0.02
UNET ZSATol= 0.1
UNET MxIter= 20
UNET MaxInSteps= 20
UNET DtIC= 0
UNET DtMin= 0
UNET MaxCRTS= 20
UNET WFStab= 2
UNET SFStab= 1
UNET WFX= 1
UNET SFX= 1
UNET Convert EG Bridges=-1
UNET Use Existing IB Tables=-1
Instantaneous Interval=1HOUR
Write IC File= 0
Write Velocity= 0
Write Detailed= 0

--- DAEKOK.f01 (steady flow) ---

Flow Title=Imported Flow 01
Version=Version 3.0.1  Mar 2001
Number of Profiles= 5
Profile Names=10YR,20YR,30YR,50YR,80YR
River Rch & RM=RIVER-1,Reach-1         ,40.040
    19.3      22    23.6    25.7    27.9
River Rch & RM=RIVER-1,Reach-1         ,12
    38.2    43.4    46.6    50.1    54.9
Boundary for River Rch & Prof#=RIVER-1,Reach-1         , 1
Up Type= 0
Dn Type= 3
Dn Slope=.052
Boundary for River Rch & Prof#=RIVER-1,Reach-1         , 2
Up Type= 0
Dn Type= 3
Dn Slope=.052
Boundary for River Rch & Prof#=RIVER-1,Reach-1         , 3
Up Type= 0
Dn Type= 3
Dn Slope=.052
Boundary for River Rch & Prof#=RIVER-1,Reach-1         , 4
Up Type= 0
Dn Type= 3
Dn Slope=.052
Boundary for River Rch & Prof#=RIVER-1,Reach-1         , 5
Up Type= 0
Dn Type= 3
Dn Slope=.052
DSS Import GetInterval= 0
DSS Import GetPeak= 0
DSS Import FillOption= 0

--- DAEKOK.g01 (geometry) ---

Geom Title=Imported Geom 01
Version=Version 3.0.1  Mar 2001

River Reach=RIVER-1         ,Reach-1
Reach XY= 2
              .5             .95              .5             .05

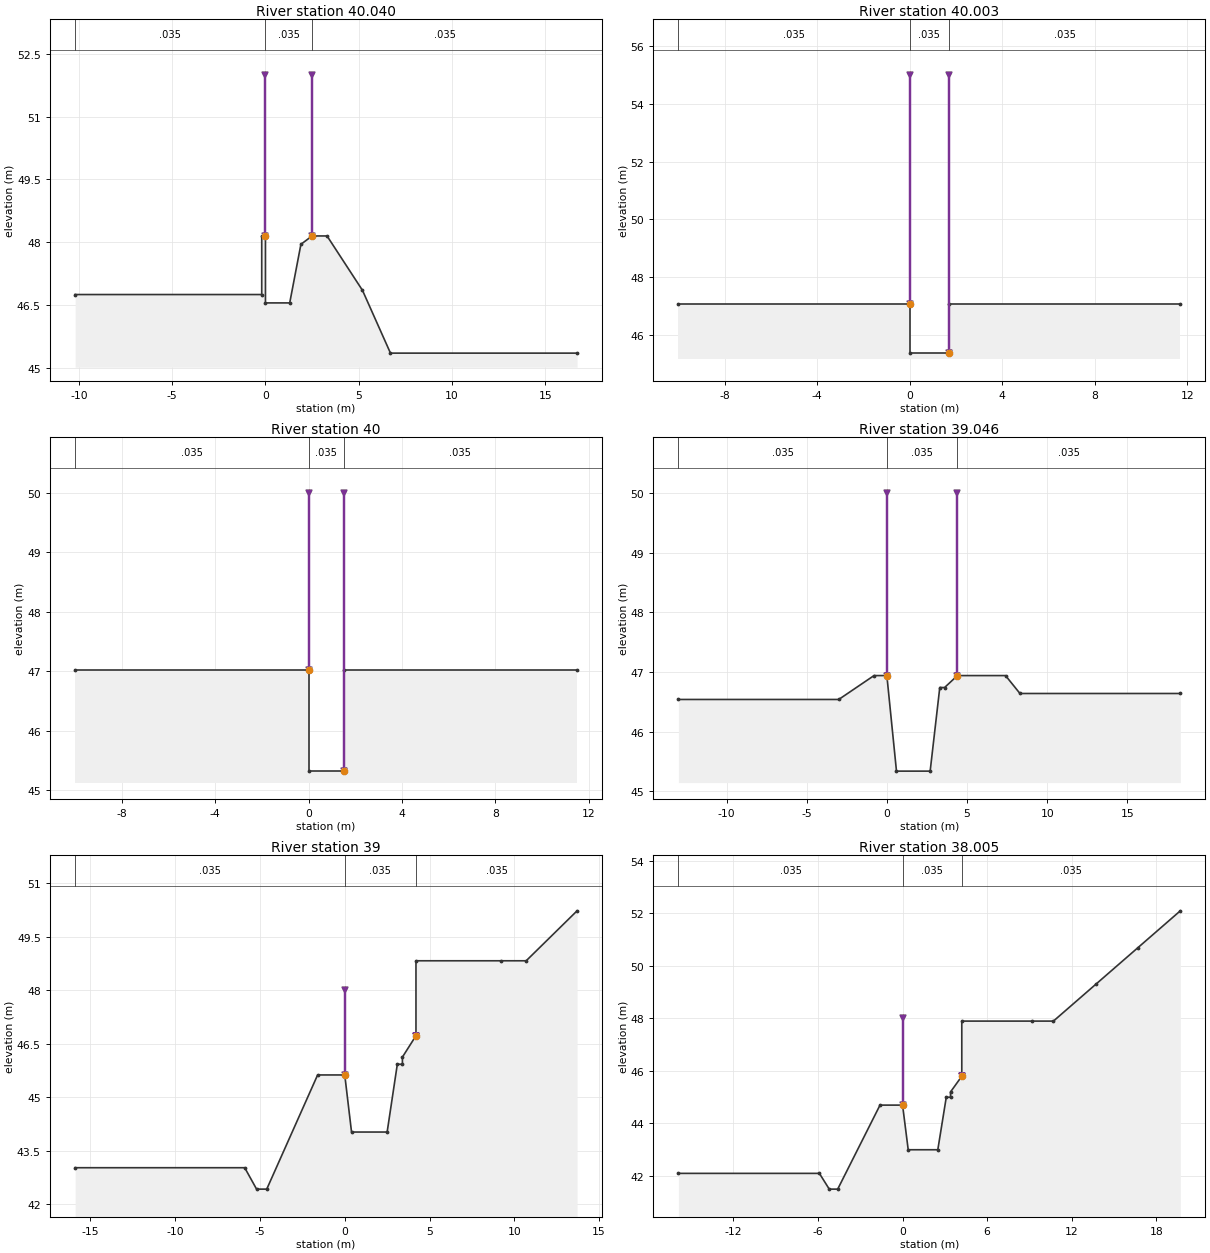
Type RM Length L Ch R = 1 ,40.040  ,37,37,37
#Sta/Elev= 12
   -10.2   46.75     -.2   46.75     -.2   48.15       0   48.15       0   46.55
     1.3   46.55     1.9   47.95     2.5   48.15     3.3   48.15     5.2   46.85
     6.7   45.35    16.7   45.35
#Mann= 3 , 0 , 0
   -10.2    .035       0       0    .035       0     2.5    .035       0
Levee=-1,0,52,-1,2.5,52,,
Bank Sta=0,2.5
XS Rating Curve= 0
Exp/Cntr=.3,.1

Type RM Length L Ch R = 1 ,40.003  ,3,3,3
#Sta/Elev= 6
     -10   47.07       0   47.07       0   45.37     1.7   45.37     1.7   47.07
    11.7   47.07
#Mann= 3 , 0 , 0
     -10    .035       0       0    .035       0     1.7    .035       0
Levee=-1,0,55,-1,1.7,55,,
Bank Sta=0,1.7
XS Rating Curve= 0
Exp/Cntr=.3,.1

Type RM Length L Ch R = 1 ,40      ,4,4,4
#Sta/Elev= 6
     -10   47.02       0   47.02       0   45.32     1.5   45.32     1.5   47.02
    11.5   47.02
#Mann= 3 , 0 , 0
     -10    .035       0       0    .035       0     1.5    .035       0
Levee=-1,0,50,-1,1.5,50,,
Bank Sta=0,1.5
XS Rating Curve= 0
Exp/Cntr=.3,.1

Type RM Length L Ch R = 1 ,39.046  ,46,46,46
#Sta/Elev= 12
     -13   46.54      -3   46.54     -.8   46.94       0   46.94      .6   45.34
     2.7   45.34     3.3   46.74     3.6   46.74     4.4   46.94     7.4   46.94
     8.3   46.64    18.3   46.64
#Mann= 3 , 0 , 0
     -13    .035       0       0    .035       0     4.4    .035       0
Levee=-1,0,50,-1,4.4,50,,
Bank Sta=0,4.4
XS Rating Curve= 0
Exp/Cntr=.3,.1

Type RM Length L Ch R = 1 ,39      ,45,45,45
#Sta/Elev= 16
   -15.9   43.02    -5.9   43.02    -5.2   42.42    -4.6   42.42    -1.6   45.62
       0   45.62      .4   44.02     2.5   44.02     3.1   45.92     3.4   45.92
     3.4   46.12     4.2   46.72     4.2   48.82     9.2   48.82    10.7   48.82
    13.7   50.22
#Mann= 3 , 0 , 0
   -15.9    .035       0       0    .035       0     4.2    .035       0
Levee=-1,0,48,-1,4.2,46.72,,
Bank Sta=0,4.2
XS Rating Curve= 0
Exp/Cntr=.3,.1

Type RM Length L Ch R = 1 ,38.005  ,3,3,3
#Sta/Elev= 18
   -15.9   42.09    -5.9   42.09    -5.2   41.49    -4.6   41.49    -1.6   44.69
       0   44.69      .4   42.99     2.5   42.99     3.1   44.99     3.4   44.99
     3.4   45.19     4.2   45.79     4.2   47.89     9.2   47.89    10.7   47.89
    13.7   49.29    16.7   50.69    19.7   52.09
#Mann= 3 , 0 , 0
   -15.9    .035       0       0    .035       0     4.2    .035       0
Levee=-1,0,48,-1,4.2,45.79,,
Bank Sta=0,4.2
XS Rating Curve= 0
Exp/Cntr=.3,.1

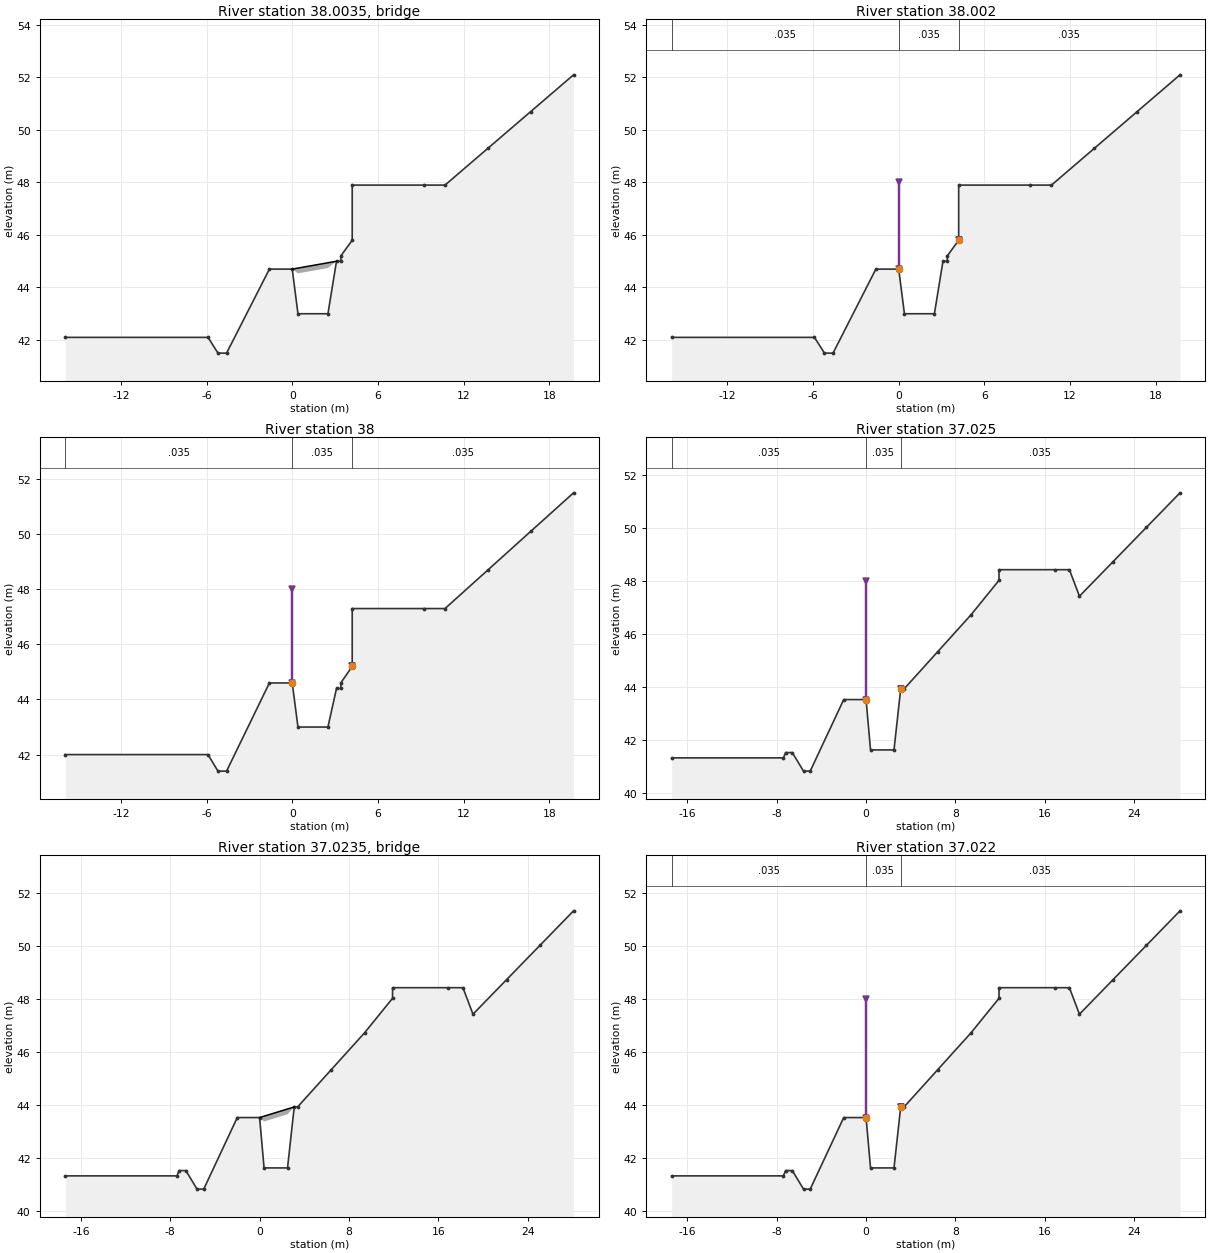
Type RM Length L Ch R = 3 ,38.0035 ,,,
Bridge Culvert--1,0,-1,-1, 0
Deck Dist Width WeirC Skew NumUp NumDn MinLoCord MaxHiCord MaxSubmerge Is_Ogee
.001,2.999,1.44,0, 2, 2, , , .95, 0, 0,0,,
       0     3.1
   44.69   44.99
   44.49   44.79
       0     3.1
   44.69   44.99
   44.49   44.79
BR Coef=-1 , 0 , 0 ,, 0 ,,,.8,-1,,0,
WSPro=,,,, 1 ,,,, 0 ,,,, 0 ,,,,-1 ,-1 ,-1 , 0 , 0 , 0 , 0 , 0
BC Design=,, 0 ,, 0 ,,,,,,

Type RM Length L Ch R = 1 ,38.002  ,2,2,2
#Sta/Elev= 18
   -15.9   42.09    -5.9   42.09    -5.2   41.49    -4.6   41.49    -1.6   44.69
       0   44.69      .4   42.99     2.5   42.99     3.1   44.99     3.4   44.99
     3.4   45.19     4.2   45.79     4.2   47.89     9.2   47.89    10.7   47.89
    13.7   49.29    16.7   50.69    19.7   52.09
#Mann= 3 , 0 , 0
   -15.9    .035       0       0    .035       0     4.2    .035       0
Levee=-1,0,48,-1,4.2,45.79,,
Bank Sta=0,4.2
XS Rating Curve= 0
Exp/Cntr=.3,.1

Type RM Length L Ch R = 1 ,38      ,25,25,25
#Sta/Elev= 18
   -15.9      42    -5.9      42    -5.2    41.4    -4.6    41.4    -1.6    44.6
       0    44.6      .4      43     2.5      43     3.1    44.4     3.4    44.4
     3.4    44.6     4.2    45.2     4.2    47.3     9.2    47.3    10.7    47.3
    13.7    48.7    16.7    50.1    19.7    51.5
#Mann= 3 , 0 , 0
   -15.9    .035       0       0    .035       0     4.2    .035       0
Levee=-1,0,48,-1,4.2,45.2,,
Bank Sta=0,4.2
XS Rating Curve= 0
Exp/Cntr=.3,.1

Type RM Length L Ch R = 1 ,37.025  ,3,3,3
#Sta/Elev= 22
   -17.4   41.31    -7.4   41.31    -7.2   41.51    -6.6   41.51    -5.6   40.81
      -5   40.81      -2   43.51       0   43.51      .4   41.61     2.5   41.61
     3.1   43.91     3.4   43.91     6.4   45.31     9.4   46.71    11.9   48.01
    11.9   48.41    16.9   48.41    18.2   48.41    19.1   47.41    22.1   48.71
    25.1   50.01    28.1   51.31
#Mann= 3 , 0 , 0
   -17.4    .035       0       0    .035       0     3.1    .035       0
Levee=-1,0,48,-1,3.1,43.91,,
Bank Sta=0,3.1
XS Rating Curve= 0
Exp/Cntr=.3,.1

Type RM Length L Ch R = 3 ,37.0235 ,,,
Bridge Culvert--1,0,-1,-1, 0
Deck Dist Width WeirC Skew NumUp NumDn MinLoCord MaxHiCord MaxSubmerge Is_Ogee
.001,2.999,1.44,0, 2, 2, , , .95, 0, 0,0,,
       0     3.1
   43.51   43.91
   43.31   43.71
       0     3.1
   43.51   43.91
   43.31   43.71
BR Coef=-1 , 0 , 0 ,, 0 ,,,.8,-1,,0,
WSPro=,,,, 1 ,,,, 0 ,,,, 0 ,,,,-1 ,-1 ,-1 , 0 , 0 , 0 , 0 , 0
BC Design=,, 0 ,, 0 ,,,,,,

Type RM Length L Ch R = 1 ,37.022  ,22,22,22
#Sta/Elev= 22
   -17.4   41.31    -7.4   41.31    -7.2   41.51    -6.6   41.51    -5.6   40.81
      -5   40.81      -2   43.51       0   43.51      .4   41.61     2.5   41.61
     3.1   43.91     3.4   43.91     6.4   45.31     9.4   46.71    11.9   48.01
    11.9   48.41    16.9   48.41    18.2   48.41    19.1   47.41    22.1   48.71
    25.1   50.01    28.1   51.31
#Mann= 3 , 0 , 0
   -17.4    .035       0       0    .035       0     3.1    .035       0
Levee=-1,0,48,-1,3.1,43.91,,
Bank Sta=0,3.1
XS Rating Curve= 0
Exp/Cntr=.3,.1

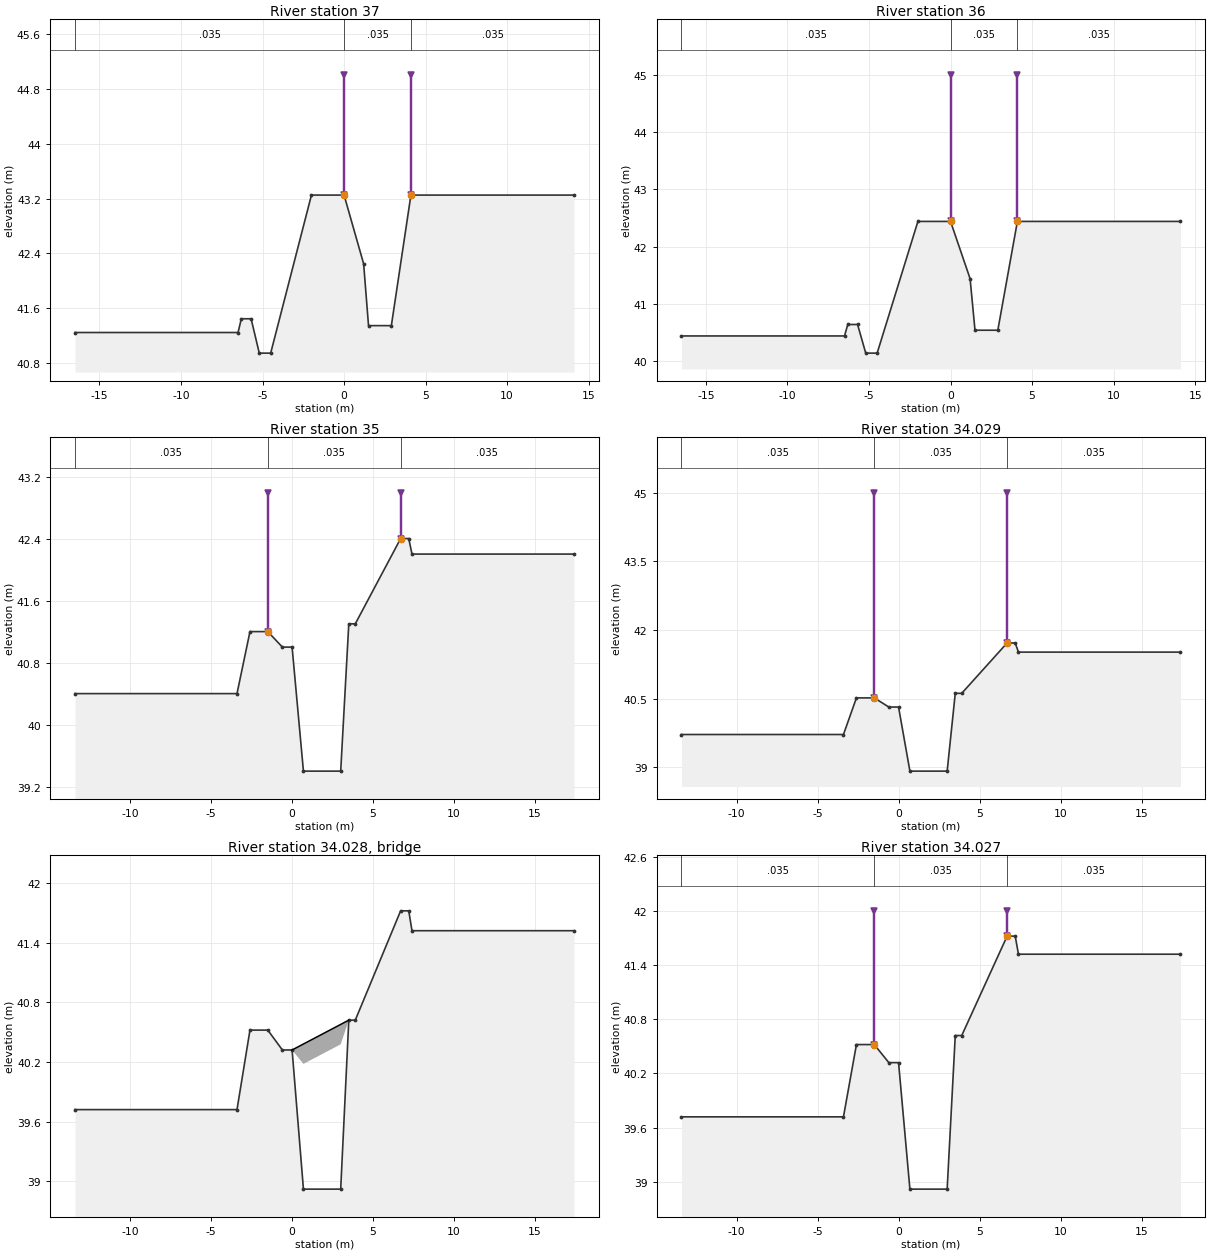
Type RM Length L Ch R = 1 ,37      ,50,50,50
#Sta/Elev= 13
   -16.5   41.25    -6.5   41.25    -6.3   41.45    -5.7   41.45    -5.2   40.95
    -4.5   40.95      -2   43.25       0   43.25     1.2   42.25     1.5   41.35
     2.9   41.35     4.1   43.25    14.1   43.25
#Mann= 3 , 0 , 0
   -16.5    .035       0       0    .035       0     4.1    .035       0
Levee=-1,0,45,-1,4.1,45,,
Bank Sta=0,4.1
XS Rating Curve= 0
Exp/Cntr=.3,.1

Type RM Length L Ch R = 1 ,36      ,50,50,50
#Sta/Elev= 13
   -16.5   40.44    -6.5   40.44    -6.3   40.64    -5.7   40.64    -5.2   40.14
    -4.5   40.14      -2   42.44       0   42.44     1.2   41.44     1.5   40.54
     2.9   40.54     4.1   42.44    14.1   42.44
#Mann= 3 , 0 , 0
   -16.5    .035       0       0    .035       0     4.1    .035       0
Levee=-1,0,45,-1,4.1,45,,
Bank Sta=0,4.1
XS Rating Curve= 0
Exp/Cntr=.3,.1

Type RM Length L Ch R = 1 ,35      ,21,21,21
#Sta/Elev= 14
   -13.4   40.41    -3.4   40.41    -2.6   41.21    -1.5   41.21     -.6   41.01
       0   41.01      .7   39.41       3   39.41     3.5   41.31     3.9   41.31
     6.7   42.41     7.2   42.41     7.4   42.21    17.4   42.21
#Mann= 3 , 0 , 0
   -13.4    .035       0    -1.5    .035       0     6.7    .035       0
Levee=-1,-1.5,43,-1,6.7,43,,
Bank Sta=-1.5,6.7
XS Rating Curve= 0
Exp/Cntr=.3,.1

Type RM Length L Ch R = 1 ,34.029  ,2,2,2
#Sta/Elev= 14
   -13.4   39.72    -3.4   39.72    -2.6   40.52    -1.5   40.52     -.6   40.32
       0   40.32      .7   38.92       3   38.92     3.5   40.62     3.9   40.62
     6.7   41.72     7.2   41.72     7.4   41.52    17.4   41.52
#Mann= 3 , 0 , 0
   -13.4    .035       0    -1.5    .035       0     6.7    .035       0
Levee=-1,-1.5,45,-1,6.7,45,,
Bank Sta=-1.5,6.7
XS Rating Curve= 0
Exp/Cntr=.3,.1

Type RM Length L Ch R = 3 ,34.028  ,,,
Bridge Culvert--1,0,-1,-1, 0
Deck Dist Width WeirC Skew NumUp NumDn MinLoCord MaxHiCord MaxSubmerge Is_Ogee
.001,1.999,1.44,0, 2, 2, , , .95, 0, 0,0,,
       0     3.5
   40.32   40.62
   40.12   40.42
       0     3.5
   40.32   40.62
   40.12   40.42
BR Coef=-1 , 0 , 0 ,, 0 ,,,.8,-1,,0,
WSPro=,,,, 1 ,,,, 0 ,,,, 0 ,,,,-1 ,-1 ,-1 , 0 , 0 , 0 , 0 , 0
BC Design=,, 0 ,, 0 ,,,,,,

Type RM Length L Ch R = 1 ,34.027  ,27,27,27
#Sta/Elev= 14
   -13.4   39.72    -3.4   39.72    -2.6   40.52    -1.5   40.52     -.6   40.32
       0   40.32      .7   38.92       3   38.92     3.5   40.62     3.9   40.62
     6.7   41.72     7.2   41.72     7.4   41.52    17.4   41.52
#Mann= 3 , 0 , 0
   -13.4    .035       0    -1.5    .035       0     6.7    .035       0
Levee=-1,-1.5,42,-1,6.7,42,,
Bank Sta=-1.5,6.7
XS Rating Curve= 0
Exp/Cntr=.3,.1

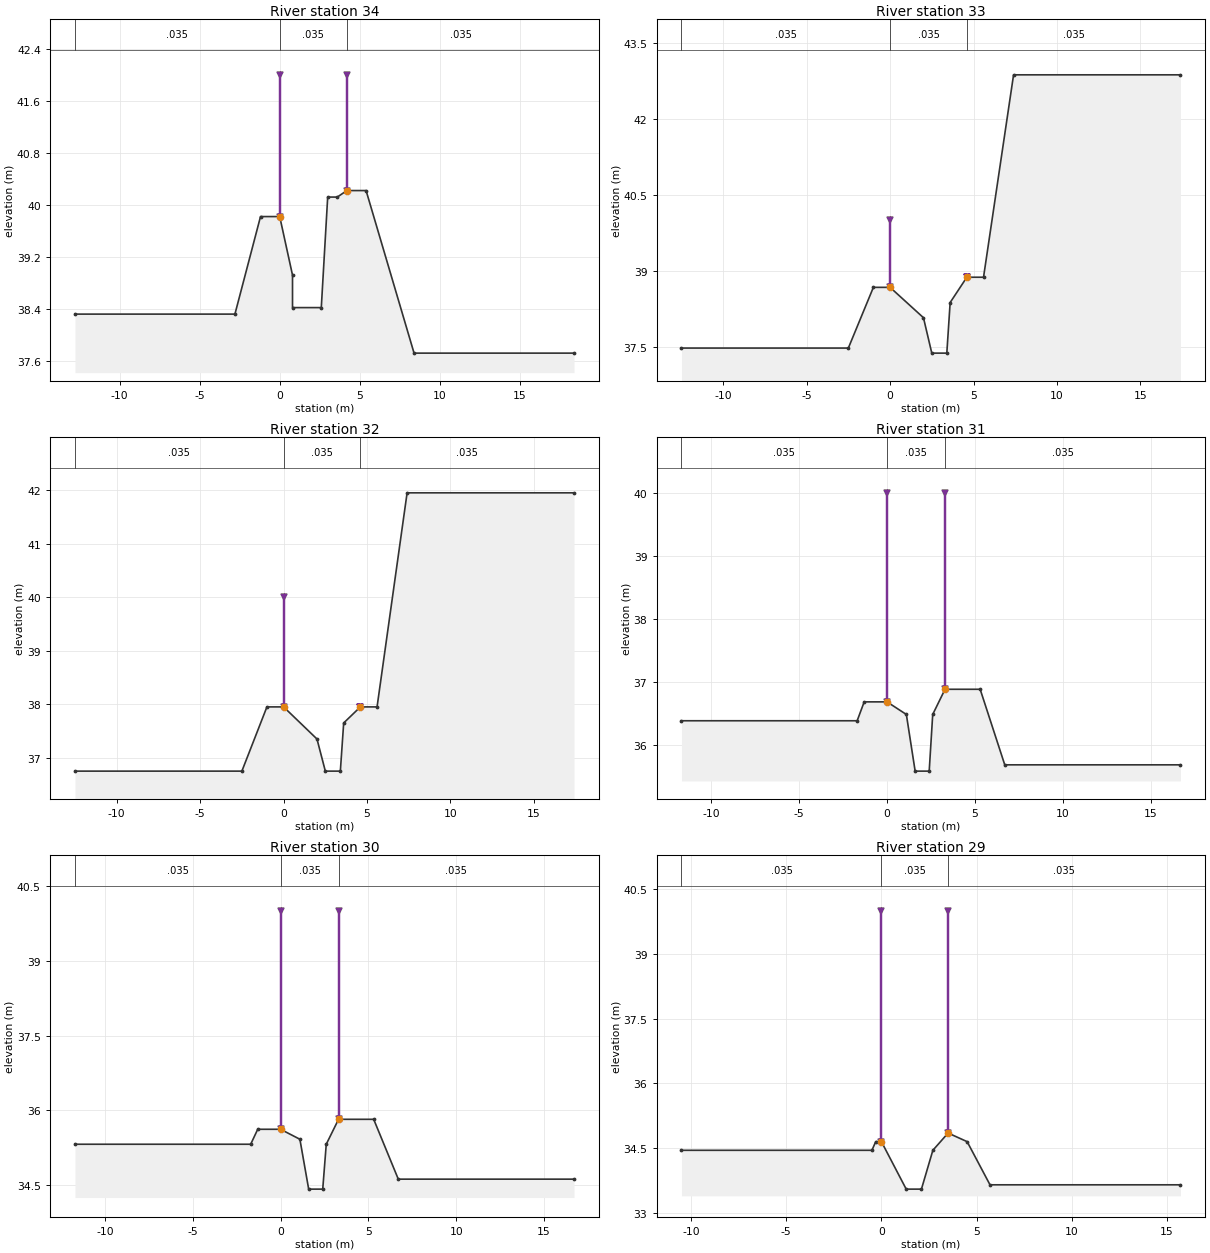
Type RM Length L Ch R = 1 ,34      ,50,50,50
#Sta/Elev= 13
   -12.8   38.32    -2.8   38.32    -1.2   39.82       0   39.82      .8   38.92
      .8   38.42     2.6   38.42       3   40.12     3.6   40.12     4.2   40.22
     5.4   40.22     8.4   37.72    18.4   37.72
#Mann= 3 , 0 , 0
   -12.8    .035       0       0    .035       0     4.2    .035       0
Levee=-1,0,42,-1,4.2,42,,
Bank Sta=0,4.2
XS Rating Curve= 0
Exp/Cntr=.3,.1

Type RM Length L Ch R = 1 ,33      ,50,50,50
#Sta/Elev= 12
   -12.5   37.47    -2.5   37.47      -1   38.67       0   38.67       2   38.07
     2.5   37.37     3.4   37.37     3.6   38.37     4.6   38.87     5.6   38.87
     7.4   42.87    17.4   42.87
#Mann= 3 , 0 , 0
   -12.5    .035       0       0    .035       0     4.6    .035       0
Levee=-1,0,40,-1,4.6,38.87,,
Bank Sta=0,4.6
XS Rating Curve= 0
Exp/Cntr=.3,.1

Type RM Length L Ch R = 1 ,32      ,50,50,50
#Sta/Elev= 12
   -12.5   36.75    -2.5   36.75      -1   37.95       0   37.95       2   37.35
     2.5   36.75     3.4   36.75     3.6   37.65     4.6   37.95     5.6   37.95
     7.4   41.95    17.4   41.95
#Mann= 3 , 0 , 0
   -12.5    .035       0       0    .035       0     4.6    .035       0
Levee=-1,0,40,-1,4.6,37.95,,
Bank Sta=0,4.6
XS Rating Curve= 0
Exp/Cntr=.3,.1

Type RM Length L Ch R = 1 ,31      ,50,50,50
#Sta/Elev= 12
   -11.7   36.38    -1.7   36.38    -1.3   36.68       0   36.68     1.1   36.48
     1.6   35.58     2.4   35.58     2.6   36.48     3.3   36.88     5.3   36.88
     6.7   35.68    16.7   35.68
#Mann= 3 , 0 , 0
   -11.7    .035       0       0    .035       0     3.3    .035       0
Levee=-1,0,40,-1,3.3,40,,
Bank Sta=0,3.3
XS Rating Curve= 0
Exp/Cntr=.3,.1

Type RM Length L Ch R = 1 ,30      ,50,50,50
#Sta/Elev= 12
   -11.7   35.32    -1.7   35.32    -1.3   35.62       0   35.62     1.1   35.42
     1.6   34.42     2.4   34.42     2.6   35.32     3.3   35.82     5.3   35.82
     6.7   34.62    16.7   34.62
#Mann= 3 , 0 , 0
   -11.7    .035       0       0    .035       0     3.3    .035       0
Levee=-1,0,40,-1,3.3,40,,
Bank Sta=0,3.3
XS Rating Curve= 0
Exp/Cntr=.3,.1

Type RM Length L Ch R = 1 ,29      ,50,50,50
#Sta/Elev= 11
   -10.5   34.45     -.5   34.45     -.3   34.65       0   34.65     1.3   33.55
     2.1   33.55     2.7   34.45     3.5   34.85     4.5   34.65     5.7   33.65
    15.7   33.65
#Mann= 3 , 0 , 0
   -10.5    .035       0       0    .035       0     3.5    .035       0
Levee=-1,0,40,-1,3.5,40,,
Bank Sta=0,3.5
XS Rating Curve= 0
Exp/Cntr=.3,.1

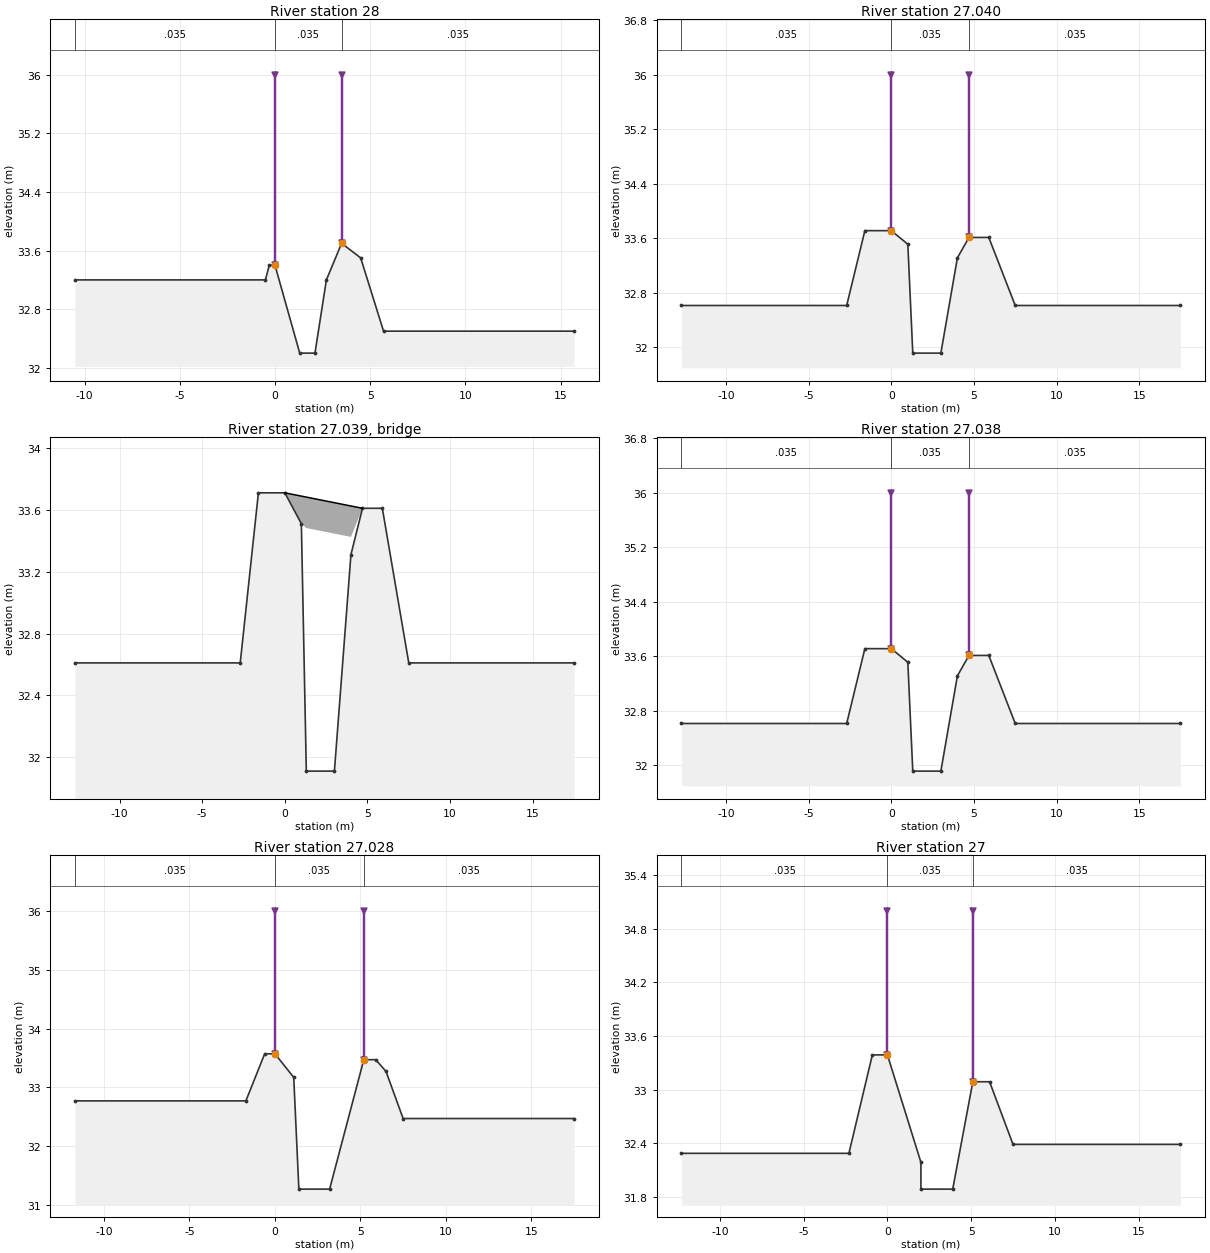
Type RM Length L Ch R = 1 ,28      ,10,10,10
#Sta/Elev= 11
   -10.5    33.2     -.5    33.2     -.3    33.4       0    33.4     1.3    32.2
     2.1    32.2     2.7    33.2     3.5    33.7     4.5    33.5     5.7    32.5
    15.7    32.5
#Mann= 3 , 0 , 0
   -10.5    .035       0       0    .035       0     3.5    .035       0
Levee=-1,0,36,-1,3.5,36,,
Bank Sta=0,3.5
XS Rating Curve= 0
Exp/Cntr=.3,.1

Type RM Length L Ch R = 1 ,27.040  ,2,2,2
#Sta/Elev= 12
   -12.7   32.61    -2.7   32.61    -1.6   33.71       0   33.71       1   33.51
     1.3   31.91       3   31.91       4   33.31     4.7   33.61     5.9   33.61
     7.5   32.61    17.5   32.61
#Mann= 3 , 0 , 0
   -12.7    .035       0       0    .035       0     4.7    .035       0
Levee=-1,0,36,-1,4.7,36,,
Bank Sta=0,4.7
XS Rating Curve= 0
Exp/Cntr=.3,.1

Type RM Length L Ch R = 3 ,27.039  ,,,
Bridge Culvert--1,0,-1,-1, 0
Deck Dist Width WeirC Skew NumUp NumDn MinLoCord MaxHiCord MaxSubmerge Is_Ogee
.001,1.999,1.44,0, 2, 2, , , .95, 0, 0,0,,
       0     4.7
   33.71   33.61
   33.51   33.41
       0     4.7
   33.71   33.61
   33.51   33.41
BR Coef=-1 , 0 , 0 ,, 0 ,,,.8,-1,,0,
WSPro=,,,, 1 ,,,, 0 ,,,, 0 ,,,,-1 ,-1 ,-1 , 0 , 0 , 0 , 0 , 0
BC Design=,, 0 ,, 0 ,,,,,,

Type RM Length L Ch R = 1 ,27.038  ,10,10,10
#Sta/Elev= 12
   -12.7   32.61    -2.7   32.61    -1.6   33.71       0   33.71       1   33.51
     1.3   31.91       3   31.91       4   33.31     4.7   33.61     5.9   33.61
     7.5   32.61    17.5   32.61
#Mann= 3 , 0 , 0
   -12.7    .035       0       0    .035       0     4.7    .035       0
Levee=-1,0,36,-1,4.7,36,,
Bank Sta=0,4.7
XS Rating Curve= 0
Exp/Cntr=.3,.1

Type RM Length L Ch R = 1 ,27.028  ,28,28,28
#Sta/Elev= 12
   -11.7   32.77    -1.7   32.77     -.6   33.57       0   33.57     1.1   33.17
     1.4   31.27     3.2   31.27     5.2   33.47     5.9   33.47     6.5   33.27
     7.5   32.47    17.5   32.47
#Mann= 3 , 0 , 0
   -11.7    .035       0       0    .035       0     5.2    .035       0
Levee=-1,0,36,-1,5.2,36,,
Bank Sta=0,5.2
XS Rating Curve= 0
Exp/Cntr=.3,.1

Type RM Length L Ch R = 1 ,27      ,50,50,50
#Sta/Elev= 11
   -12.3   32.29    -2.3   32.29     -.9   33.39       0   33.39       2   32.19
       2   31.89     3.9   31.89     5.1   33.09     6.1   33.09     7.5   32.39
    17.5   32.39
#Mann= 3 , 0 , 0
   -12.3    .035       0       0    .035       0     5.1    .035       0
Levee=-1,0,35,-1,5.1,35,,
Bank Sta=0,5.1
XS Rating Curve= 0
Exp/Cntr=.3,.1

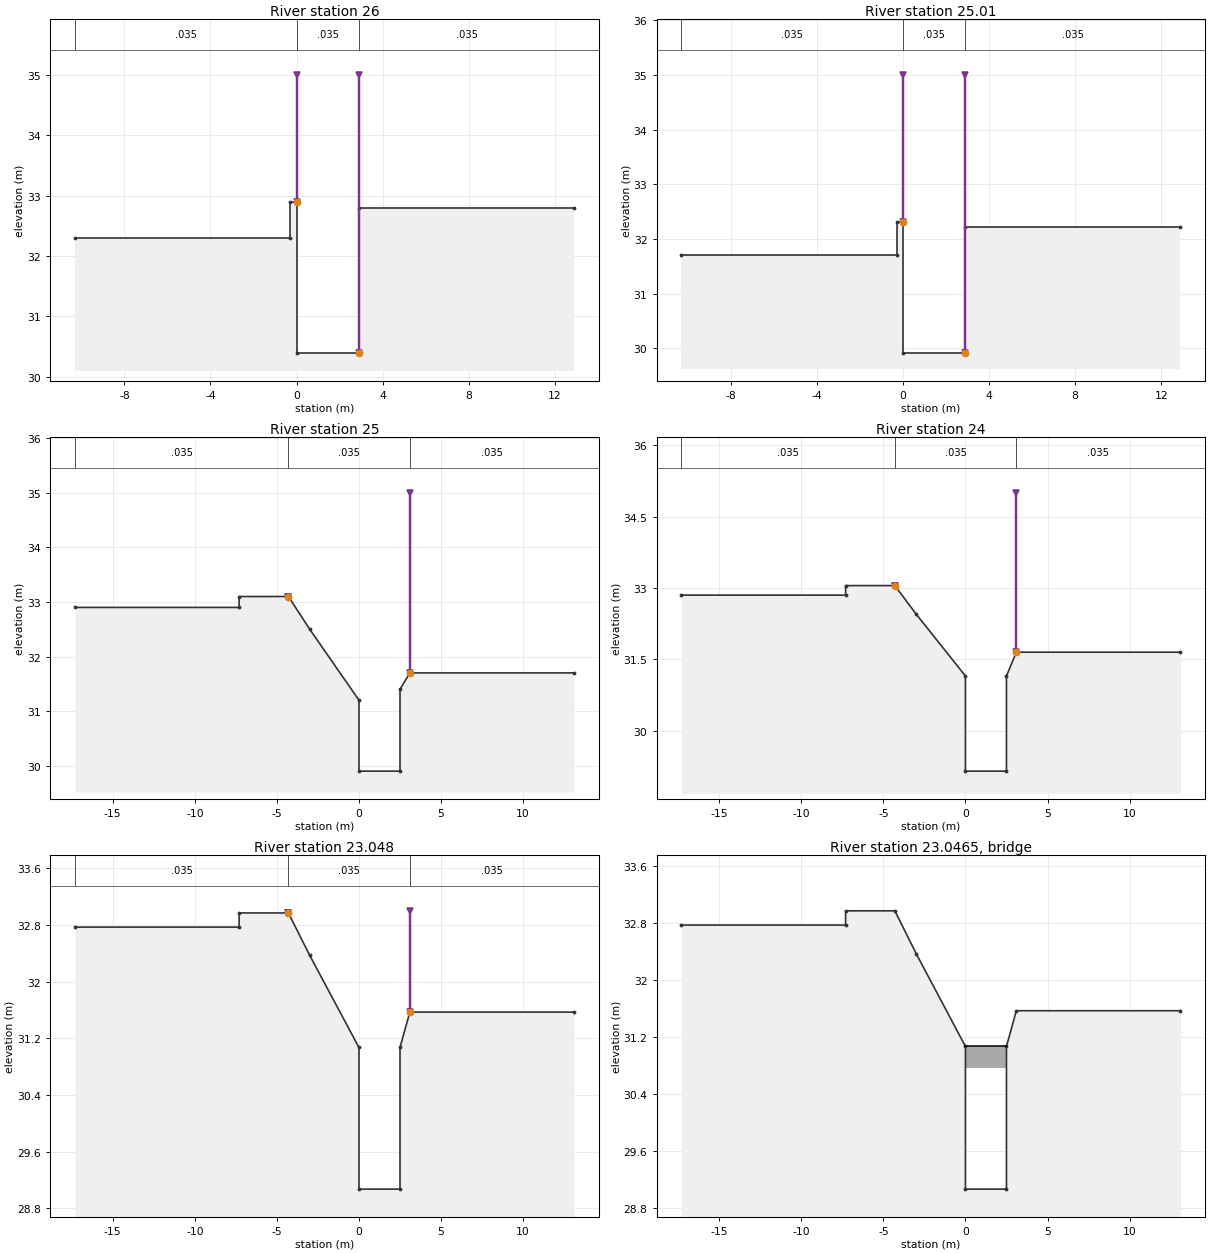
Type RM Length L Ch R = 1 ,26      ,10,10,10
#Sta/Elev= 8
   -10.3   32.29     -.3   32.29     -.3   32.89       0   32.89       0   30.39
     2.9   30.39     2.9   32.79    12.9   32.79
#Mann= 3 , 0 , 0
   -10.3    .035       0       0    .035       0     2.9    .035       0
Levee=-1,0,35,-1,2.9,35,,
Bank Sta=0,2.9
XS Rating Curve= 0
Exp/Cntr=.3,.1

Type RM Length L Ch R = 1 ,25.01   ,10,10,10
#Sta/Elev= 8
   -10.3   31.71     -.3   31.71     -.3   32.31       0   32.31       0   29.91
     2.9   29.91     2.9   32.21    12.9   32.21
#Mann= 3 , 0 , 0
   -10.3    .035       0       0    .035       0     2.9    .035       0
Levee=-1,0,35,-1,2.9,35,,
Bank Sta=0,2.9
XS Rating Curve= 0
Exp/Cntr=.3,.1

Type RM Length L Ch R = 1 ,25      ,50,50,50
#Sta/Elev= 11
   -17.3    32.9    -7.3    32.9    -7.3    33.1    -4.3    33.1      -3    32.5
       0    31.2       0    29.9     2.5    29.9     2.5    31.4     3.1    31.7
    13.1    31.7
#Mann= 3 , 0 , 0
   -17.3    .035       0    -4.3    .035       0     3.1    .035       0
Levee=-1,-4.3,33.1,-1,3.1,35,,
Bank Sta=-4.3,3.1
XS Rating Curve= 0
Exp/Cntr=.3,.1

Type RM Length L Ch R = 1 ,24      ,2,2,2
#Sta/Elev= 11
   -17.3   32.85    -7.3   32.85    -7.3   33.05    -4.3   33.05      -3   32.45
       0   31.15       0   29.15     2.5   29.15     2.5   31.15     3.1   31.65
    13.1   31.65
#Mann= 3 , 0 , 0
   -17.3    .035       0    -4.3    .035       0     3.1    .035       0
Levee=-1,-4.3,33.05,-1,3.1,35,,
Bank Sta=-4.3,3.1
XS Rating Curve= 0
Exp/Cntr=.3,.1

Type RM Length L Ch R = 1 ,23.048  ,3,3,3
#Sta/Elev= 11
   -17.3   32.77    -7.3   32.77    -7.3   32.97    -4.3   32.97      -3   32.37
       0   31.07       0   29.07     2.5   29.07     2.5   31.07     3.1   31.57
    13.1   31.57
#Mann= 3 , 0 , 0
   -17.3    .035       0    -4.3    .035       0     3.1    .035       0
Levee=-1,-4.3,32.97,-1,3.1,33,,
Bank Sta=-4.3,3.1
XS Rating Curve= 0
Exp/Cntr=.3,.1

Type RM Length L Ch R = 3 ,23.0465 ,,,
Bridge Culvert--1,0,-1,-1, 0
Deck Dist Width WeirC Skew NumUp NumDn MinLoCord MaxHiCord MaxSubmerge Is_Ogee
.001,2.999,1.44,0, 2, 2, , , .95, 0, 0,0,,
       0     2.5
   31.07   31.07
   30.77   30.77
       0     2.5
   31.07   31.07
   30.77   30.77
BR Coef=-1 , 0 , 0 ,, 0 ,,,.8,-1,,0,
WSPro=,,,, 1 ,,,, 0 ,,,, 0 ,,,,-1 ,-1 ,-1 , 0 , 0 , 0 , 0 , 0
BC Design=,, 0 ,, 0 ,,,,,,

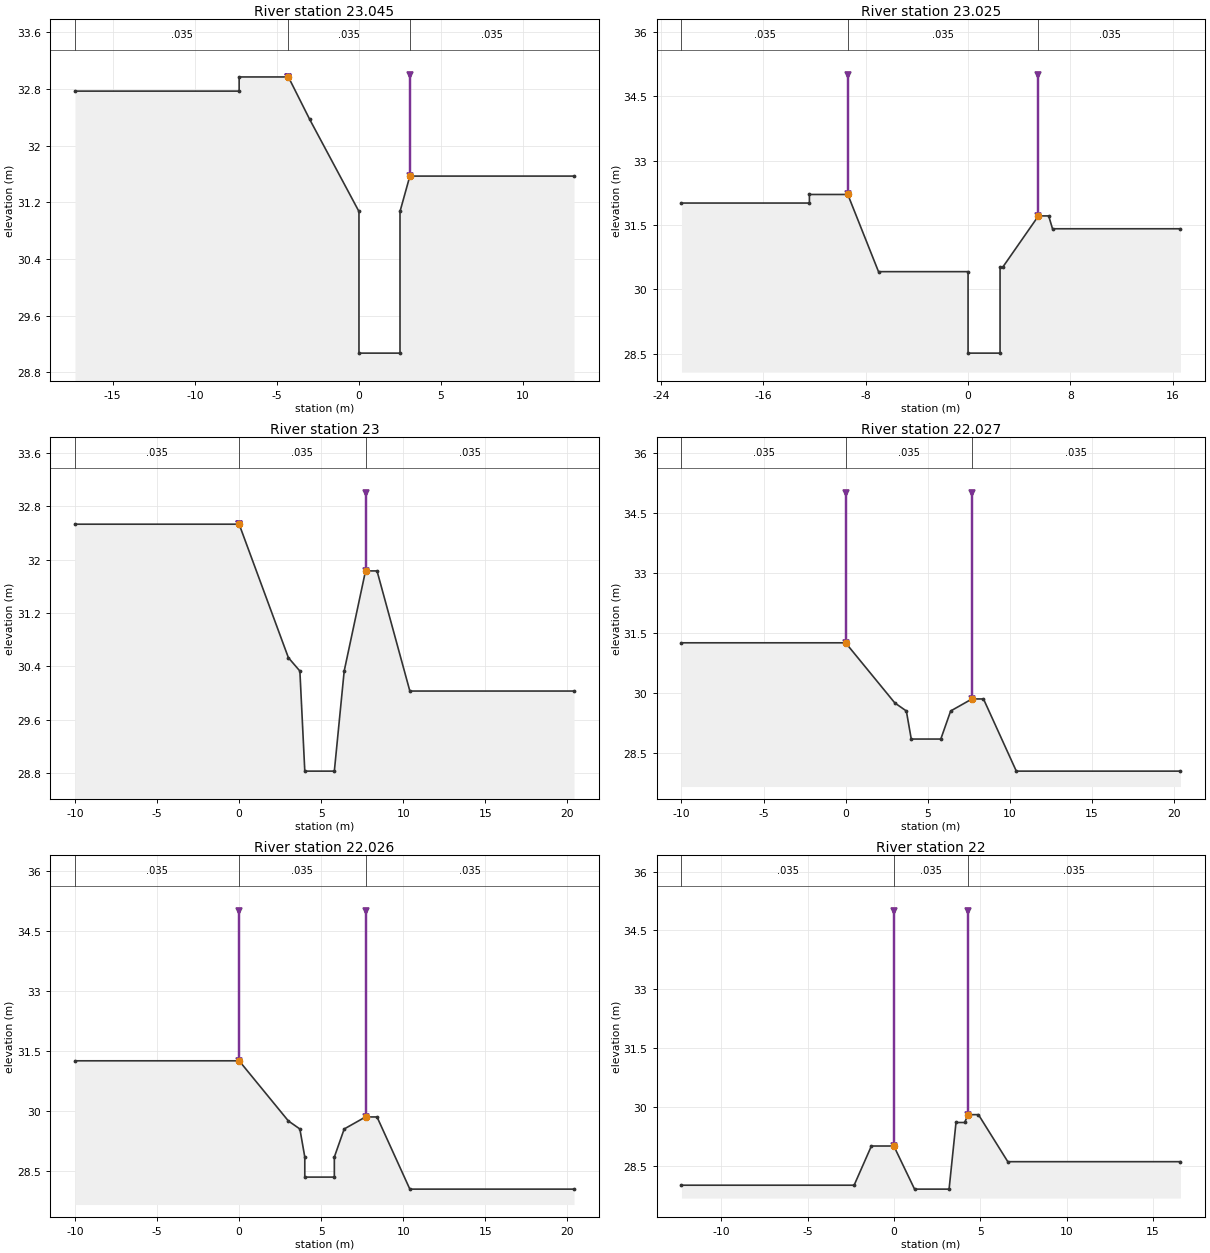
Type RM Length L Ch R = 1 ,23.045  ,23,23,23
#Sta/Elev= 11
   -17.3   32.77    -7.3   32.77    -7.3   32.97    -4.3   32.97      -3   32.37
       0   31.07       0   29.07     2.5   29.07     2.5   31.07     3.1   31.57
    13.1   31.57
#Mann= 3 , 0 , 0
   -17.3    .035       0    -4.3    .035       0     3.1    .035       0
Levee=-1,-4.3,32.97,-1,3.1,33,,
Bank Sta=-4.3,3.1
XS Rating Curve= 0
Exp/Cntr=.3,.1

Type RM Length L Ch R = 1 ,23.025  ,25,25,25
#Sta/Elev= 14
   -22.4   32.01   -12.4   32.01   -12.4   32.21    -9.4   32.21      -7   30.41
       0   30.41       0   28.51     2.5   28.51     2.5   30.51     2.7   30.51
     5.5   31.71     6.3   31.71     6.6   31.41    16.6   31.41
#Mann= 3 , 0 , 0
   -22.4    .035       0    -9.4    .035       0     5.5    .035       0
Levee=-1,-9.4,35,-1,5.5,35,,
Bank Sta=-9.4,5.5
XS Rating Curve= 0
Exp/Cntr=.3,.1

Type RM Length L Ch R = 1 ,23      ,23,23,23
#Sta/Elev= 11
     -10   32.53       0   32.53       3   30.53     3.7   30.33       4   28.83
     5.8   28.83     6.4   30.33     7.7   31.83     8.4   31.83    10.4   30.03
    20.4   30.03
#Mann= 3 , 0 , 0
     -10    .035       0       0    .035       0     7.7    .035       0
Levee=-1,0,32.53,-1,7.7,33,,
Bank Sta=0,7.7
XS Rating Curve= 0
Exp/Cntr=.3,.1

Type RM Length L Ch R = 1 ,22.027  ,1,1,1
#Sta/Elev= 11
     -10   31.26       0   31.26       3   29.76     3.7   29.56       4   28.86
     5.8   28.86     6.4   29.56     7.7   29.86     8.4   29.86    10.4   28.06
    20.4   28.06
#Mann= 3 , 0 , 0
     -10    .035       0       0    .035       0     7.7    .035       0
Levee=-1,0,35,-1,7.7,35,,
Bank Sta=0,7.7
XS Rating Curve= 0
Exp/Cntr=.3,.1

Type RM Length L Ch R = 1 ,22.026  ,26,26,26
#Sta/Elev= 13
     -10   31.26       0   31.26       3   29.76     3.7   29.56       4   28.86
       4   28.36     5.8   28.36     5.8   28.86     6.4   29.56     7.7   29.86
     8.4   29.86    10.4   28.06    20.4   28.06
#Mann= 3 , 0 , 0
     -10    .035       0       0    .035       0     7.7    .035       0
Levee=-1,0,35,-1,7.7,35,,
Bank Sta=0,7.7
XS Rating Curve= 0
Exp/Cntr=.3,.1

Type RM Length L Ch R = 1 ,22      ,21,21,21
#Sta/Elev= 12
   -12.3      28    -2.3      28    -1.3      29       0      29     1.2    27.9
     3.2    27.9     3.6    29.6     4.1    29.6     4.3    29.8     4.9    29.8
     6.6    28.6    16.6    28.6
#Mann= 3 , 0 , 0
   -12.3    .035       0       0    .035       0     4.3    .035       0
Levee=-1,0,35,-1,4.3,35,,
Bank Sta=0,4.3
XS Rating Curve= 0
Exp/Cntr=.3,.1