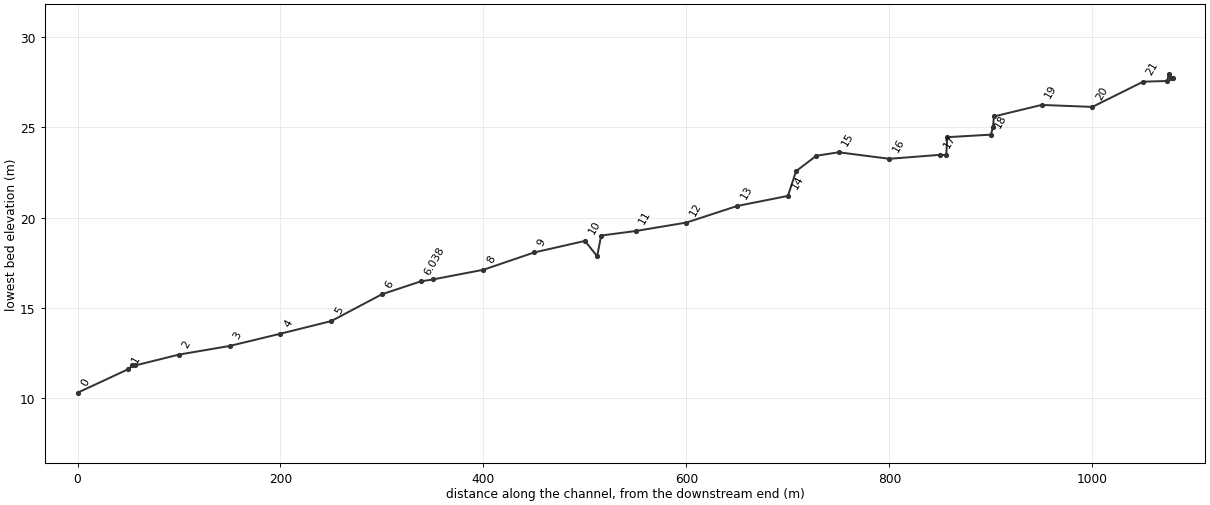
HEC-RAS study DAEKOK.prj: DAEKOK

--- DAEKOK.g01 (geometry) --- (continued)

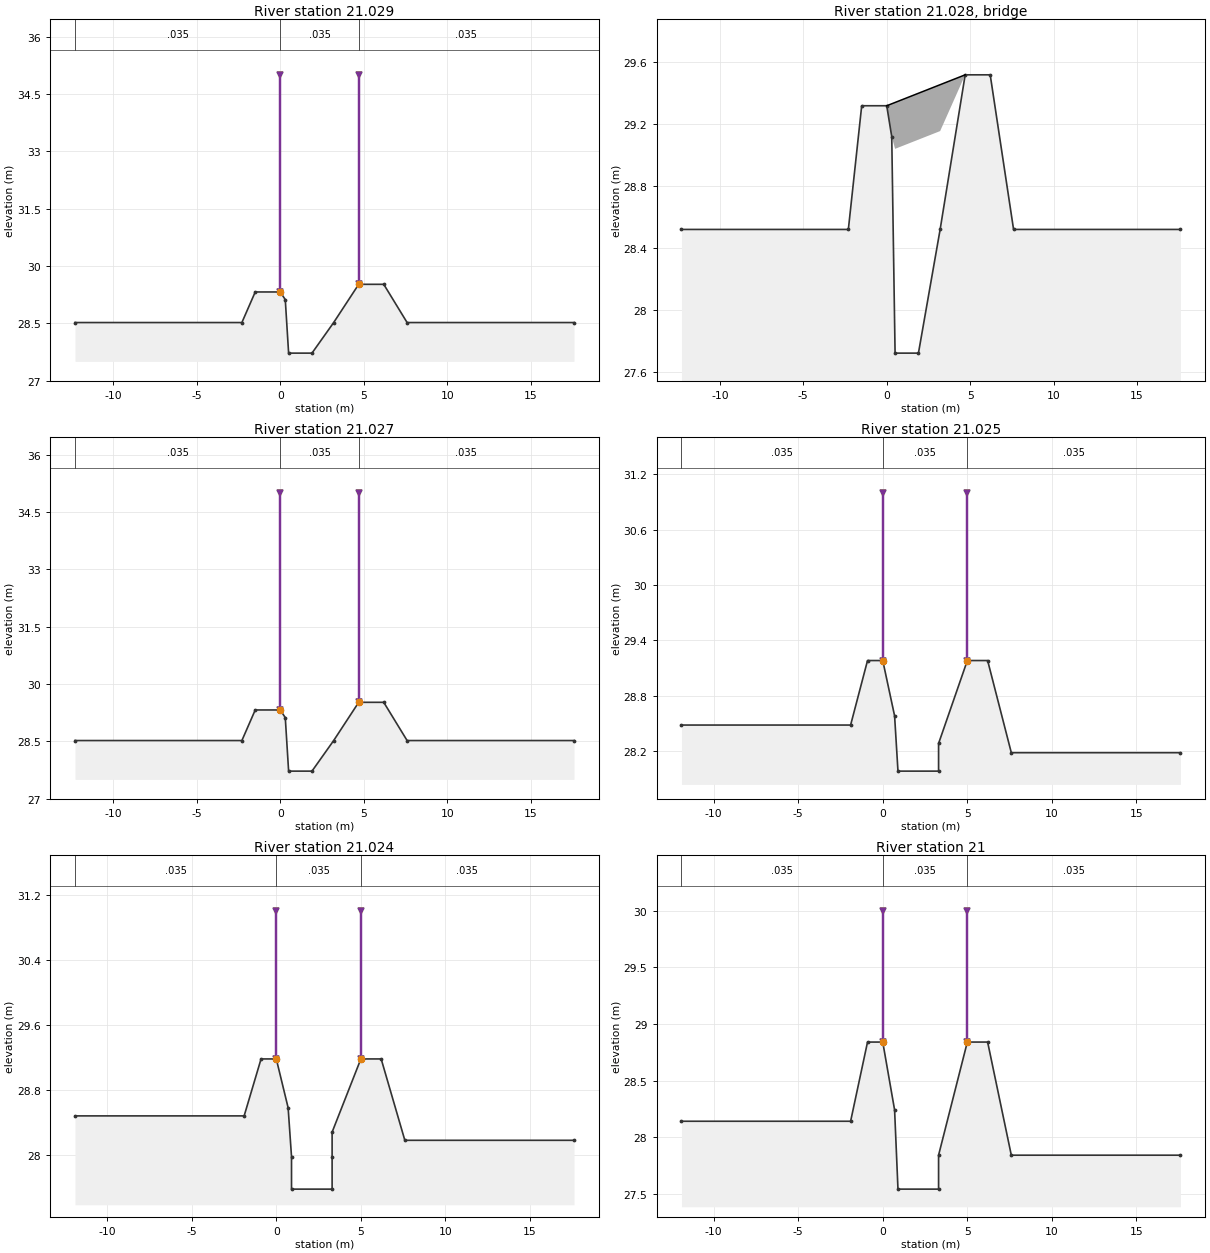
Type RM Length L Ch R = 1 ,21.029  ,2,2,2
#Sta/Elev= 12
   -12.3   28.52    -2.3   28.52    -1.5   29.32       0   29.32      .3   29.12
      .5   27.72     1.9   27.72     3.2   28.52     4.7   29.52     6.2   29.52
     7.6   28.52    17.6   28.52
#Mann= 3 , 0 , 0
   -12.3    .035       0       0    .035       0     4.7    .035       0
Levee=-1,0,35,-1,4.7,35,,
Bank Sta=0,4.7
XS Rating Curve= 0
Exp/Cntr=.3,.1

Type RM Length L Ch R = 3 ,21.028  ,,,
Bridge Culvert--1,0,-1,-1, 0
Deck Dist Width WeirC Skew NumUp NumDn MinLoCord MaxHiCord MaxSubmerge Is_Ogee
.001,1.999,1.44,0, 2, 2, , , .95, 0, 0,0,,
       0     4.7
   29.32   29.52
   29.02   29.22
       0     4.7
   29.32   29.52
   29.02   29.22
BR Coef=-1 , 0 , 0 ,, 0 ,,,.8,-1,,0,
WSPro=,,,, 1 ,,,, 0 ,,,, 0 ,,,,-1 ,-1 ,-1 , 0 , 0 , 0 , 0 , 0
BC Design=,, 0 ,, 0 ,,,,,,

Type RM Length L Ch R = 1 ,21.027  ,2,2,2
#Sta/Elev= 12
   -12.3   28.52    -2.3   28.52    -1.5   29.32       0   29.32      .3   29.12
      .5   27.72     1.9   27.72     3.2   28.52     4.7   29.52     6.2   29.52
     7.6   28.52    17.6   28.52
#Mann= 3 , 0 , 0
   -12.3    .035       0       0    .035       0     4.7    .035       0
Levee=-1,0,35,-1,4.7,35,,
Bank Sta=0,4.7
XS Rating Curve= 0
Exp/Cntr=.3,.1

Type RM Length L Ch R = 1 ,21.025  ,1,1,1
#Sta/Elev= 12
   -11.9   28.48    -1.9   28.48     -.9   29.18       0   29.18      .7   28.58
      .9   27.98     3.3   27.98     3.3   28.28       5   29.18     6.2   29.18
     7.6   28.18    17.6   28.18
#Mann= 3 , 0 , 0
   -11.9    .035       0       0    .035       0       5    .035       0
Levee=-1,0,31,-1,5,31,,
Bank Sta=0,5
XS Rating Curve= 0
Exp/Cntr=.3,.1

Type RM Length L Ch R = 1 ,21.024  ,24,24,24
#Sta/Elev= 14
   -11.9   28.48    -1.9   28.48     -.9   29.18       0   29.18      .7   28.58
      .9   27.98      .9   27.58     3.3   27.58     3.3   27.98     3.3   28.28
       5   29.18     6.2   29.18     7.6   28.18    17.6   28.18
#Mann= 3 , 0 , 0
   -11.9    .035       0       0    .035       0       5    .035       0
Levee=-1,0,31,-1,5,31,,
Bank Sta=0,5
XS Rating Curve= 0
Exp/Cntr=.3,.1

Type RM Length L Ch R = 1 ,21      ,50,50,50
#Sta/Elev= 12
   -11.9   28.14    -1.9   28.14     -.9   28.84       0   28.84      .7   28.24
      .9   27.54     3.3   27.54     3.3   27.84       5   28.84     6.2   28.84
     7.6   27.84    17.6   27.84
#Mann= 3 , 0 , 0
   -11.9    .035       0       0    .035       0       5    .035       0
Levee=-1,0,30,-1,5,30,,
Bank Sta=0,5
XS Rating Curve= 0
Exp/Cntr=.3,.1

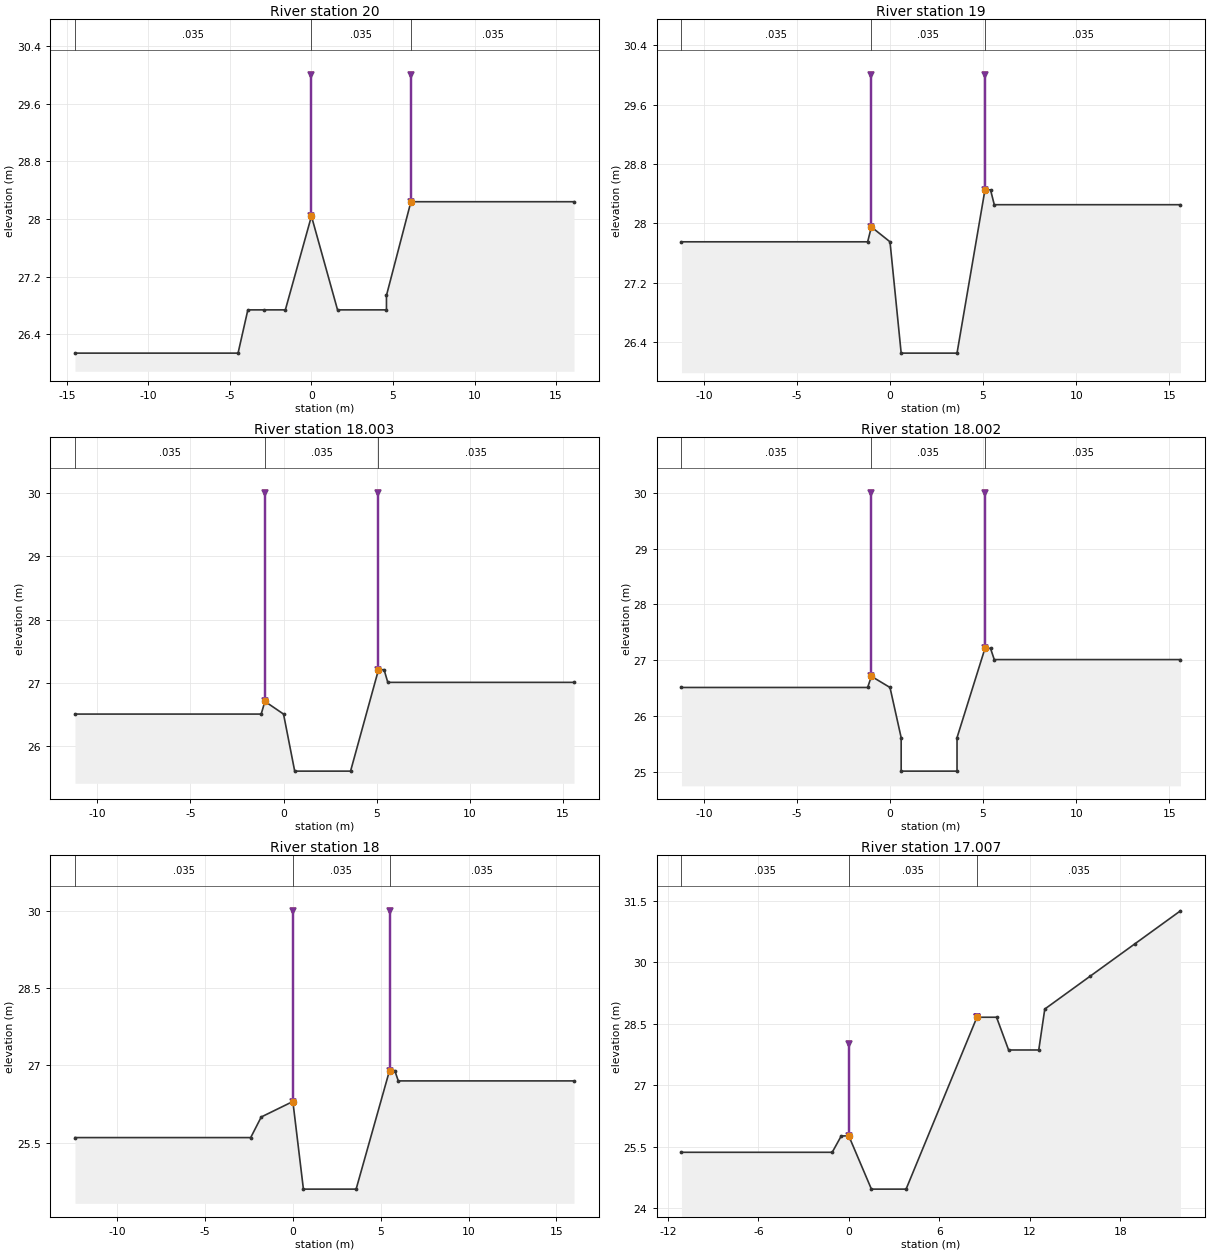
Type RM Length L Ch R = 1 ,20      ,50,50,50
#Sta/Elev= 11
   -14.5   26.14    -4.5   26.14    -3.9   26.74    -2.9   26.74    -1.6   26.74
       0   28.04     1.6   26.74     4.6   26.74     4.6   26.94     6.1   28.24
    16.1   28.24
#Mann= 3 , 0 , 0
   -14.5    .035       0       0    .035       0     6.1    .035       0
Levee=-1,0,30,-1,6.1,30,,
Bank Sta=0,6.1
XS Rating Curve= 0
Exp/Cntr=.3,.1

Type RM Length L Ch R = 1 ,19      ,47,47,47
#Sta/Elev= 10
   -11.2   27.75    -1.2   27.75      -1   27.95       0   27.75      .6   26.25
     3.6   26.25     5.1   28.45     5.4   28.45     5.6   28.25    15.6   28.25
#Mann= 3 , 0 , 0
   -11.2    .035       0      -1    .035       0     5.1    .035       0
Levee=-1,-1,30,-1,5.1,30,,
Bank Sta=-1,5.1
XS Rating Curve= 0
Exp/Cntr=.3,.1

Type RM Length L Ch R = 1 ,18.003  ,1,1,1
#Sta/Elev= 10
   -11.2   26.51    -1.2   26.51      -1   26.71       0   26.51      .6   25.61
     3.6   25.61     5.1   27.21     5.4   27.21     5.6   27.01    15.6   27.01
#Mann= 3 , 0 , 0
   -11.2    .035       0      -1    .035       0     5.1    .035       0
Levee=-1,-1,30,-1,5.1,30,,
Bank Sta=-1,5.1
XS Rating Curve= 0
Exp/Cntr=.3,.1

Type RM Length L Ch R = 1 ,18.002  ,2,2,2
#Sta/Elev= 12
   -11.2   26.51    -1.2   26.51      -1   26.71       0   26.51      .6   25.61
      .6   25.01     3.6   25.01     3.6   25.61     5.1   27.21     5.4   27.21
     5.6   27.01    15.6   27.01
#Mann= 3 , 0 , 0
   -11.2    .035       0      -1    .035       0     5.1    .035       0
Levee=-1,-1,30,-1,5.1,30,,
Bank Sta=-1,5.1
XS Rating Curve= 0
Exp/Cntr=.3,.1

Type RM Length L Ch R = 1 ,18      ,43,43,43
#Sta/Elev= 10
   -12.4    25.6    -2.4    25.6    -1.8      26       0    26.3      .6    24.6
     3.6    24.6     5.5    26.9     5.8    26.9       6    26.7      16    26.7
#Mann= 3 , 0 , 0
   -12.4    .035       0       0    .035       0     5.5    .035       0
Levee=-1,0,30,-1,5.5,30,,
Bank Sta=0,5.5
XS Rating Curve= 0
Exp/Cntr=.3,.1

Type RM Length L Ch R = 1 ,17.007  ,1,1,1
#Sta/Elev= 14
   -11.1   25.36    -1.1   25.36     -.5   25.76       0   25.76     1.5   24.46
     3.8   24.46     8.5   28.66     9.8   28.66    10.6   27.86    12.6   27.86
      13   28.86      16   29.66      19   30.46      22   31.26
#Mann= 3 , 0 , 0
   -11.1    .035       0       0    .035       0     8.5    .035       0
Levee=-1,0,28,-1,8.5,28.66,,
Bank Sta=0,8.5
XS Rating Curve= 0
Exp/Cntr=.3,.1

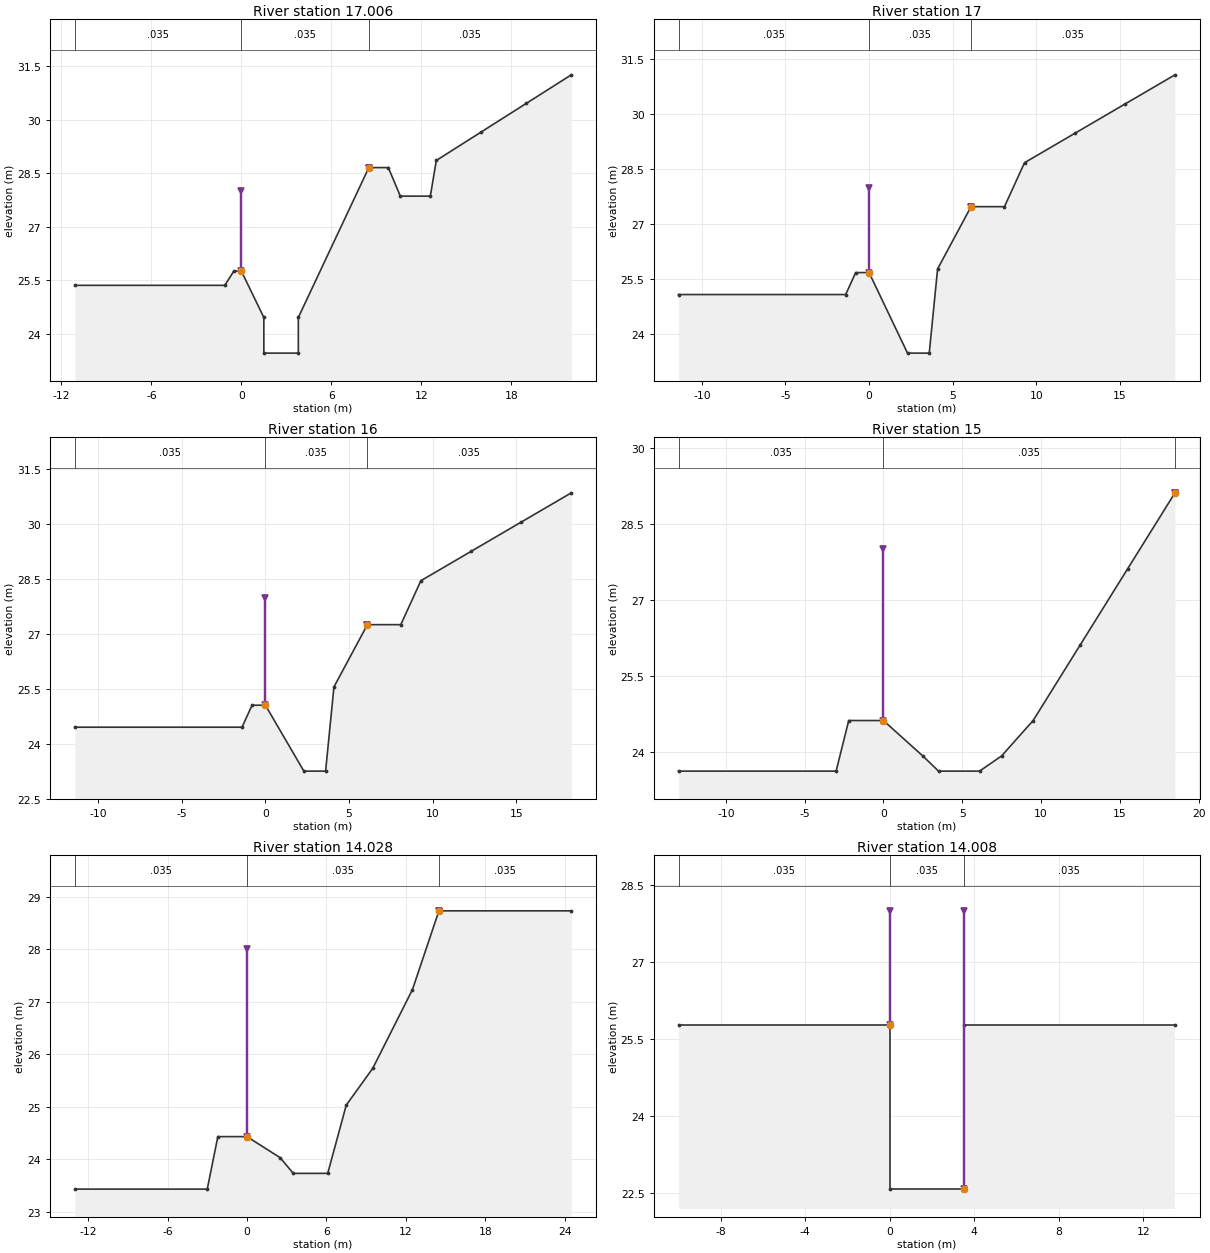
Type RM Length L Ch R = 1 ,17.006  ,6,6,6
#Sta/Elev= 16
   -11.1   25.36    -1.1   25.36     -.5   25.76       0   25.76     1.5   24.46
     1.5   23.46     3.8   23.46     3.8   24.46     8.5   28.66     9.8   28.66
    10.6   27.86    12.6   27.86      13   28.86      16   29.66      19   30.46
      22   31.26
#Mann= 3 , 0 , 0
   -11.1    .035       0       0    .035       0     8.5    .035       0
Levee=-1,0,28,-1,8.5,28.66,,
Bank Sta=0,8.5
XS Rating Curve= 0
Exp/Cntr=.3,.1

Type RM Length L Ch R = 1 ,17      ,50,50,50
#Sta/Elev= 13
   -11.4   25.08    -1.4   25.08     -.8   25.68       0   25.68     2.3   23.48
     3.6   23.48     4.1   25.78     6.1   27.48     8.1   27.48     9.3   28.68
    12.3   29.48    15.3   30.28    18.3   31.08
#Mann= 3 , 0 , 0
   -11.4    .035       0       0    .035       0     6.1    .035       0
Levee=-1,0,28,-1,6.1,27.48,,
Bank Sta=0,6.1
XS Rating Curve= 0
Exp/Cntr=.3,.1

Type RM Length L Ch R = 1 ,16      ,50,50,50
#Sta/Elev= 13
   -11.4   24.46    -1.4   24.46     -.8   25.06       0   25.06     2.3   23.26
     3.6   23.26     4.1   25.56     6.1   27.26     8.1   27.26     9.3   28.46
    12.3   29.26    15.3   30.06    18.3   30.86
#Mann= 3 , 0 , 0
   -11.4    .035       0       0    .035       0     6.1    .035       0
Levee=-1,0,28,-1,6.1,27.26,,
Bank Sta=0,6.1
XS Rating Curve= 0
Exp/Cntr=.3,.1

Type RM Length L Ch R = 1 ,15      ,22,22,22
#Sta/Elev= 12
     -13   23.62      -3   23.62    -2.2   24.62       0   24.62     2.5   23.92
     3.5   23.62     6.1   23.62     7.5   23.92     9.5   24.62    12.5   26.12
    15.5   27.62    18.5   29.12
#Mann= 3 , 0 , 0
     -13    .035       0       0    .035       0    18.5    .035       0
Levee=-1,0,28,-1,18.5,29.12,,
Bank Sta=0,18.5
XS Rating Curve= 0
Exp/Cntr=.3,.1

Type RM Length L Ch R = 1 ,14.028  ,20,20,20
#Sta/Elev= 12
     -13   23.43      -3   23.43    -2.2   24.43       0   24.43     2.5   24.03
     3.5   23.73     6.1   23.73     7.5   25.03     9.5   25.73    12.5   27.23
    14.5   28.73    24.5   28.73
#Mann= 3 , 0 , 0
     -13    .035       0       0    .035       0    14.5    .035       0
Levee=-1,0,28,-1,14.5,28.73,,
Bank Sta=0,14.5
XS Rating Curve= 0
Exp/Cntr=.3,.1

Type RM Length L Ch R = 1 ,14.008  ,8,8,8
#Sta/Elev= 6
     -10   25.77       0   25.77       0   22.57     3.5   22.57     3.5   25.77
    13.5   25.77
#Mann= 3 , 0 , 0
     -10    .035       0       0    .035       0     3.5    .035       0
Levee=-1,0,28,-1,3.5,28,,
Bank Sta=0,3.5
XS Rating Curve= 0
Exp/Cntr=.3,.1

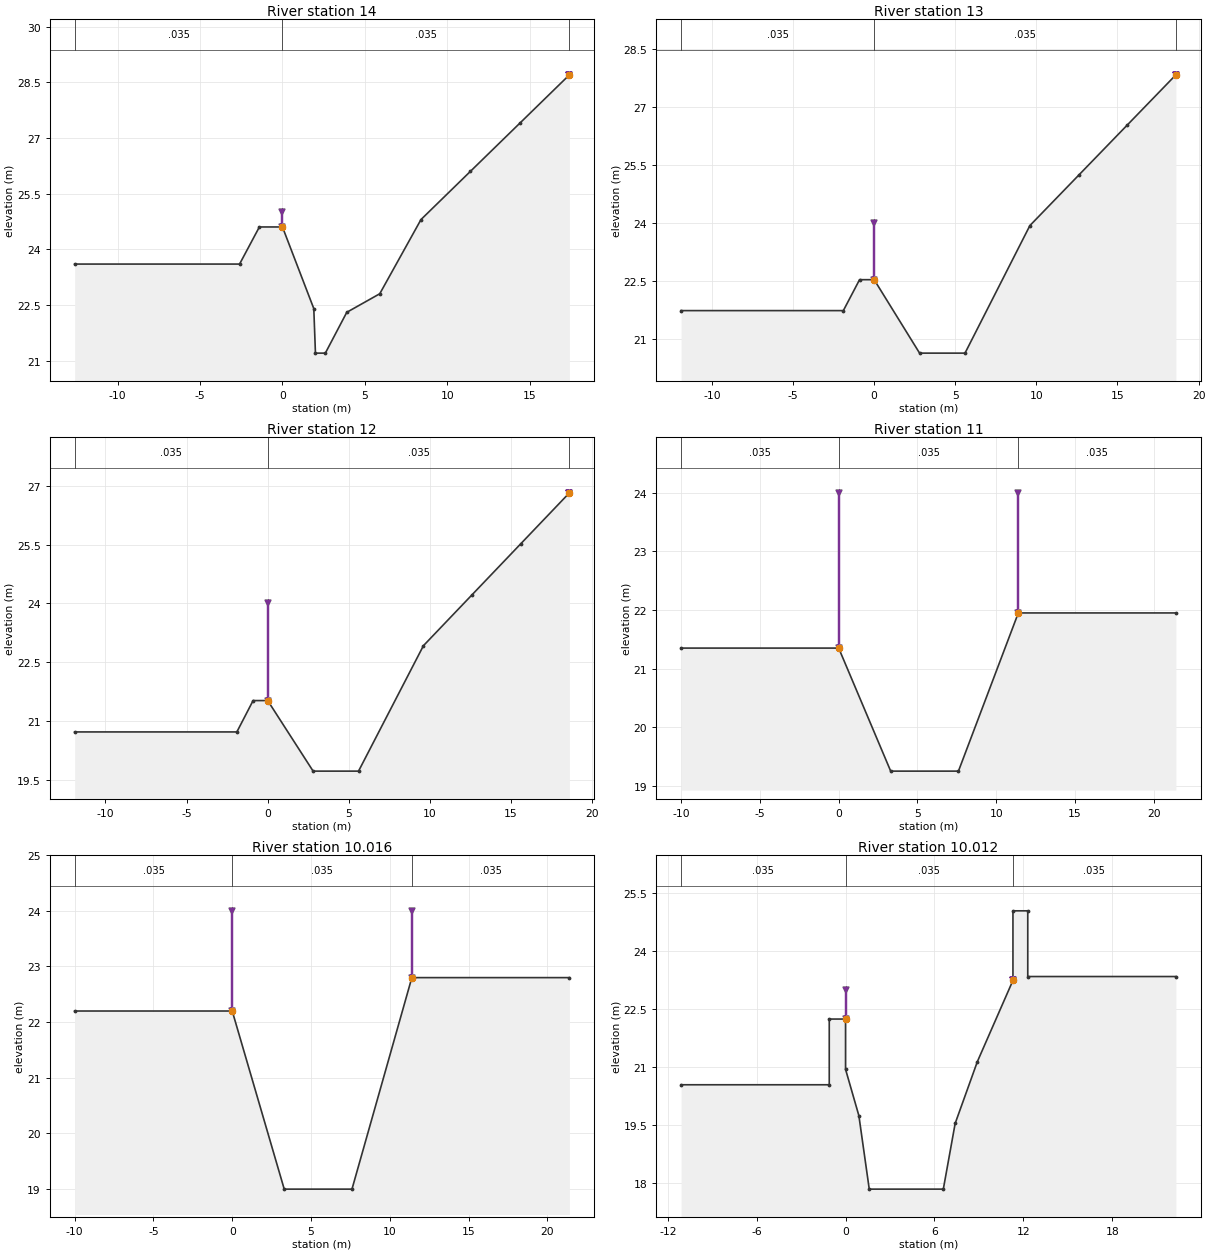
Type RM Length L Ch R = 1 ,14      ,50,50,50
#Sta/Elev= 13
   -12.6    23.6    -2.6    23.6    -1.4    24.6       0    24.6     1.9    22.4
       2    21.2     2.6    21.2     3.9    22.3     5.9    22.8     8.4    24.8
    11.4    26.1    14.4    27.4    17.4    28.7
#Mann= 3 , 0 , 0
   -12.6    .035       0       0    .035       0    17.4    .035       0
Levee=-1,0,25,-1,17.4,28.7,,
Bank Sta=0,17.4
XS Rating Curve= 0
Exp/Cntr=.3,.1

Type RM Length L Ch R = 1 ,13      ,50,50,50
#Sta/Elev= 10
   -11.9   21.74    -1.9   21.74     -.9   22.54       0   22.54     2.8   20.64
     5.6   20.64     9.6   23.94    12.6   25.24    15.6   26.54    18.6   27.84
#Mann= 3 , 0 , 0
   -11.9    .035       0       0    .035       0    18.6    .035       0
Levee=-1,0,24,-1,18.6,27.84,,
Bank Sta=0,18.6
XS Rating Curve= 0
Exp/Cntr=.3,.1

Type RM Length L Ch R = 1 ,12      ,50,50,50
#Sta/Elev= 10
   -11.9   20.72    -1.9   20.72     -.9   21.52       0   21.52     2.8   19.72
     5.6   19.72     9.6   22.92    12.6   24.22    15.6   25.52    18.6   26.82
#Mann= 3 , 0 , 0
   -11.9    .035       0       0    .035       0    18.6    .035       0
Levee=-1,0,24,-1,18.6,26.82,,
Bank Sta=0,18.6
XS Rating Curve= 0
Exp/Cntr=.3,.1

Type RM Length L Ch R = 1 ,11      ,34,34,34
#Sta/Elev= 6
     -10   21.35       0   21.35     3.3   19.25     7.6   19.25    11.4   21.95
    21.4   21.95
#Mann= 3 , 0 , 0
     -10    .035       0       0    .035       0    11.4    .035       0
Levee=-1,0,24,-1,11.4,24,,
Bank Sta=0,11.4
XS Rating Curve= 0
Exp/Cntr=.3,.1

Type RM Length L Ch R = 1 ,10.016  ,4,4,4
#Sta/Elev= 6
     -10    22.2       0    22.2     3.3      19     7.6      19    11.4    22.8
    21.4    22.8
#Mann= 3 , 0 , 0
     -10    .035       0       0    .035       0    11.4    .035       0
Levee=-1,0,24,-1,11.4,24,,
Bank Sta=0,11.4
XS Rating Curve= 0
Exp/Cntr=.3,.1

Type RM Length L Ch R = 1 ,10.012  ,12,12,12
#Sta/Elev= 15
   -11.1   20.55    -1.1   20.55    -1.1   22.25       0   22.25       0   20.95
      .9   19.75     1.6   17.85     6.6   17.85     7.4   19.55     8.9   21.15
    11.3   23.25    11.3   25.05    12.3   25.05    12.3   23.35    22.3   23.35
#Mann= 3 , 0 , 0
   -11.1    .035       0       0    .035       0    11.3    .035       0
Levee=-1,0,23,-1,11.3,23.25,,
Bank Sta=0,11.3
XS Rating Curve= 0
Exp/Cntr=.3,.1

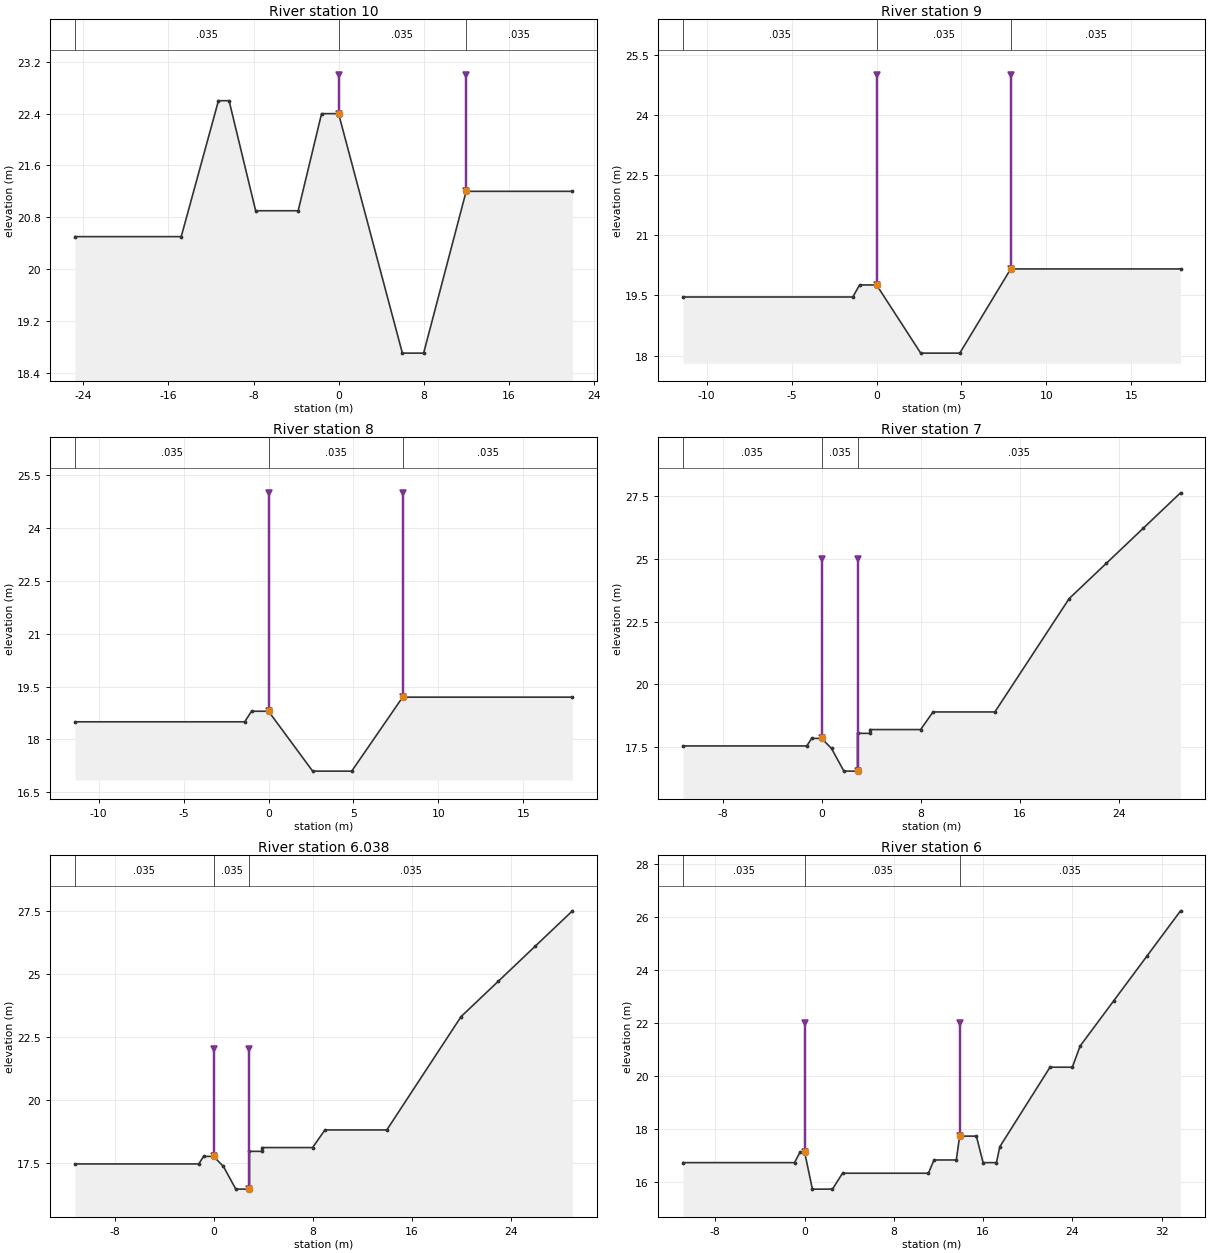
Type RM Length L Ch R = 1 ,10      ,50,50,50
#Sta/Elev= 12
   -24.8    20.5   -14.8    20.5   -11.3    22.6   -10.3    22.6    -7.8    20.9
    -3.8    20.9    -1.6    22.4       0    22.4       6    18.7       8    18.7
      12    21.2      22    21.2
#Mann= 3 , 0 , 0
   -24.8    .035       0       0    .035       0      12    .035       0
Levee=-1,0,23,-1,12,23,,
Bank Sta=0,12
XS Rating Curve= 0
Exp/Cntr=.3,.1

Type RM Length L Ch R = 1 ,9       ,50,50,50
#Sta/Elev= 8
   -11.4   19.46    -1.4   19.46      -1   19.76       0   19.76     2.6   18.06
     4.9   18.06     7.9   20.16    17.9   20.16
#Mann= 3 , 0 , 0
   -11.4    .035       0       0    .035       0     7.9    .035       0
Levee=-1,0,25,-1,7.9,25,,
Bank Sta=0,7.9
XS Rating Curve= 0
Exp/Cntr=.3,.1

Type RM Length L Ch R = 1 ,8       ,50,50,50
#Sta/Elev= 8
   -11.4    18.5    -1.4    18.5      -1    18.8       0    18.8     2.6    17.1
     4.9    17.1     7.9    19.2    17.9    19.2
#Mann= 3 , 0 , 0
   -11.4    .035       0       0    .035       0     7.9    .035       0
Levee=-1,0,25,-1,7.9,25,,
Bank Sta=0,7.9
XS Rating Curve= 0
Exp/Cntr=.3,.1

Type RM Length L Ch R = 1 ,7       ,12,12,12
#Sta/Elev= 17
   -11.2   17.56    -1.2   17.56     -.8   17.86       0   17.86      .8   17.46
     1.8   16.56     2.9   16.56     2.9   18.06     3.9   18.06     3.9   18.21
       8   18.21       9   18.91      14   18.91      20   23.41      23   24.81
      26   26.21      29   27.61
#Mann= 3 , 0 , 0
   -11.2    .035       0       0    .035       0     2.9    .035       0
Levee=-1,0,25,-1,2.9,25,,
Bank Sta=0,2.9
XS Rating Curve= 0
Exp/Cntr=.3,.1

Type RM Length L Ch R = 1 ,6.038   ,38,38,38
#Sta/Elev= 17
   -11.2   17.45    -1.2   17.45     -.8   17.75       0   17.75      .8   17.35
     1.8   16.45     2.9   16.45     2.9   17.95     3.9   17.95     3.9    18.1
       8    18.1       9    18.8      14    18.8      20    23.3      23    24.7
      26    26.1      29    27.5
#Mann= 3 , 0 , 0
   -11.2    .035       0       0    .035       0     2.9    .035       0
Levee=-1,0,22,-1,2.9,22,,
Bank Sta=0,2.9
XS Rating Curve= 0
Exp/Cntr=.3,.1

Type RM Length L Ch R = 1 ,6       ,50,50,50
#Sta/Elev= 21
   -10.9   16.74     -.9   16.74     -.4   17.14       0   17.14      .7   15.74
     2.5   15.74     3.4   16.34    11.1   16.34    11.6   16.84    13.6   16.84
    13.9   17.74    15.4   17.74      16   16.74    17.2   16.74    17.5   17.34
      22   20.34      24   20.34    24.7   21.14    27.7   22.84    30.7   24.54
    33.7   26.24
#Mann= 3 , 0 , 0
   -10.9    .035       0       0    .035       0    13.9    .035       0
Levee=-1,0,22,-1,13.9,22,,
Bank Sta=0,13.9
XS Rating Curve= 0
Exp/Cntr=.3,.1

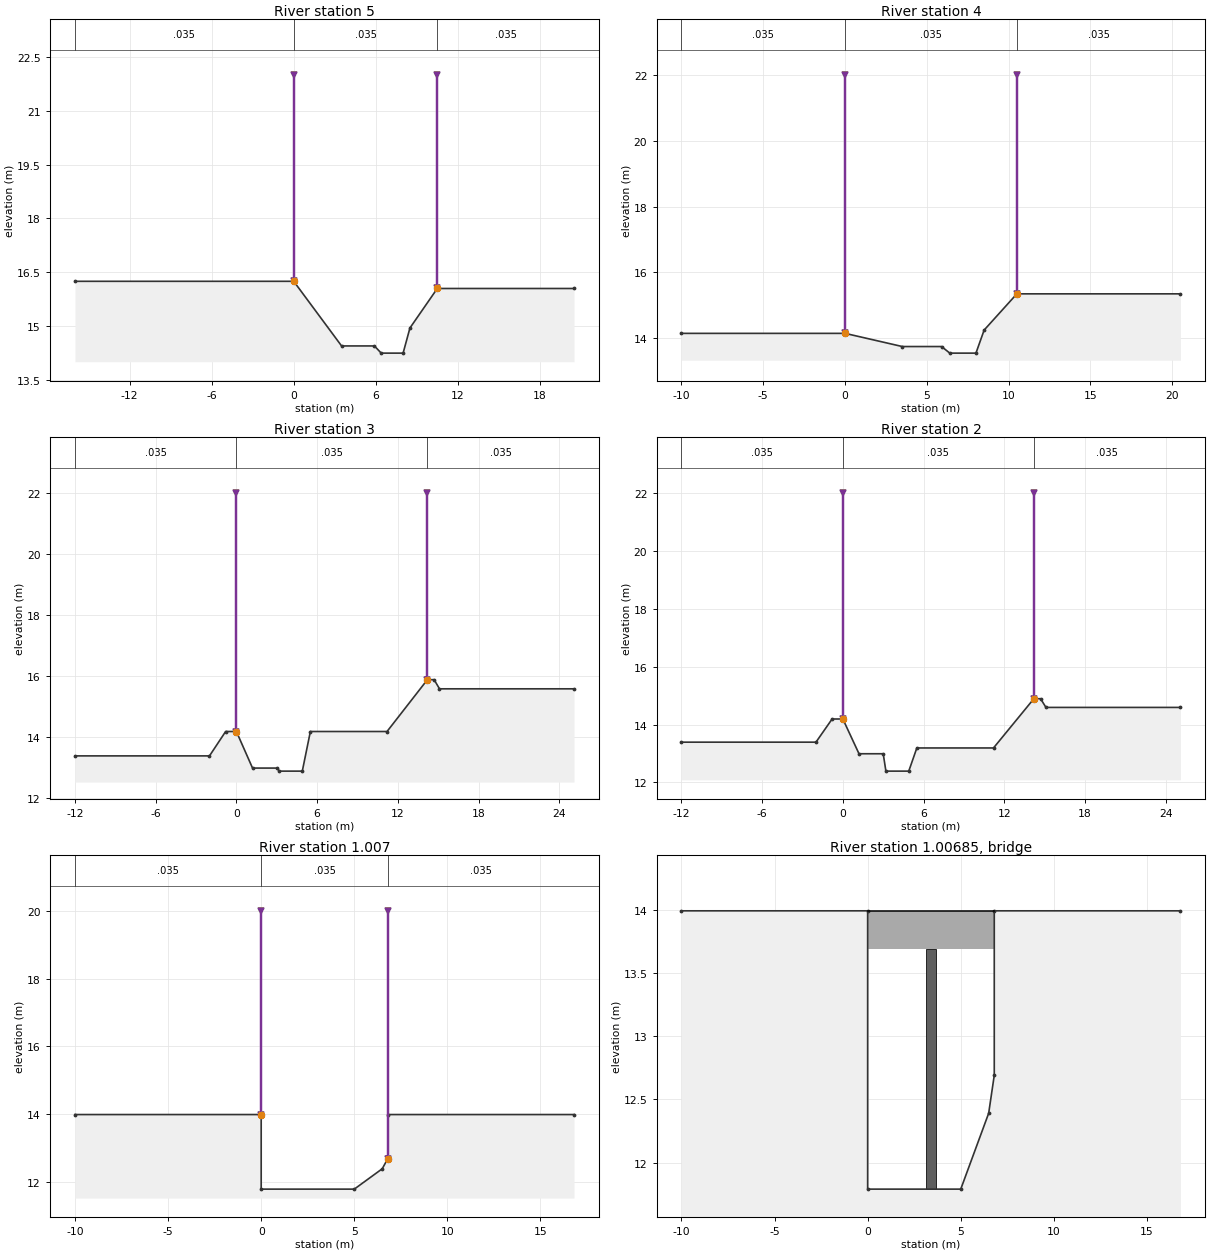
Type RM Length L Ch R = 1 ,5       ,50,50,50
#Sta/Elev= 9
     -16   16.25       0   16.25     3.5   14.45     5.9   14.45     6.4   14.25
       8   14.25     8.5   14.95    10.5   16.05    20.5   16.05
#Mann= 3 , 0 , 0
     -16    .035       0       0    .035       0    10.5    .035       0
Levee=-1,0,22,-1,10.5,22,,
Bank Sta=0,10.5
XS Rating Curve= 0
Exp/Cntr=.3,.1

Type RM Length L Ch R = 1 ,4       ,50,50,50
#Sta/Elev= 9
     -10   14.15       0   14.15     3.5   13.75     5.9   13.75     6.4   13.55
       8   13.55     8.5   14.25    10.5   15.35    20.5   15.35
#Mann= 3 , 0 , 0
     -10    .035       0       0    .035       0    10.5    .035       0
Levee=-1,0,22,-1,10.5,22,,
Bank Sta=0,10.5
XS Rating Curve= 0
Exp/Cntr=.3,.1

Type RM Length L Ch R = 1 ,3       ,50,50,50
#Sta/Elev= 14
     -12   13.37      -2   13.37     -.8   14.17       0   14.17     1.2   12.97
       3   12.97     3.2   12.87     4.9   12.87     5.5   14.17    11.2   14.17
    14.2   15.87    14.7   15.87    15.1   15.57    25.1   15.57
#Mann= 3 , 0 , 0
     -12    .035       0       0    .035       0    14.2    .035       0
Levee=-1,0,22,-1,14.2,22,,
Bank Sta=0,14.2
XS Rating Curve= 0
Exp/Cntr=.3,.1

Type RM Length L Ch R = 1 ,2       ,43,43,43
#Sta/Elev= 14
     -12   13.39      -2   13.39     -.8   14.19       0   14.19     1.2   12.99
       3   12.99     3.2   12.39     4.9   12.39     5.5   13.19    11.2   13.19
    14.2   14.89    14.7   14.89    15.1   14.59    25.1   14.59
#Mann= 3 , 0 , 0
     -12    .035       0       0    .035       0    14.2    .035       0
Levee=-1,0,22,-1,14.2,22,,
Bank Sta=0,14.2
XS Rating Curve= 0
Exp/Cntr=.3,.1

Type RM Length L Ch R = 1 ,1.007   ,3,3,3
#Sta/Elev= 8
     -10   13.99       0   13.99       0   11.79       5   11.79     6.5   12.39
     6.8   12.69     6.8   13.99    16.8   13.99
#Mann= 3 , 0 , 0
     -10    .035       0       0    .035       0     6.8    .035       0
Levee=-1,0,20,-1,6.8,20,,
Bank Sta=0,6.8
XS Rating Curve= 0
Exp/Cntr=.3,.1

Type RM Length L Ch R = 3 ,1.00685 ,,,
Bridge Culvert--1,0,-1,-1, 0
Deck Dist Width WeirC Skew NumUp NumDn MinLoCord MaxHiCord MaxSubmerge Is_Ogee
.001,2.999,1.44,0, 2, 2, , , .95, 0, 0,0,,
       0     6.8
   13.99   13.99
   13.69   13.69
       0     6.8
   13.99   13.99
   13.69   13.69
Pier Skew, UpSta & Num, DnSta & Num=  ,3.4, 2 ,3.4, 2 , 0 , 0 , 0 ,,
      .5      .5
   11.79    13.9
      .5      .5
   11.79    13.9
BR Coef=-1 , 1 , 1 ,.9, 0 ,,,.8,-1,1.2,0,
WSPro=,,,, 1 ,,,, 0 ,,,, 0 ,,,,-1 ,-1 ,-1 , 0 , 0 , 0 , 0 , 0
BC Design=,, 0 ,, 0 ,,,,,,

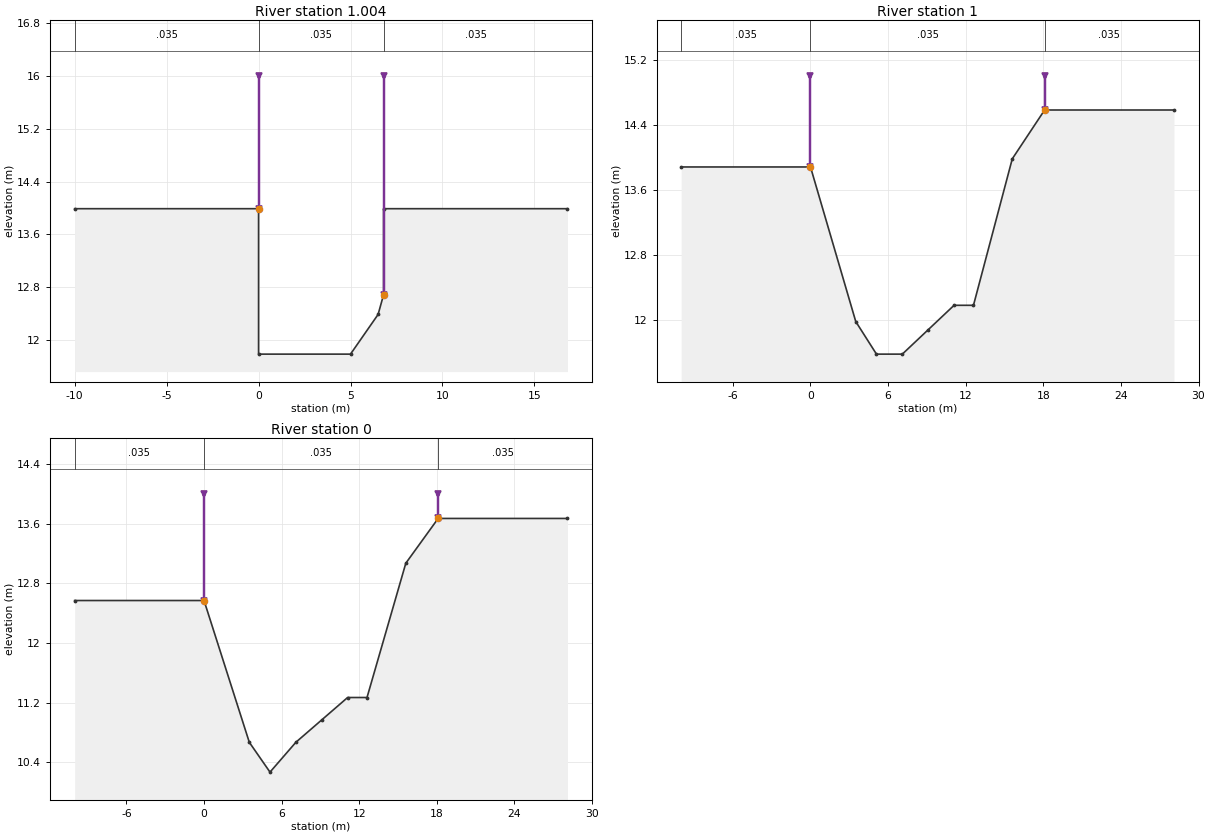
Type RM Length L Ch R = 1 ,1.004   ,4,4,4
#Sta/Elev= 8
     -10   13.99       0   13.99       0   11.79       5   11.79     6.5   12.39
     6.8   12.69     6.8   13.99    16.8   13.99
#Mann= 3 , 0 , 0
     -10    .035       0       0    .035       0     6.8    .035       0
Levee=-1,0,16,-1,6.8,16,,
Bank Sta=0,6.8
XS Rating Curve= 0
Exp/Cntr=.3,.1

Type RM Length L Ch R = 1 ,1       ,50,50,50
#Sta/Elev= 11
     -10   13.88       0   13.88     3.5   11.98     5.1   11.58     7.1   11.58
     9.1   11.88    11.1   12.18    12.6   12.18    15.6   13.98    18.1   14.58
    28.1   14.58
#Mann= 3 , 0 , 0
     -10    .035       0       0    .035       0    18.1    .035       0
Levee=-1,0,15,-1,18.1,15,,
Bank Sta=0,18.1
XS Rating Curve= 0
Exp/Cntr=.3,.1

Type RM Length L Ch R = 1 ,0       ,0,0,0
#Sta/Elev= 11
     -10   12.57       0   12.57     3.5   10.67     5.1   10.27     7.1   10.67
     9.1   10.97    11.1   11.27    12.6   11.27    15.6   13.07    18.1   13.67
    28.1   13.67
#Mann= 3 , 0 , 0
     -10    .035       0       0    .035       0    18.1    .035       0
Levee=-1,0,14,-1,18.1,14,,
Bank Sta=0,18.1
XS Rating Curve= 0
Exp/Cntr=.3,.1

Chan Stop Cuts=-1