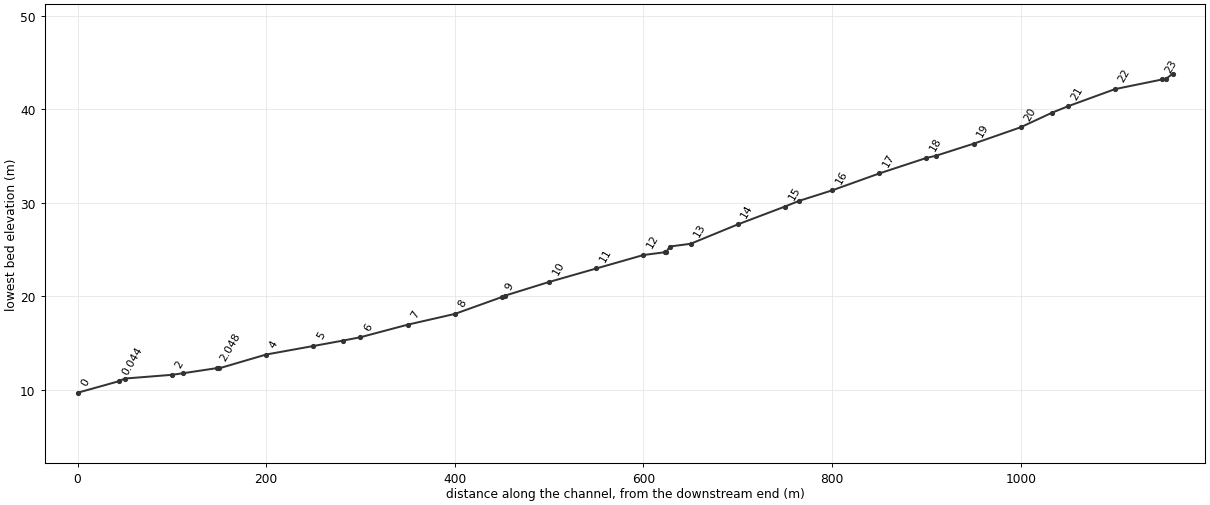
--- WONPYUNG.prj (project) ---

Proj Title=WONPYUNG
Current Plan=p01
Default Exp/Contr=.3,.1
SI Units
Geom File=g01
Flow File=f01
Plan File=p01
Y Axis Title=Elevation
X Axis Title(PF)=Main Channel Distance
X Axis Title(XS)=Station
BEGIN DESCRIPTION:
           BACK WATER COMPUTATION
      APPLICATION OF HEC-2 BY Samju Construction Engineering
      WONPYUNG-STREEM : 30 YR
END DESCRIPTION:
DSS Export Rating Curves= 0
DSS Export Rating Curve Sorted= 0
DSS Export Volume Flow Curves= 0
DXF OffsetX= 0
DXF OffsetY= 0
DXF ScaleX= 1
DXF ScaleY= 10

--- WONPYUNG.p01 (plan) ---

Plan Title=Imported Plan 01
Version=Version 3.0.1  Mar 2001
Short Identifier=Imported Pla
Geom File=g01
Flow File=f01
Subcritical Flow
K Sum by GR= 0
Std Step Tol= 0.003
Critical Tol= 0.003
Num of Std Step Trials= 20
Max Error Tol= 0.1
Flow Tol Ratio= 0.001
Split Flow NTrial= 30
Split Flow Tol= 0.02
Split Flow Ratio= 0.02
Log Output Level= 0
Friction Slope Method= 1
Unsteady Friction Slope Method= 2
Parabolic Critical Depth
Global Vel Dist= 0 , 0 , 0
Global Log Level= 0
CheckData=True
Encroach Param=-1 ,0,0, 0
Computation Interval=1HOUR
Output Interval=1HOUR
Run HTab= 0
Run UNet= 0
Run PostProcess= 0
UNET Theta= 1
UNET ZTol= 0.02
UNET ZSATol= 0.1
UNET MxIter= 20
UNET MaxInSteps= 20
UNET DtIC= 0
UNET DtMin= 0
UNET MaxCRTS= 20
UNET WFStab= 2
UNET SFStab= 1
UNET WFX= 1
UNET SFX= 1
UNET Convert EG Bridges=-1
UNET Use Existing IB Tables=-1
Instantaneous Interval=1HOUR
Write IC File= 0
Write Velocity= 0
Write Detailed= 0

--- WONPYUNG.f01 (steady flow) ---

Flow Title=Imported Flow 01
Version=Version 3.0.1  Mar 2001
Number of Profiles= 1
Profile Names=PF 1
River Rch & RM=RIVER-1,Reach-1         ,23.011
      75
River Rch & RM=WONPYUNG,WONPYUNG        ,23.011
      75
Boundary for River Rch & Prof#=WONPYUNG,WONPYUNG        , 1
Up Type= 0
Dn Type= 3
Dn Slope=.0109
DSS Import GetInterval= 0
DSS Import GetPeak= 0
DSS Import FillOption= 0

--- WONPYUNG.g01 (geometry) ---

Geom Title=Imported Geom 01
Version=Version 3.0.1  Mar 2001

River Reach=WONPYUNG        ,WONPYUNG
Reach XY= 2
              .5             .95              .5             .05

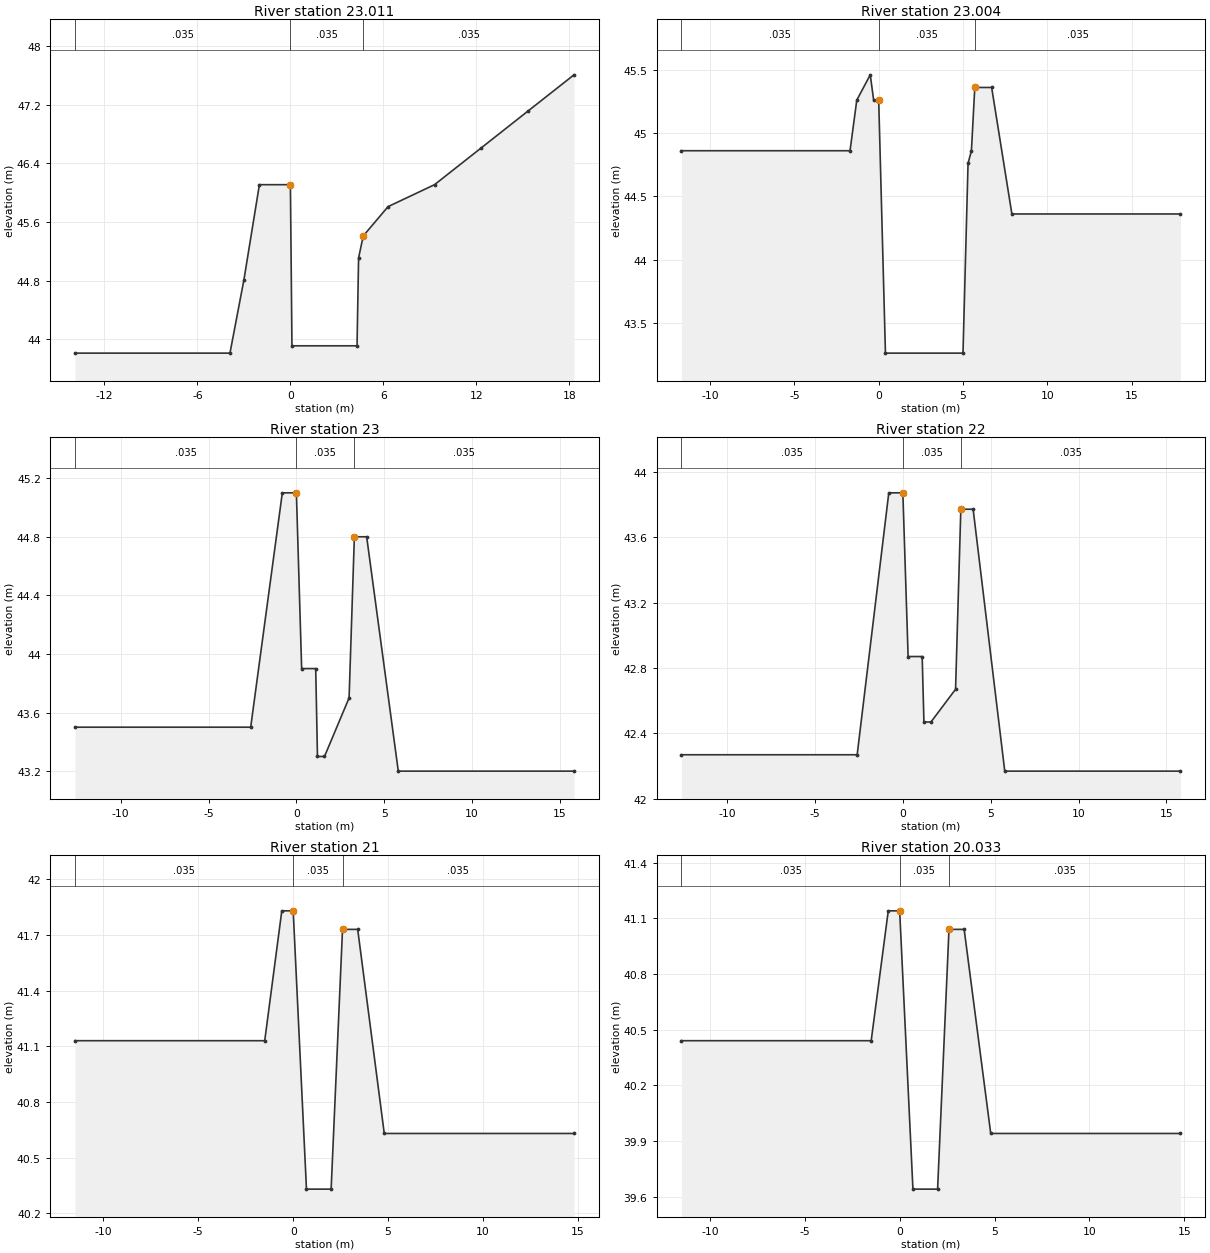
Type RM Length L Ch R = 1 ,23.011  ,7,7,7
#Sta/Elev= 14
   -13.9   43.81    -3.9   43.81      -3   44.81      -2   46.11       0   46.11
      .1   43.91     4.3   43.91     4.4   45.11     4.7   45.41     6.3   45.81
     9.3   46.11    12.3   46.61    15.3   47.11    18.3   47.61
#Mann= 3 , 0 , 0
   -13.9    .035       0       0    .035       0     4.7    .035       0
Bank Sta=0,4.7
XS Rating Curve= 0
Exp/Cntr=.3,.1

Type RM Length L Ch R = 1 ,23.004  ,4,4,4
#Sta/Elev= 14
   -11.7   44.86    -1.7   44.86    -1.3   45.26     -.5   45.46     -.3   45.26
       0   45.26      .4   43.26       5   43.26     5.3   44.76     5.5   44.86
     5.7   45.36     6.7   45.36     7.9   44.36    17.9   44.36
#Mann= 3 , 0 , 0
   -11.7    .035       0       0    .035       0     5.7    .035       0
Bank Sta=0,5.7
XS Rating Curve= 0
Exp/Cntr=.3,.1

Type RM Length L Ch R = 1 ,23      ,50,50,50
#Sta/Elev= 13
   -12.6    43.5    -2.6    43.5     -.8    45.1       0    45.1      .3    43.9
     1.1    43.9     1.2    43.3     1.6    43.3       3    43.7     3.3    44.8
       4    44.8     5.8    43.2    15.8    43.2
#Mann= 3 , 0 , 0
   -12.6    .035       0       0    .035       0     3.3    .035       0
Bank Sta=0,3.3
XS Rating Curve= 0
Exp/Cntr=.3,.1

Type RM Length L Ch R = 1 ,22      ,50,50,50
#Sta/Elev= 13
   -12.6   42.27    -2.6   42.27     -.8   43.87       0   43.87      .3   42.87
     1.1   42.87     1.2   42.47     1.6   42.47       3   42.67     3.3   43.77
       4   43.77     5.8   42.17    15.8   42.17
#Mann= 3 , 0 , 0
   -12.6    .035       0       0    .035       0     3.3    .035       0
Bank Sta=0,3.3
XS Rating Curve= 0
Exp/Cntr=.3,.1

Type RM Length L Ch R = 1 ,21      ,17,17,17
#Sta/Elev= 10
   -11.5   41.13    -1.5   41.13     -.6   41.83       0   41.83      .7   40.33
       2   40.33     2.6   41.73     3.4   41.73     4.8   40.63    14.8   40.63
#Mann= 3 , 0 , 0
   -11.5    .035       0       0    .035       0     2.6    .035       0
Bank Sta=0,2.6
XS Rating Curve= 0
Exp/Cntr=.3,.1

Type RM Length L Ch R = 1 ,20.033  ,33,33,33
#Sta/Elev= 10
   -11.5   40.44    -1.5   40.44     -.6   41.14       0   41.14      .7   39.64
       2   39.64     2.6   41.04     3.4   41.04     4.8   39.94    14.8   39.94
#Mann= 3 , 0 , 0
   -11.5    .035       0       0    .035       0     2.6    .035       0
Bank Sta=0,2.6
XS Rating Curve= 0
Exp/Cntr=.3,.1

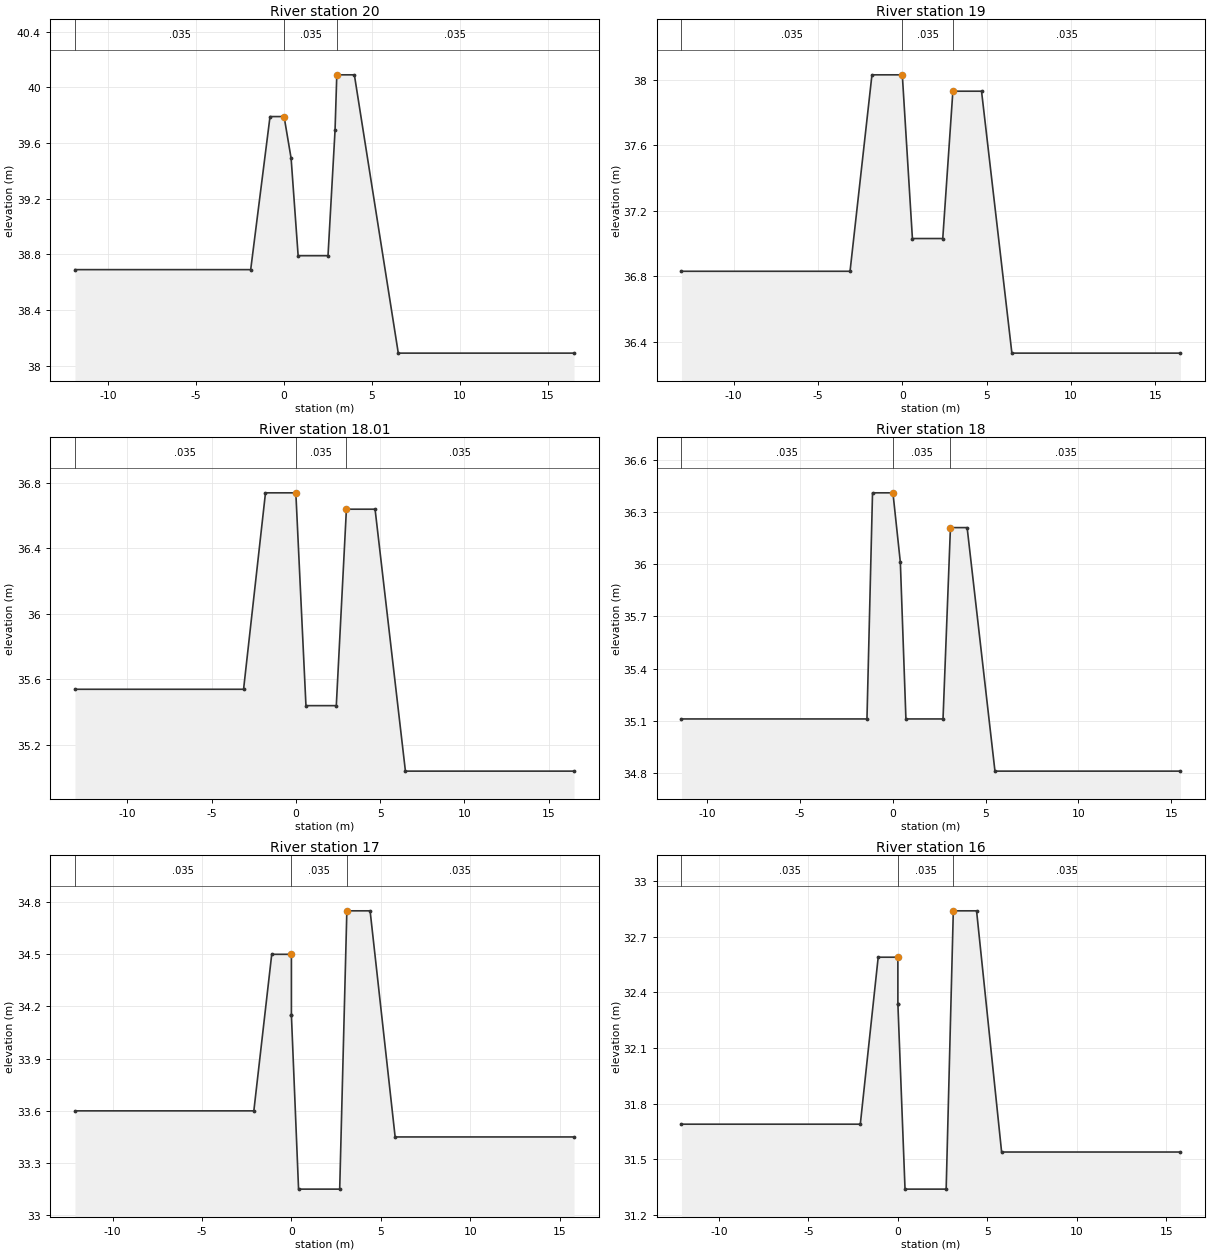
Type RM Length L Ch R = 1 ,20      ,50,50,50
#Sta/Elev= 12
   -11.9   38.69    -1.9   38.69     -.8   39.79       0   39.79      .4   39.49
      .8   38.79     2.5   38.79     2.9   39.69       3   40.09       4   40.09
     6.5   38.09    16.5   38.09
#Mann= 3 , 0 , 0
   -11.9    .035       0       0    .035       0       3    .035       0
Bank Sta=0,3
XS Rating Curve= 0
Exp/Cntr=.3,.1

Type RM Length L Ch R = 1 ,19      ,40,40,40
#Sta/Elev= 10
   -13.1   36.83    -3.1   36.83    -1.8   38.03       0   38.03      .6   37.03
     2.4   37.03       3   37.93     4.7   37.93     6.5   36.33    16.5   36.33
#Mann= 3 , 0 , 0
   -13.1    .035       0       0    .035       0       3    .035       0
Bank Sta=0,3
XS Rating Curve= 0
Exp/Cntr=.3,.1

Type RM Length L Ch R = 1 ,18.01   ,10,10,10
#Sta/Elev= 10
   -13.1   35.54    -3.1   35.54    -1.8   36.74       0   36.74      .6   35.44
     2.4   35.44       3   36.64     4.7   36.64     6.5   35.04    16.5   35.04
#Mann= 3 , 0 , 0
   -13.1    .035       0       0    .035       0       3    .035       0
Bank Sta=0,3
XS Rating Curve= 0
Exp/Cntr=.3,.1

Type RM Length L Ch R = 1 ,18      ,50,50,50
#Sta/Elev= 11
   -11.4   35.11    -1.4   35.11    -1.1   36.41       0   36.41      .4   36.01
      .7   35.11     2.7   35.11     3.1   36.21       4   36.21     5.5   34.81
    15.5   34.81
#Mann= 3 , 0 , 0
   -11.4    .035       0       0    .035       0     3.1    .035       0
Bank Sta=0,3.1
XS Rating Curve= 0
Exp/Cntr=.3,.1

Type RM Length L Ch R = 1 ,17      ,50,50,50
#Sta/Elev= 12
   -12.1    33.6    -2.1    33.6    -1.1    34.5       0    34.5       0   34.15
       0   34.15      .4   33.15     2.7   33.15     3.1   34.75     4.4   34.75
     5.8   33.45    15.8   33.45
#Mann= 3 , 0 , 0
   -12.1    .035       0       0    .035       0     3.1    .035       0
Bank Sta=0,3.1
XS Rating Curve= 0
Exp/Cntr=.3,.1

Type RM Length L Ch R = 1 ,16      ,35,35,35
#Sta/Elev= 12
   -12.1   31.69    -2.1   31.69    -1.1   32.59       0   32.59       0   32.34
       0   32.34      .4   31.34     2.7   31.34     3.1   32.84     4.4   32.84
     5.8   31.54    15.8   31.54
#Mann= 3 , 0 , 0
   -12.1    .035       0       0    .035       0     3.1    .035       0
Bank Sta=0,3.1
XS Rating Curve= 0
Exp/Cntr=.3,.1

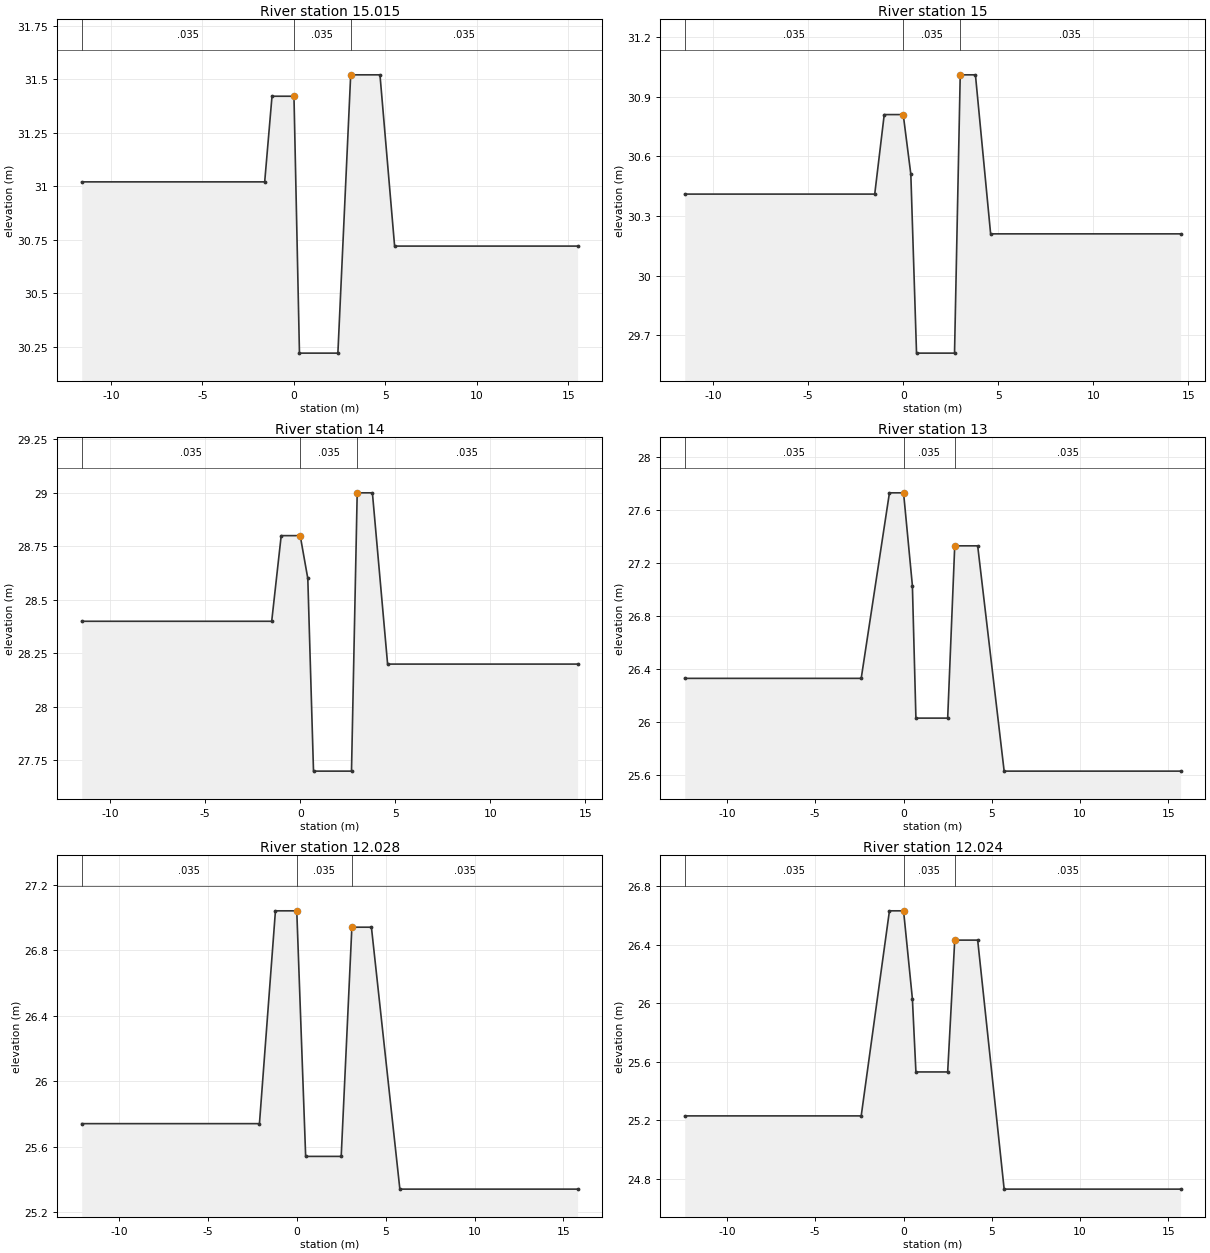
Type RM Length L Ch R = 1 ,15.015  ,15,15,15
#Sta/Elev= 10
   -11.6   31.02    -1.6   31.02    -1.2   31.42       0   31.42      .3   30.22
     2.4   30.22     3.1   31.52     4.7   31.52     5.5   30.72    15.5   30.72
#Mann= 3 , 0 , 0
   -11.6    .035       0       0    .035       0     3.1    .035       0
Bank Sta=0,3.1
XS Rating Curve= 0
Exp/Cntr=.3,.1

Type RM Length L Ch R = 1 ,15      ,50,50,50
#Sta/Elev= 11
   -11.5   30.41    -1.5   30.41      -1   30.81       0   30.81      .4   30.51
      .7   29.61     2.7   29.61       3   31.01     3.8   31.01     4.6   30.21
    14.6   30.21
#Mann= 3 , 0 , 0
   -11.5    .035       0       0    .035       0       3    .035       0
Bank Sta=0,3
XS Rating Curve= 0
Exp/Cntr=.3,.1

Type RM Length L Ch R = 1 ,14      ,50,50,50
#Sta/Elev= 11
   -11.5    28.4    -1.5    28.4      -1    28.8       0    28.8      .4    28.6
      .7    27.7     2.7    27.7       3      29     3.8      29     4.6    28.2
    14.6    28.2
#Mann= 3 , 0 , 0
   -11.5    .035       0       0    .035       0       3    .035       0
Bank Sta=0,3
XS Rating Curve= 0
Exp/Cntr=.3,.1

Type RM Length L Ch R = 1 ,13      ,22,22,22
#Sta/Elev= 11
   -12.4   26.33    -2.4   26.33     -.8   27.73       0   27.73      .5   27.03
      .7   26.03     2.5   26.03     2.9   27.33     4.2   27.33     5.7   25.63
    15.7   25.63
#Mann= 3 , 0 , 0
   -12.4    .035       0       0    .035       0     2.9    .035       0
Bank Sta=0,2.9
XS Rating Curve= 0
Exp/Cntr=.3,.1

Type RM Length L Ch R = 1 ,12.028  ,4,4,4
#Sta/Elev= 10
   -12.1   25.74    -2.1   25.74    -1.2   27.04       0   27.04      .5   25.54
     2.5   25.54     3.1   26.94     4.2   26.94     5.8   25.34    15.8   25.34
#Mann= 3 , 0 , 0
   -12.1    .035       0       0    .035       0     3.1    .035       0
Bank Sta=0,3.1
XS Rating Curve= 0
Exp/Cntr=.3,.1

Type RM Length L Ch R = 1 ,12.024  ,1,1,1
#Sta/Elev= 11
   -12.4   25.23    -2.4   25.23     -.8   26.63       0   26.63      .5   26.03
      .7   25.53     2.5   25.53     2.9   26.43     4.2   26.43     5.7   24.73
    15.7   24.73
#Mann= 3 , 0 , 0
   -12.4    .035       0       0    .035       0     2.9    .035       0
Bank Sta=0,2.9
XS Rating Curve= 0
Exp/Cntr=.3,.1

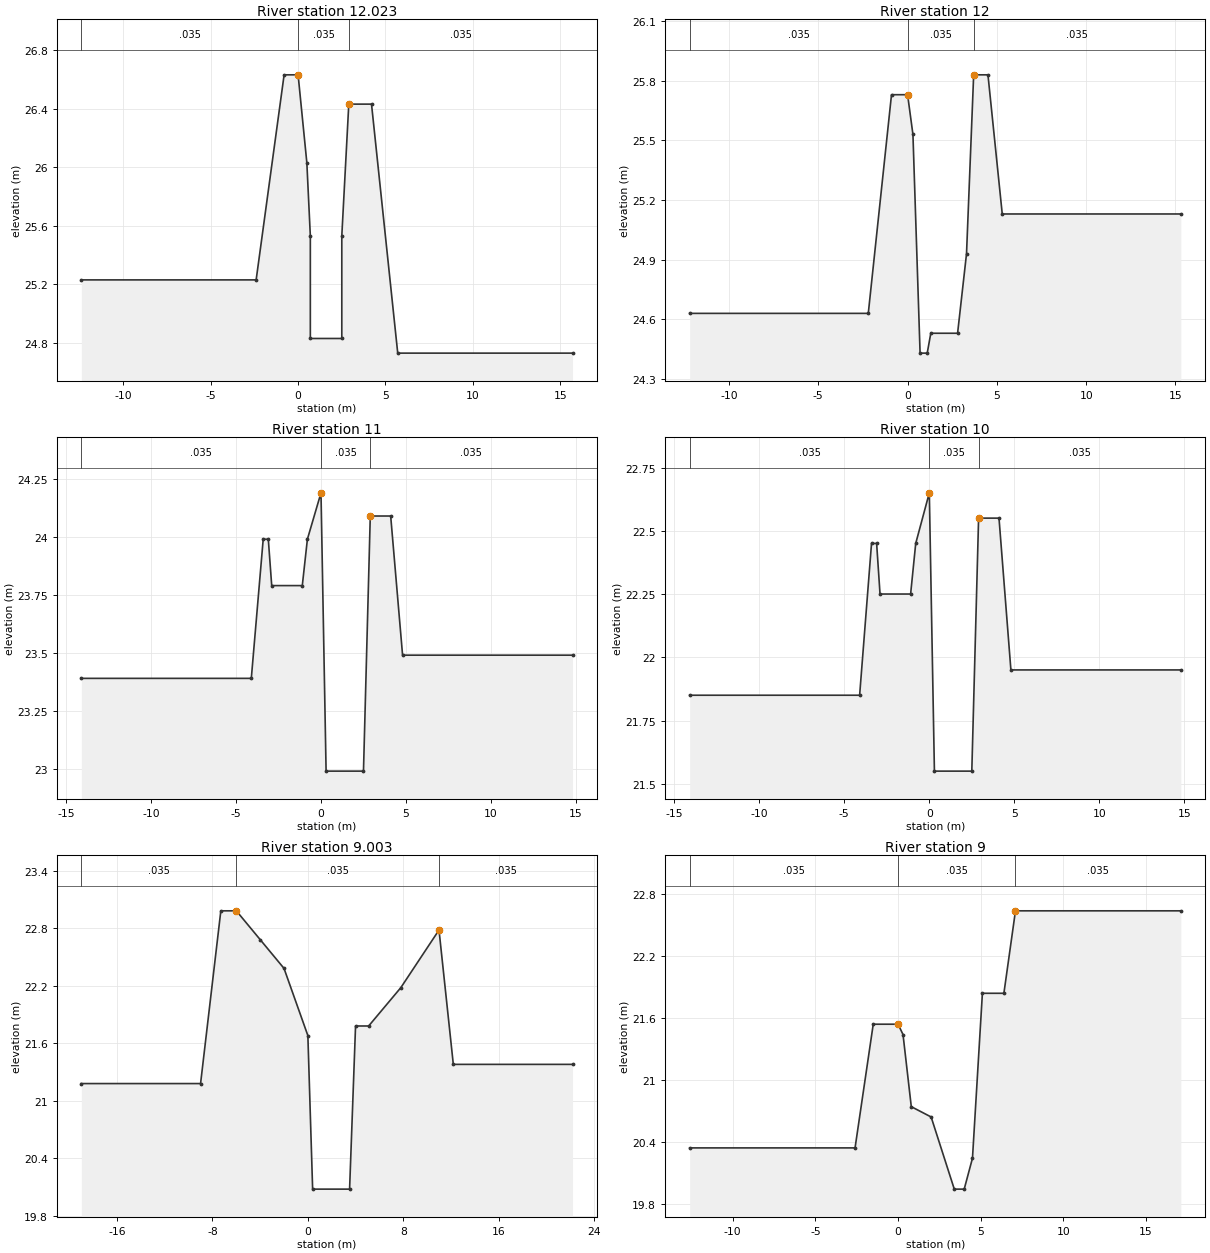
Type RM Length L Ch R = 1 ,12.023  ,23,23,23
#Sta/Elev= 13
   -12.4   25.23    -2.4   25.23     -.8   26.63       0   26.63      .5   26.03
      .7   25.53      .7   24.83     2.5   24.83     2.5   25.53     2.9   26.43
     4.2   26.43     5.7   24.73    15.7   24.73
#Mann= 3 , 0 , 0
   -12.4    .035       0       0    .035       0     2.9    .035       0
Bank Sta=0,2.9
XS Rating Curve= 0
Exp/Cntr=.3,.1

Type RM Length L Ch R = 1 ,12      ,50,50,50
#Sta/Elev= 14
   -12.2   24.63    -2.2   24.63     -.9   25.73       0   25.73      .3   25.53
      .7   24.43     1.1   24.43     1.3   24.53     2.8   24.53     3.3   24.93
     3.7   25.83     4.5   25.83     5.3   25.13    15.3   25.13
#Mann= 3 , 0 , 0
   -12.2    .035       0       0    .035       0     3.7    .035       0
Bank Sta=0,3.7
XS Rating Curve= 0
Exp/Cntr=.3,.1

Type RM Length L Ch R = 1 ,11      ,50,50,50
#Sta/Elev= 14
   -14.1   23.39    -4.1   23.39    -3.4   23.99    -3.1   23.99    -2.9   23.79
    -1.1   23.79     -.8   23.99       0   24.19      .3   22.99     2.5   22.99
     2.9   24.09     4.1   24.09     4.8   23.49    14.8   23.49
#Mann= 3 , 0 , 0
   -14.1    .035       0       0    .035       0     2.9    .035       0
Bank Sta=0,2.9
XS Rating Curve= 0
Exp/Cntr=.3,.1

Type RM Length L Ch R = 1 ,10      ,47,47,47
#Sta/Elev= 14
   -14.1   21.85    -4.1   21.85    -3.4   22.45    -3.1   22.45    -2.9   22.25
    -1.1   22.25     -.8   22.45       0   22.65      .3   21.55     2.5   21.55
     2.9   22.55     4.1   22.55     4.8   21.95    14.8   21.95
#Mann= 3 , 0 , 0
   -14.1    .035       0       0    .035       0     2.9    .035       0
Bank Sta=0,2.9
XS Rating Curve= 0
Exp/Cntr=.3,.1

Type RM Length L Ch R = 1 ,9.003   ,3,3,3
#Sta/Elev= 15
     -19   21.18      -9   21.18    -7.3   22.98      -6   22.98      -4   22.68
      -2   22.38       0   21.68      .4   20.08     3.5   20.08       4   21.78
     5.1   21.78     7.8   22.18      11   22.78    12.2   21.38    22.2   21.38
#Mann= 3 , 0 , 0
     -19    .035       0      -6    .035       0      11    .035       0
Bank Sta=-6,11
XS Rating Curve= 0
Exp/Cntr=.3,.1

Type RM Length L Ch R = 1 ,9       ,50,50,50
#Sta/Elev= 14
   -12.6   20.34    -2.6   20.34    -1.5   21.54       0   21.54      .3   21.44
      .8   20.74       2   20.64     3.4   19.94       4   19.94     4.5   20.24
     5.1   21.84     6.4   21.84     7.1   22.64    17.1   22.64
#Mann= 3 , 0 , 0
   -12.6    .035       0       0    .035       0     7.1    .035       0
Bank Sta=0,7.1
XS Rating Curve= 0
Exp/Cntr=.3,.1

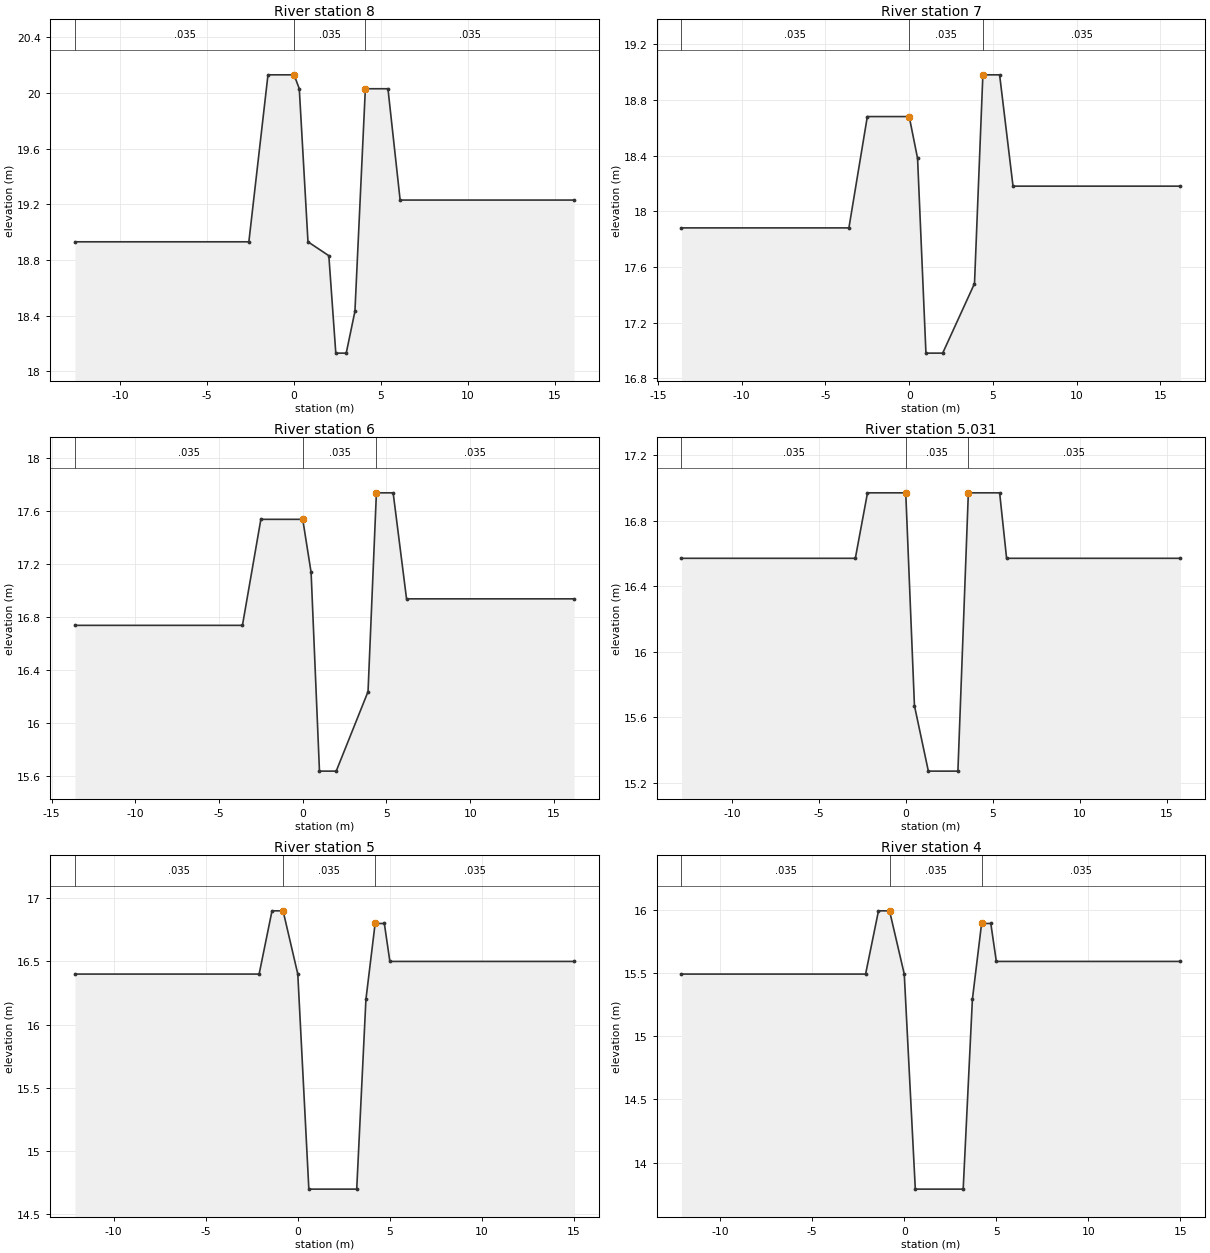
Type RM Length L Ch R = 1 ,8       ,50,50,50
#Sta/Elev= 14
   -12.6   18.93    -2.6   18.93    -1.5   20.13       0   20.13      .3   20.03
      .8   18.93       2   18.83     2.4   18.13       3   18.13     3.5   18.43
     4.1   20.03     5.4   20.03     6.1   19.23    16.1   19.23
#Mann= 3 , 0 , 0
   -12.6    .035       0       0    .035       0     4.1    .035       0
Bank Sta=0,4.1
XS Rating Curve= 0
Exp/Cntr=.3,.1

Type RM Length L Ch R = 1 ,7       ,50,50,50
#Sta/Elev= 12
   -13.6   17.88    -3.6   17.88    -2.5   18.68       0   18.68      .5   18.38
       1   16.98       2   16.98     3.9   17.48     4.4   18.98     5.4   18.98
     6.2   18.18    16.2   18.18
#Mann= 3 , 0 , 0
   -13.6    .035       0       0    .035       0     4.4    .035       0
Bank Sta=0,4.4
XS Rating Curve= 0
Exp/Cntr=.3,.1

Type RM Length L Ch R = 1 ,6       ,19,19,19
#Sta/Elev= 12
   -13.6   16.74    -3.6   16.74    -2.5   17.54       0   17.54      .5   17.14
       1   15.64       2   15.64     3.9   16.24     4.4   17.74     5.4   17.74
     6.2   16.94    16.2   16.94
#Mann= 3 , 0 , 0
   -13.6    .035       0       0    .035       0     4.4    .035       0
Bank Sta=0,4.4
XS Rating Curve= 0
Exp/Cntr=.3,.1

Type RM Length L Ch R = 1 ,5.031   ,31,31,31
#Sta/Elev= 11
   -12.9   16.57    -2.9   16.57    -2.2   16.97       0   16.97      .5   15.67
     1.3   15.27       3   15.27     3.6   16.97     5.4   16.97     5.8   16.57
    15.8   16.57
#Mann= 3 , 0 , 0
   -12.9    .035       0       0    .035       0     3.6    .035       0
Bank Sta=0,3.6
XS Rating Curve= 0
Exp/Cntr=.3,.1

Type RM Length L Ch R = 1 ,5       ,50,50,50
#Sta/Elev= 12
   -12.1    16.4    -2.1    16.4    -1.4    16.9     -.8    16.9       0    16.4
      .6    14.7     3.2    14.7     3.7    16.2     4.2    16.8     4.7    16.8
       5    16.5      15    16.5
#Mann= 3 , 0 , 0
   -12.1    .035       0     -.8    .035       0     4.2    .035       0
Bank Sta=-.8,4.2
XS Rating Curve= 0
Exp/Cntr=.3,.1

Type RM Length L Ch R = 1 ,4       ,50,50,50
#Sta/Elev= 12
   -12.1   15.49    -2.1   15.49    -1.4   15.99     -.8   15.99       0   15.49
      .6   13.79     3.2   13.79     3.7   15.29     4.2   15.89     4.7   15.89
       5   15.59      15   15.59
#Mann= 3 , 0 , 0
   -12.1    .035       0     -.8    .035       0     4.2    .035       0
Bank Sta=-.8,4.2
XS Rating Curve= 0
Exp/Cntr=.3,.1

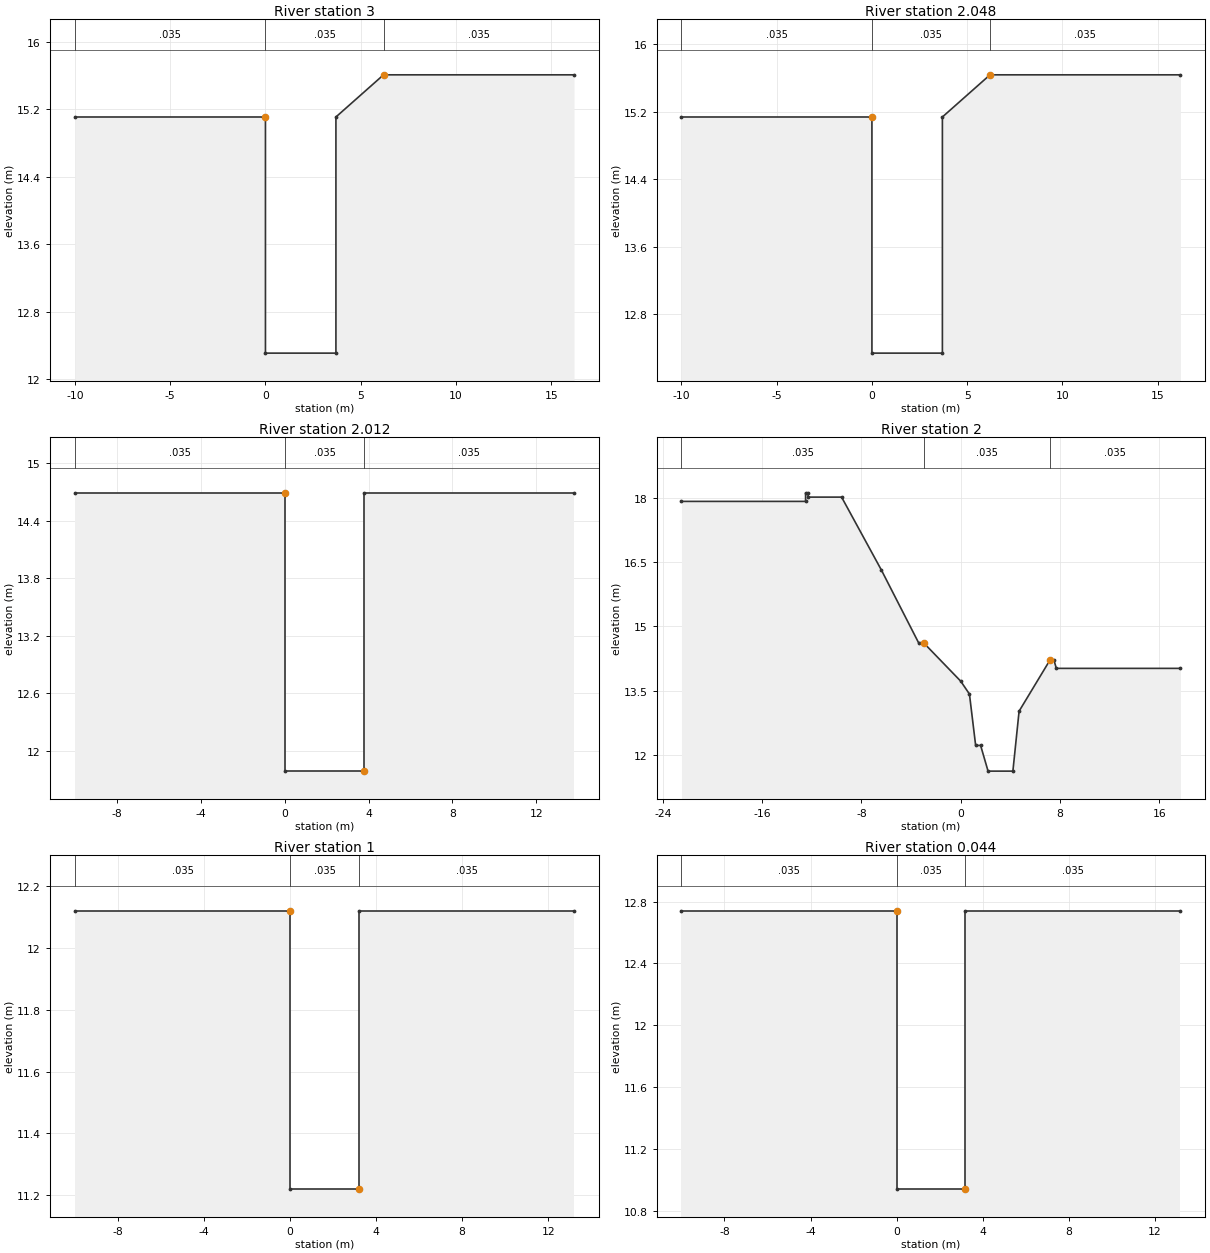
Type RM Length L Ch R = 1 ,3       ,2,2,2
#Sta/Elev= 7
     -10   15.11       0   15.11       0   12.31     3.7   12.31     3.7   15.11
     6.2   15.61    16.2   15.61
#Mann= 3 , 0 , 0
     -10    .035       0       0    .035       0     6.2    .035       0
Bank Sta=0,6.2
XS Rating Curve= 0
Exp/Cntr=.3,.1

Type RM Length L Ch R = 1 ,2.048   ,36,36,36
#Sta/Elev= 7
     -10   15.14       0   15.14       0   12.34     3.7   12.34     3.7   15.14
     6.2   15.64    16.2   15.64
#Mann= 3 , 0 , 0
     -10    .035       0       0    .035       0     6.2    .035       0
Bank Sta=0,6.2
XS Rating Curve= 0
Exp/Cntr=.3,.1

Type RM Length L Ch R = 1 ,2.012   ,12,12,12
#Sta/Elev= 6
     -10   14.69       0   14.69       0   11.79     3.8   11.79     3.8   14.69
    13.8   14.69
#Mann= 3 , 0 , 0
     -10    .035       0       0    .035       0     3.8    .035       0
Bank Sta=0,3.8
XS Rating Curve= 0
Exp/Cntr=.3,.1

Type RM Length L Ch R = 1 ,2       ,50,50,50
#Sta/Elev= 20
   -22.5   17.92   -12.5   17.92   -12.5   18.12   -12.3   18.12   -12.3   18.02
    -9.6   18.02    -6.4   16.32    -3.4   14.62      -3   14.62       0   13.72
      .7   13.42     1.2   12.22     1.6   12.22     2.2   11.62     4.2   11.62
     4.7   13.02     7.2   14.22     7.5   14.22     7.7   14.02    17.7   14.02
#Mann= 3 , 0 , 0
   -22.5    .035       0      -3    .035       0     7.2    .035       0
Bank Sta=-3,7.2
XS Rating Curve= 0
Exp/Cntr=.3,.1

Type RM Length L Ch R = 1 ,1       ,6,6,6
#Sta/Elev= 6
     -10   12.12       0   12.12       0   11.22     3.2   11.22     3.2   12.12
    13.2   12.12
#Mann= 3 , 0 , 0
     -10    .035       0       0    .035       0     3.2    .035       0
Bank Sta=0,3.2
XS Rating Curve= 0
Exp/Cntr=.3,.1

Type RM Length L Ch R = 1 ,0.044   ,44,44,44
#Sta/Elev= 6
     -10   12.74       0   12.74       0   10.94     3.2   10.94     3.2   12.74
    13.2   12.74
#Mann= 3 , 0 , 0
     -10    .035       0       0    .035       0     3.2    .035       0
Bank Sta=0,3.2
XS Rating Curve= 0
Exp/Cntr=.3,.1

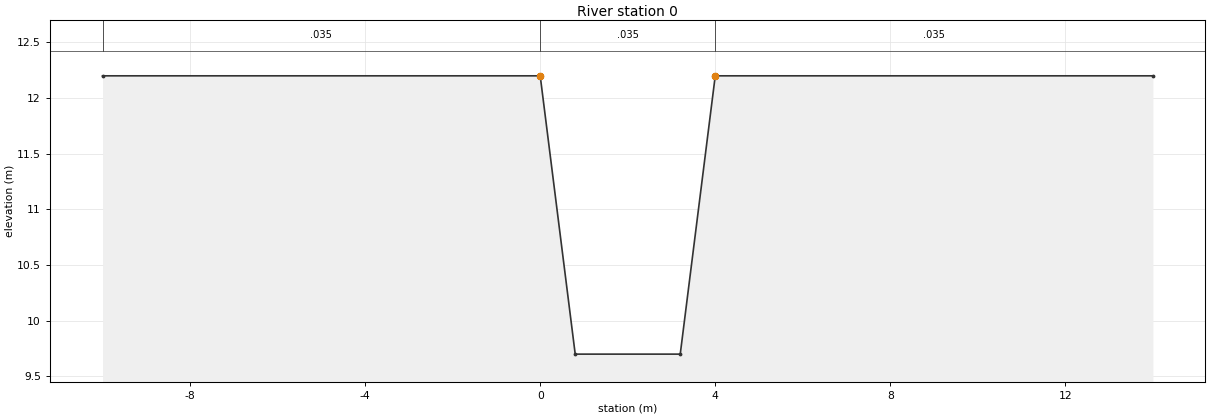
Type RM Length L Ch R = 1 ,0       ,0,0,0
#Sta/Elev= 6
     -10    12.2       0    12.2      .8     9.7     3.2     9.7       4    12.2
      14    12.2
#Mann= 3 , 0 , 0
     -10    .035       0       0    .035       0       4    .035       0
Bank Sta=0,4
XS Rating Curve= 0
Exp/Cntr=.3,.1

Chan Stop Cuts=-1