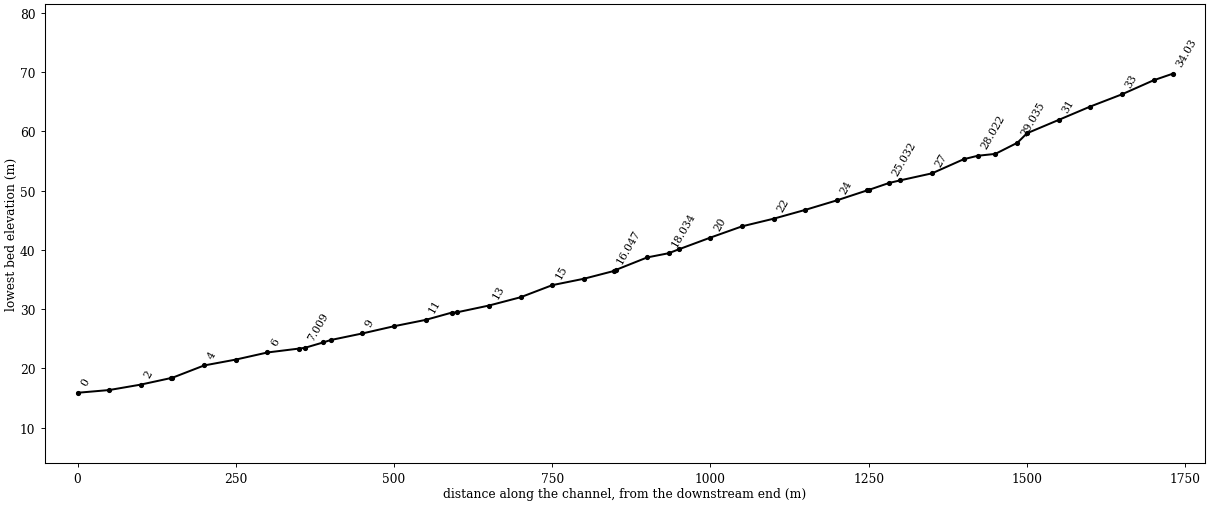
--- DAEDONG.prj (project) ---

Proj Title=DAEDONG
Current Plan=p01
Default Exp/Contr=.3,.1
SI Units
Geom File=g01
Flow File=f01
Plan File=p01
Y Axis Title=Elevation
X Axis Title(PF)=Main Channel Distance
X Axis Title(XS)=Station
BEGIN DESCRIPTION:
           BACK WATER COMPUTATION
      APPLICATION OF HEC-2 BY Samju Construction Engineering
      DAEDONG-STREEM : 30 YR
END DESCRIPTION:
DSS Export Rating Curves= 0
DSS Export Rating Curve Sorted= 0
DSS Export Volume Flow Curves= 0
DXF OffsetX= 0
DXF OffsetY= 0
DXF ScaleX= 1
DXF ScaleY= 10

--- DAEDONG.p01 (plan) ---

Plan Title=Imported Plan 01
Version=Version 3.0.1  Mar 2001
Short Identifier=Imported Pla
Geom File=g01
Flow File=f01
Subcritical Flow
K Sum by GR= 0
Std Step Tol= 0.003
Critical Tol= 0.003
Num of Std Step Trials= 20
Max Error Tol= 0.1
Flow Tol Ratio= 0.001
Split Flow NTrial= 30
Split Flow Tol= 0.02
Split Flow Ratio= 0.02
Log Output Level= 0
Friction Slope Method= 1
Unsteady Friction Slope Method= 2
Parabolic Critical Depth
Global Vel Dist= 0 , 0 , 0
Global Log Level= 0
CheckData=True
Encroach Param=-1 ,0,0, 0
Computation Interval=1HOUR
Output Interval=1HOUR
Run HTab= 0
Run UNet= 0
Run PostProcess= 0
UNET Theta= 1
UNET ZTol= 0.02
UNET ZSATol= 0.1
UNET MxIter= 20
UNET MaxInSteps= 20
UNET DtIC= 0
UNET DtMin= 0
UNET MaxCRTS= 20
UNET WFStab= 2
UNET SFStab= 1
UNET WFX= 1
UNET SFX= 1
UNET Convert EG Bridges=-1
UNET Use Existing IB Tables=-1
Instantaneous Interval=1HOUR
Write IC File= 0
Write Velocity= 0
Write Detailed= 0

--- DAEDONG.f01 (steady flow) ---

Flow Title=Imported Flow 01
Version=Version 3.0.1  Mar 2001
Number of Profiles= 1
Profile Names=PF 1
River Rch & RM=RIVER-1,Reach-1         ,34.03
      75
River Rch & RM=DAEDONG,DAEDONG         ,34.03
      75
Boundary for River Rch & Prof#=DAEDONG,DAEDONG         , 1
Up Type= 0
Dn Type= 3
Dn Slope=.0109
DSS Import GetInterval= 0
DSS Import GetPeak= 0
DSS Import FillOption= 0

--- DAEDONG.g01 (geometry) ---

Geom Title=Imported Geom 01
Version=Version 3.0.1  Mar 2001

River Reach=DAEDONG         ,DAEDONG
Reach XY= 2
              .5             .95              .5             .05

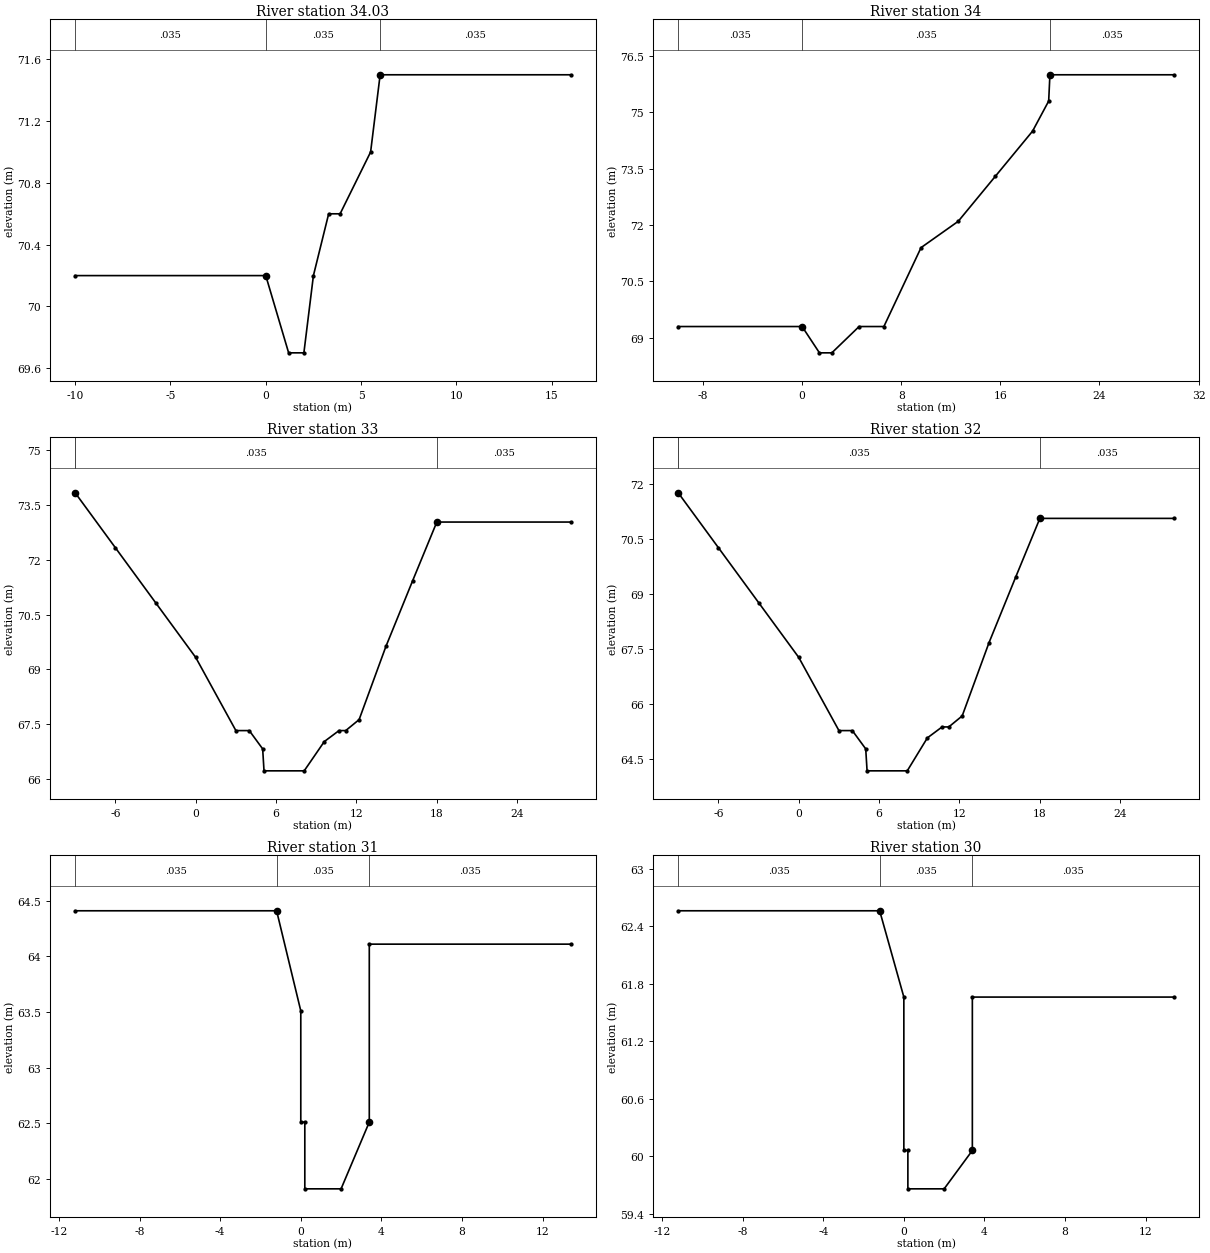
Type RM Length L Ch R = 1 ,34.03   ,30,30,30
#Sta/Elev= 10
     -10    70.2       0    70.2     1.2    69.7       2    69.7     2.5    70.2
     3.3    70.6     3.9    70.6     5.5      71       6    71.5      16    71.5
#Mann= 3 , 0 , 0
     -10    .035       0       0    .035       0       6    .035       0
Bank Sta=0,6
XS Rating Curve= 0
Exp/Cntr=.3,.1

Type RM Length L Ch R = 1 ,34      ,50,50,50
#Sta/Elev= 13
     -10    69.3       0    69.3     1.4    68.6     2.4    68.6     4.6    69.3
     6.6    69.3     9.6    71.4    12.6    72.1    15.6    73.3    18.6    74.5
    19.9    75.3      20      76      30      76
#Mann= 3 , 0 , 0
     -10    .035       0       0    .035       0      20    .035       0
Bank Sta=0,20
XS Rating Curve= 0
Exp/Cntr=.3,.1

Type RM Length L Ch R = 1 ,33      ,50,50,50
#Sta/Elev= 17
      -9   73.83      -6   72.33      -3   70.83       0   69.33       3   67.33
       4   67.33       5   66.83     5.1   66.23     8.1   66.23     9.6   67.03
    10.7   67.33    11.2   67.33    12.2   67.63    14.2   69.63    16.2   71.43
      18   73.03      28   73.03
#Mann= 3 , 0 , 0
      -9    .035       0      -9    .035       0      18    .035       0
Bank Sta=-9,18
XS Rating Curve= 0
Exp/Cntr=.3,.1

Type RM Length L Ch R = 1 ,32      ,50,50,50
#Sta/Elev= 17
      -9   71.77      -6   70.27      -3   68.77       0   67.27       3   65.27
       4   65.27       5   64.77     5.1   64.17     8.1   64.17     9.6   65.07
    10.7   65.37    11.2   65.37    12.2   65.67    14.2   67.67    16.2   69.47
      18   71.07      28   71.07
#Mann= 3 , 0 , 0
      -9    .035       0      -9    .035       0      18    .035       0
Bank Sta=-9,18
XS Rating Curve= 0
Exp/Cntr=.3,.1

Type RM Length L Ch R = 1 ,31      ,50,50,50
#Sta/Elev= 10
   -11.2   64.41    -1.2   64.41       0   63.51       0   62.51      .2   62.51
      .2   61.91       2   61.91     3.4   62.51     3.4   64.11    13.4   64.11
#Mann= 3 , 0 , 0
   -11.2    .035       0    -1.2    .035       0     3.4    .035       0
Bank Sta=-1.2,3.4
XS Rating Curve= 0
Exp/Cntr=.3,.1

Type RM Length L Ch R = 1 ,30      ,15,15,15
#Sta/Elev= 10
   -11.2   62.56    -1.2   62.56       0   61.66       0   60.06      .2   60.06
      .2   59.66       2   59.66     3.4   60.06     3.4   61.66    13.4   61.66
#Mann= 3 , 0 , 0
   -11.2    .035       0    -1.2    .035       0     3.4    .035       0
Bank Sta=-1.2,3.4
XS Rating Curve= 0
Exp/Cntr=.3,.1

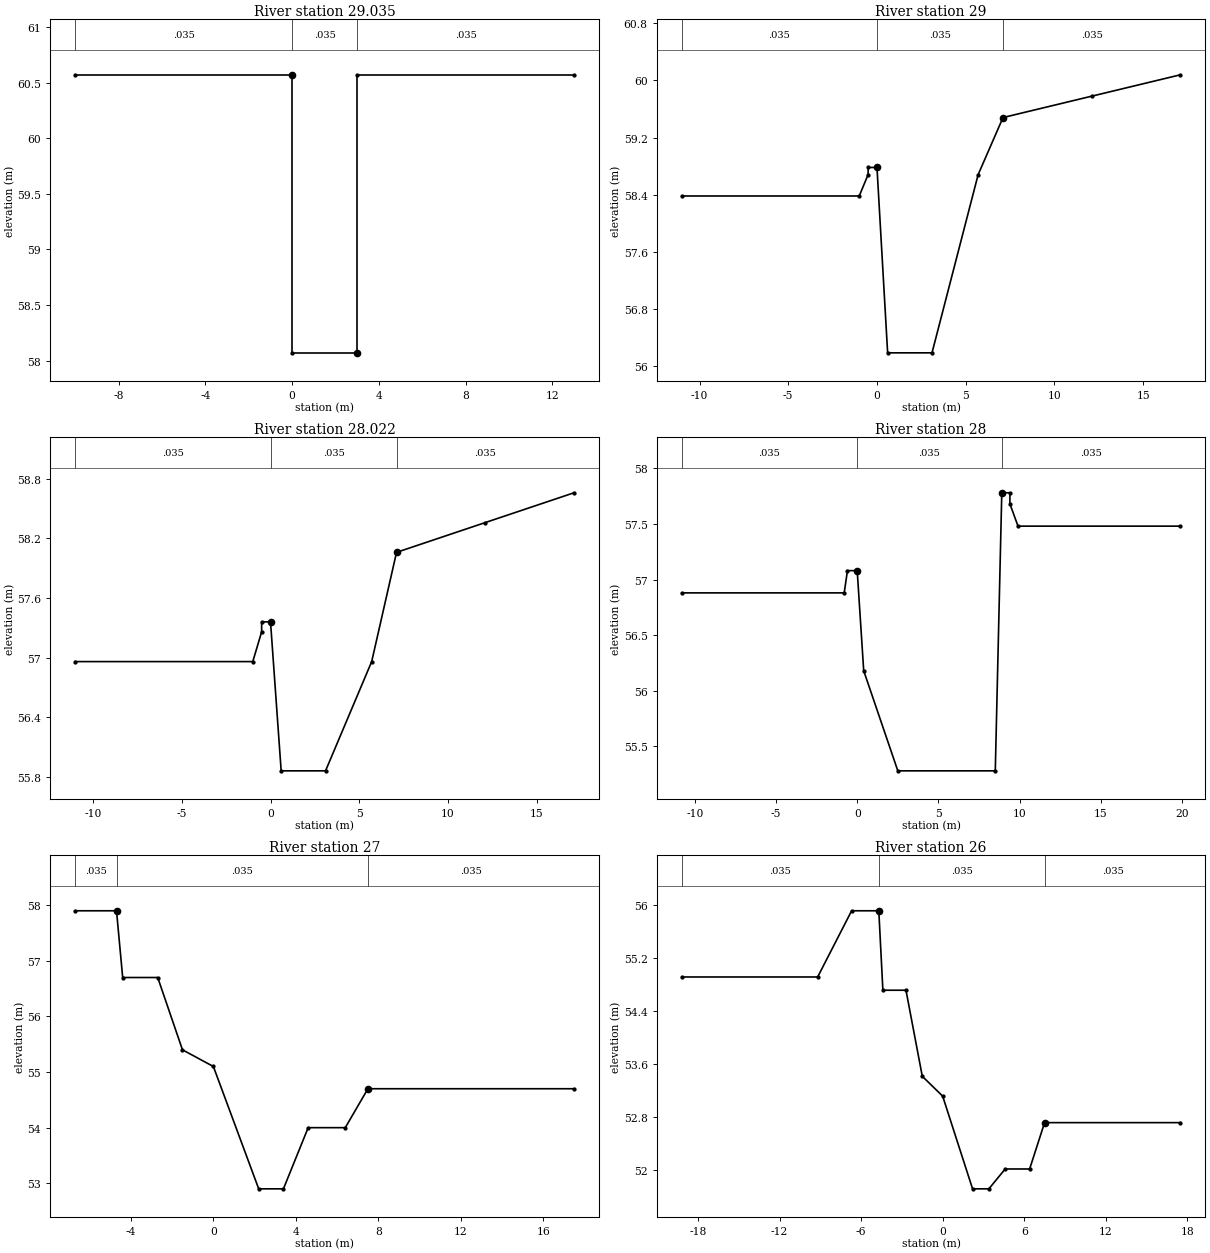
Type RM Length L Ch R = 1 ,29.035  ,35,35,35
#Sta/Elev= 6
     -10   60.57       0   60.57       0   58.07       3   58.07       3   60.57
      13   60.57
#Mann= 3 , 0 , 0
     -10    .035       0       0    .035       0       3    .035       0
Bank Sta=0,3
XS Rating Curve= 0
Exp/Cntr=.3,.1

Type RM Length L Ch R = 1 ,29      ,28,28,28
#Sta/Elev= 11
     -11   58.38      -1   58.38     -.5   58.68     -.5   58.78       0   58.78
      .6   56.18     3.1   56.18     5.7   58.68     7.1   59.48    12.1   59.78
    17.1   60.08
#Mann= 3 , 0 , 0
     -11    .035       0       0    .035       0     7.1    .035       0
Bank Sta=0,7.1
XS Rating Curve= 0
Exp/Cntr=.3,.1

Type RM Length L Ch R = 1 ,28.022  ,22,22,22
#Sta/Elev= 11
     -11   56.96      -1   56.96     -.5   57.26     -.5   57.36       0   57.36
      .6   55.86     3.1   55.86     5.7   56.96     7.1   58.06    12.1   58.36
    17.1   58.66
#Mann= 3 , 0 , 0
     -11    .035       0       0    .035       0     7.1    .035       0
Bank Sta=0,7.1
XS Rating Curve= 0
Exp/Cntr=.3,.1

Type RM Length L Ch R = 1 ,28      ,50,50,50
#Sta/Elev= 12
   -10.8   56.88     -.8   56.88     -.6   57.08       0   57.08      .4   56.18
     2.5   55.28     8.5   55.28     8.9   57.78     9.4   57.78     9.4   57.68
     9.9   57.48    19.9   57.48
#Mann= 3 , 0 , 0
   -10.8    .035       0       0    .035       0     8.9    .035       0
Bank Sta=0,8.9
XS Rating Curve= 0
Exp/Cntr=.3,.1

Type RM Length L Ch R = 1 ,27      ,50,50,50
#Sta/Elev= 12
    -6.7    57.9    -4.7    57.9    -4.4    56.7    -2.7    56.7    -1.5    55.4
       0    55.1     2.2    52.9     3.4    52.9     4.6      54     6.4      54
     7.5    54.7    17.5    54.7
#Mann= 3 , 0 , 0
    -6.7    .035       0    -4.7    .035       0     7.5    .035       0
Bank Sta=-4.7,7.5
XS Rating Curve= 0
Exp/Cntr=.3,.1

Type RM Length L Ch R = 1 ,26      ,18,18,18
#Sta/Elev= 14
   -19.2   54.92    -9.2   54.92    -6.7   55.92    -4.7   55.92    -4.4   54.72
    -2.7   54.72    -1.5   53.42       0   53.12     2.2   51.72     3.4   51.72
     4.6   52.02     6.4   52.02     7.5   52.72    17.5   52.72
#Mann= 3 , 0 , 0
   -19.2    .035       0    -4.7    .035       0     7.5    .035       0
Bank Sta=-4.7,7.5
XS Rating Curve= 0
Exp/Cntr=.3,.1

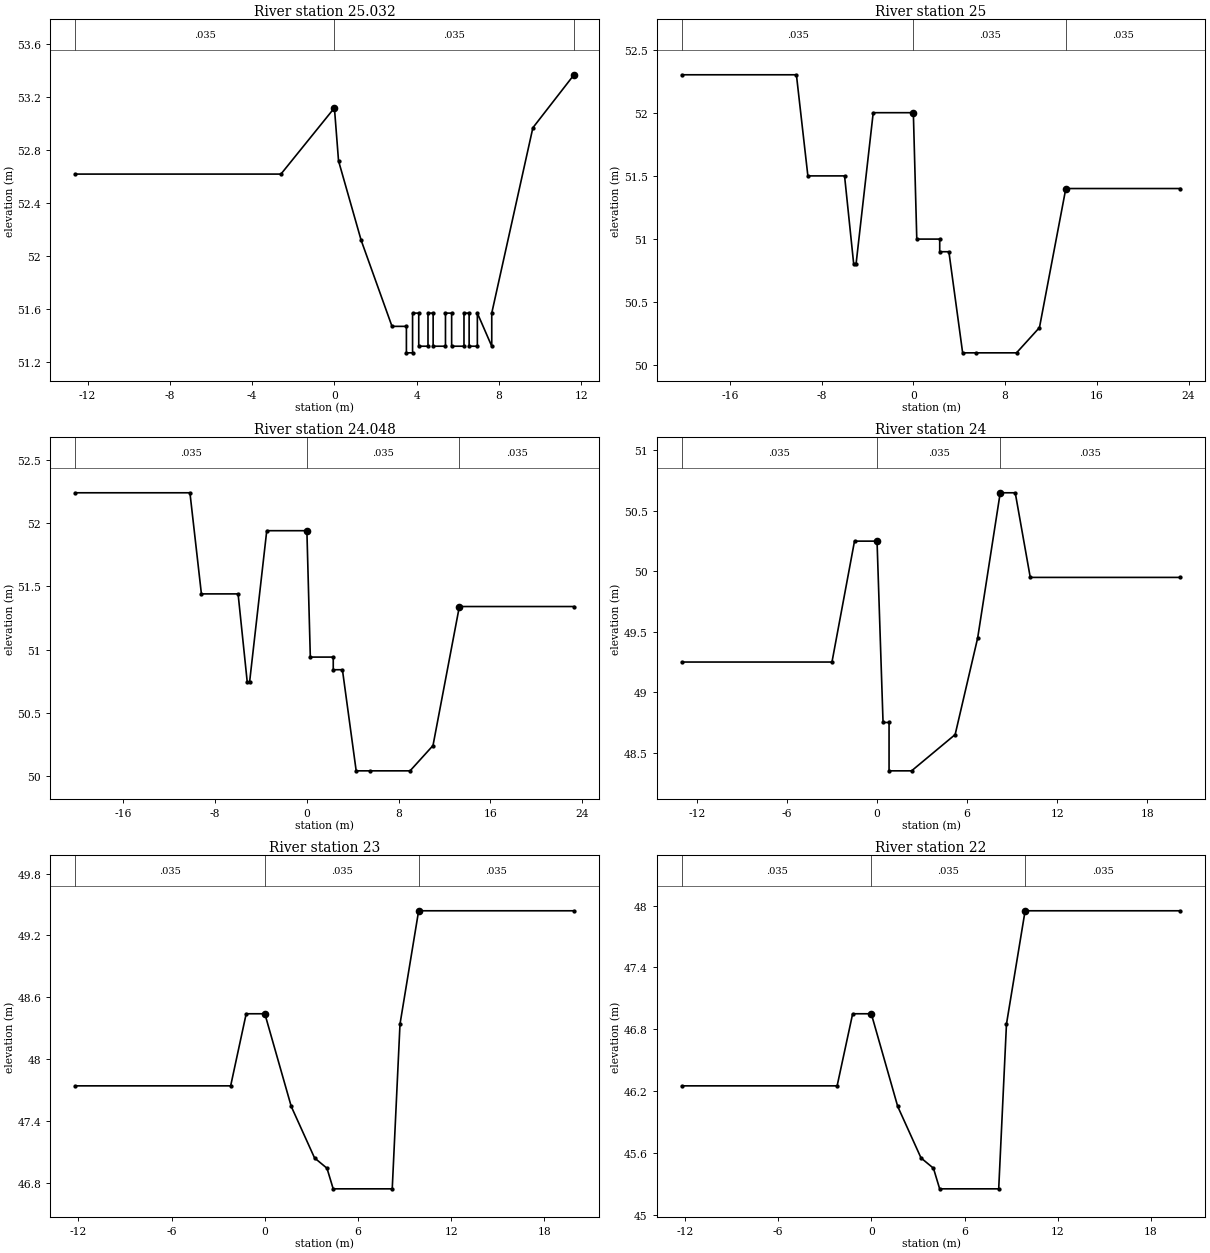
Type RM Length L Ch R = 1 ,25.032  ,32,32,32
#Sta/Elev= 30
   -12.6   52.62    -2.6   52.62       0   53.12      .2   52.72     1.3   52.12
     2.8   51.47     3.5   51.47     3.5   51.27     3.8   51.27     3.8   51.57
     4.1   51.57     4.1   51.32    4.55   51.32    4.55   51.57     4.8   51.57
     4.8   51.32     5.4   51.32     5.4   51.57     5.7   51.57     5.7   51.32
     6.3   51.32     6.3   51.57    6.55   51.57    6.55   51.32    6.95   51.32
    6.95   51.57    7.65   51.32    7.65   51.57    9.65   52.97   11.65   53.37
#Mann= 3 , 0 , 0
   -12.6    .035       0       0    .035       0   11.65    .035       0
Bank Sta=0,11.65
XS Rating Curve= 0
Exp/Cntr=.3,.1

Type RM Length L Ch R = 1 ,25      ,2,2,2
#Sta/Elev= 18
   -20.2    52.3   -10.2    52.3    -9.2    51.5      -6    51.5    -5.2    50.8
      -5    50.8    -3.5      52       0      52      .3      51     2.3      51
     2.3    50.9     3.1    50.9     4.3    50.1     5.5    50.1       9    50.1
      11    50.3    13.3    51.4    23.3    51.4
#Mann= 3 , 0 , 0
   -20.2    .035       0       0    .035       0    13.3    .035       0
Bank Sta=0,13.3
XS Rating Curve= 0
Exp/Cntr=.3,.1

Type RM Length L Ch R = 1 ,24.048  ,48,48,48
#Sta/Elev= 18
   -20.2   52.24   -10.2   52.24    -9.2   51.44      -6   51.44    -5.2   50.74
      -5   50.74    -3.5   51.94       0   51.94      .3   50.94     2.3   50.94
     2.3   50.84     3.1   50.84     4.3   50.04     5.5   50.04       9   50.04
      11   50.24    13.3   51.34    23.3   51.34
#Mann= 3 , 0 , 0
   -20.2    .035       0       0    .035       0    13.3    .035       0
Bank Sta=0,13.3
XS Rating Curve= 0
Exp/Cntr=.3,.1

Type RM Length L Ch R = 1 ,24      ,50,50,50
#Sta/Elev= 14
     -13   49.25      -3   49.25    -1.5   50.25       0   50.25      .4   48.75
      .8   48.75      .8   48.35     2.3   48.35     5.2   48.65     6.7   49.45
     8.2   50.65     9.2   50.65    10.2   49.95    20.2   49.95
#Mann= 3 , 0 , 0
     -13    .035       0       0    .035       0     8.2    .035       0
Bank Sta=0,8.2
XS Rating Curve= 0
Exp/Cntr=.3,.1

Type RM Length L Ch R = 1 ,23      ,50,50,50
#Sta/Elev= 12
   -12.2   47.74    -2.2   47.74    -1.2   48.44       0   48.44     1.7   47.54
     3.2   47.04       4   46.94     4.4   46.74     8.2   46.74     8.7   48.34
     9.9   49.44    19.9   49.44
#Mann= 3 , 0 , 0
   -12.2    .035       0       0    .035       0     9.9    .035       0
Bank Sta=0,9.9
XS Rating Curve= 0
Exp/Cntr=.3,.1

Type RM Length L Ch R = 1 ,22      ,50,50,50
#Sta/Elev= 12
   -12.2   46.25    -2.2   46.25    -1.2   46.95       0   46.95     1.7   46.05
     3.2   45.55       4   45.45     4.4   45.25     8.2   45.25     8.7   46.85
     9.9   47.95    19.9   47.95
#Mann= 3 , 0 , 0
   -12.2    .035       0       0    .035       0     9.9    .035       0
Bank Sta=0,9.9
XS Rating Curve= 0
Exp/Cntr=.3,.1

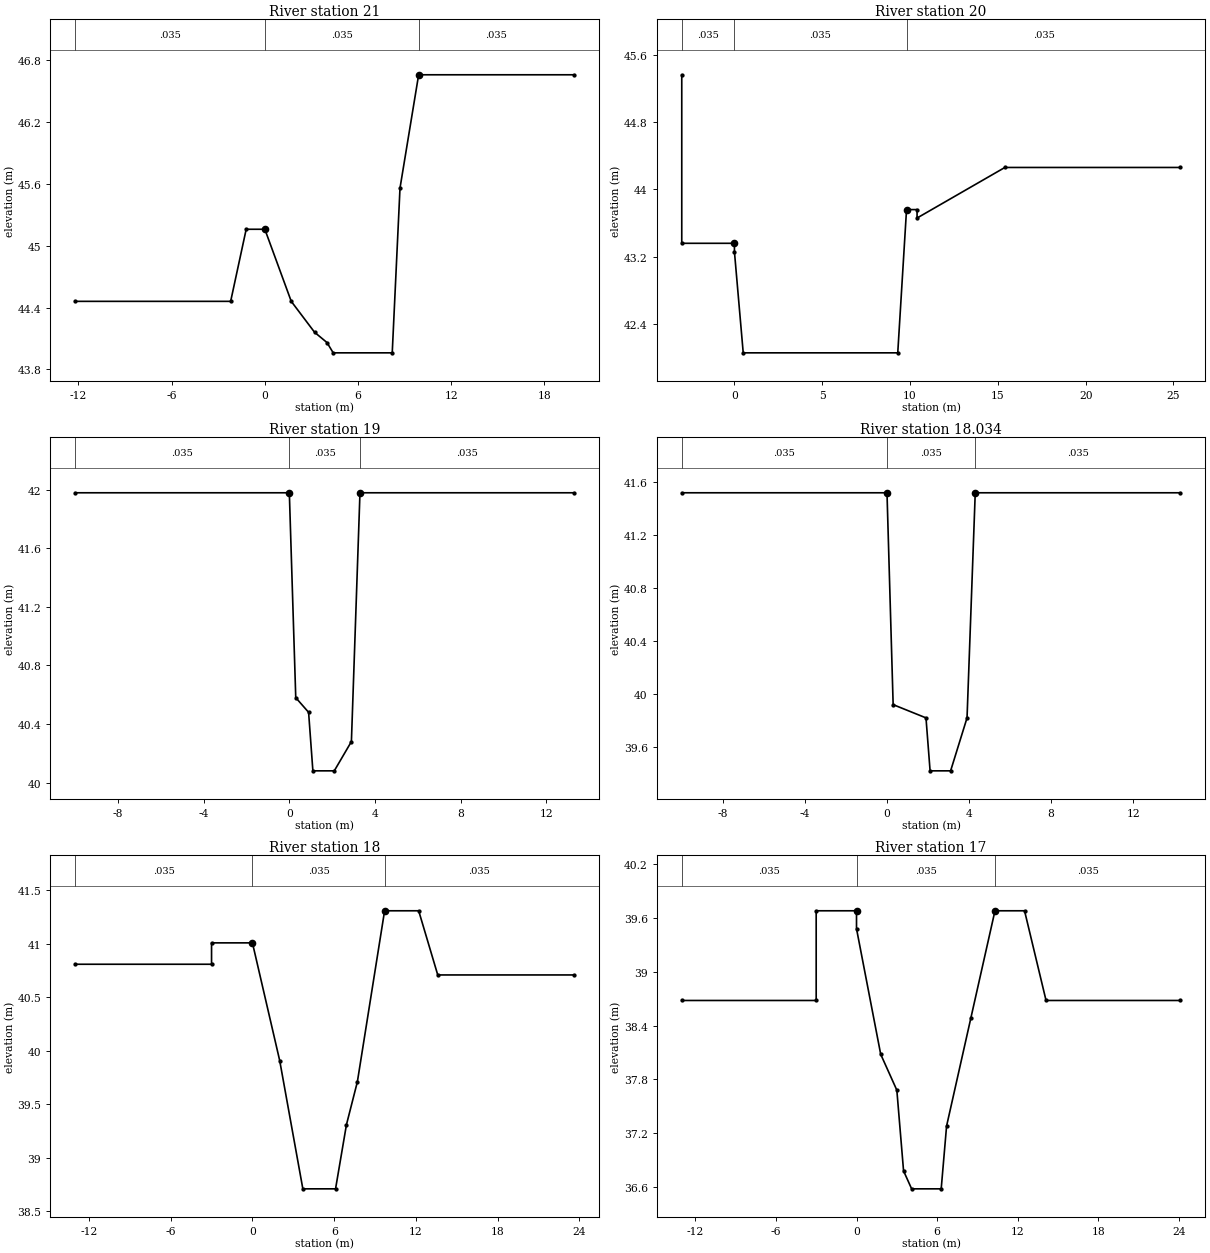
Type RM Length L Ch R = 1 ,21      ,50,50,50
#Sta/Elev= 12
   -12.2   44.46    -2.2   44.46    -1.2   45.16       0   45.16     1.7   44.46
     3.2   44.16       4   44.06     4.4   43.96     8.2   43.96     8.7   45.56
     9.9   46.66    19.9   46.66
#Mann= 3 , 0 , 0
   -12.2    .035       0       0    .035       0     9.9    .035       0
Bank Sta=0,9.9
XS Rating Curve= 0
Exp/Cntr=.3,.1

Type RM Length L Ch R = 1 ,20      ,50,50,50
#Sta/Elev= 11
      -3   45.36      -3   43.36       0   43.36       0   43.26      .5   42.06
     9.3   42.06     9.8   43.76    10.4   43.76    10.4   43.66    15.4   44.26
    25.4   44.26
#Mann= 3 , 0 , 0
      -3    .035       0       0    .035       0     9.8    .035       0
Bank Sta=0,9.8
XS Rating Curve= 0
Exp/Cntr=.3,.1

Type RM Length L Ch R = 1 ,19      ,16,16,16
#Sta/Elev= 9
     -10   41.98       0   41.98      .3   40.58      .9   40.48     1.1   40.08
     2.1   40.08     2.9   40.28     3.3   41.98    13.3   41.98
#Mann= 3 , 0 , 0
     -10    .035       0       0    .035       0     3.3    .035       0
Bank Sta=0,3.3
XS Rating Curve= 0
Exp/Cntr=.3,.1

Type RM Length L Ch R = 1 ,18.034  ,34,34,34
#Sta/Elev= 9
     -10   41.52       0   41.52      .3   39.92     1.9   39.82     2.1   39.42
     3.1   39.42     3.9   39.82     4.3   41.52    14.3   41.52
#Mann= 3 , 0 , 0
     -10    .035       0       0    .035       0     4.3    .035       0
Bank Sta=0,4.3
XS Rating Curve= 0
Exp/Cntr=.3,.1

Type RM Length L Ch R = 1 ,18      ,50,50,50
#Sta/Elev= 13
     -13   40.81      -3   40.81      -3   41.01       0   41.01       2   39.91
     3.7   38.71     6.1   38.71     6.9   39.31     7.7   39.71     9.7   41.31
    12.2   41.31    13.6   40.71    23.6   40.71
#Mann= 3 , 0 , 0
     -13    .035       0       0    .035       0     9.7    .035       0
Bank Sta=0,9.7
XS Rating Curve= 0
Exp/Cntr=.3,.1

Type RM Length L Ch R = 1 ,17      ,3,3,3
#Sta/Elev= 16
     -13   38.68      -3   38.68      -3   39.68       0   39.68       0   39.48
     1.8   38.08       3   37.68     3.5   36.78     4.1   36.58     6.3   36.58
     6.7   37.28     8.5   38.48    10.3   39.68    12.5   39.68    14.1   38.68
    24.1   38.68
#Mann= 3 , 0 , 0
     -13    .035       0       0    .035       0    10.3    .035       0
Bank Sta=0,10.3
XS Rating Curve= 0
Exp/Cntr=.3,.1

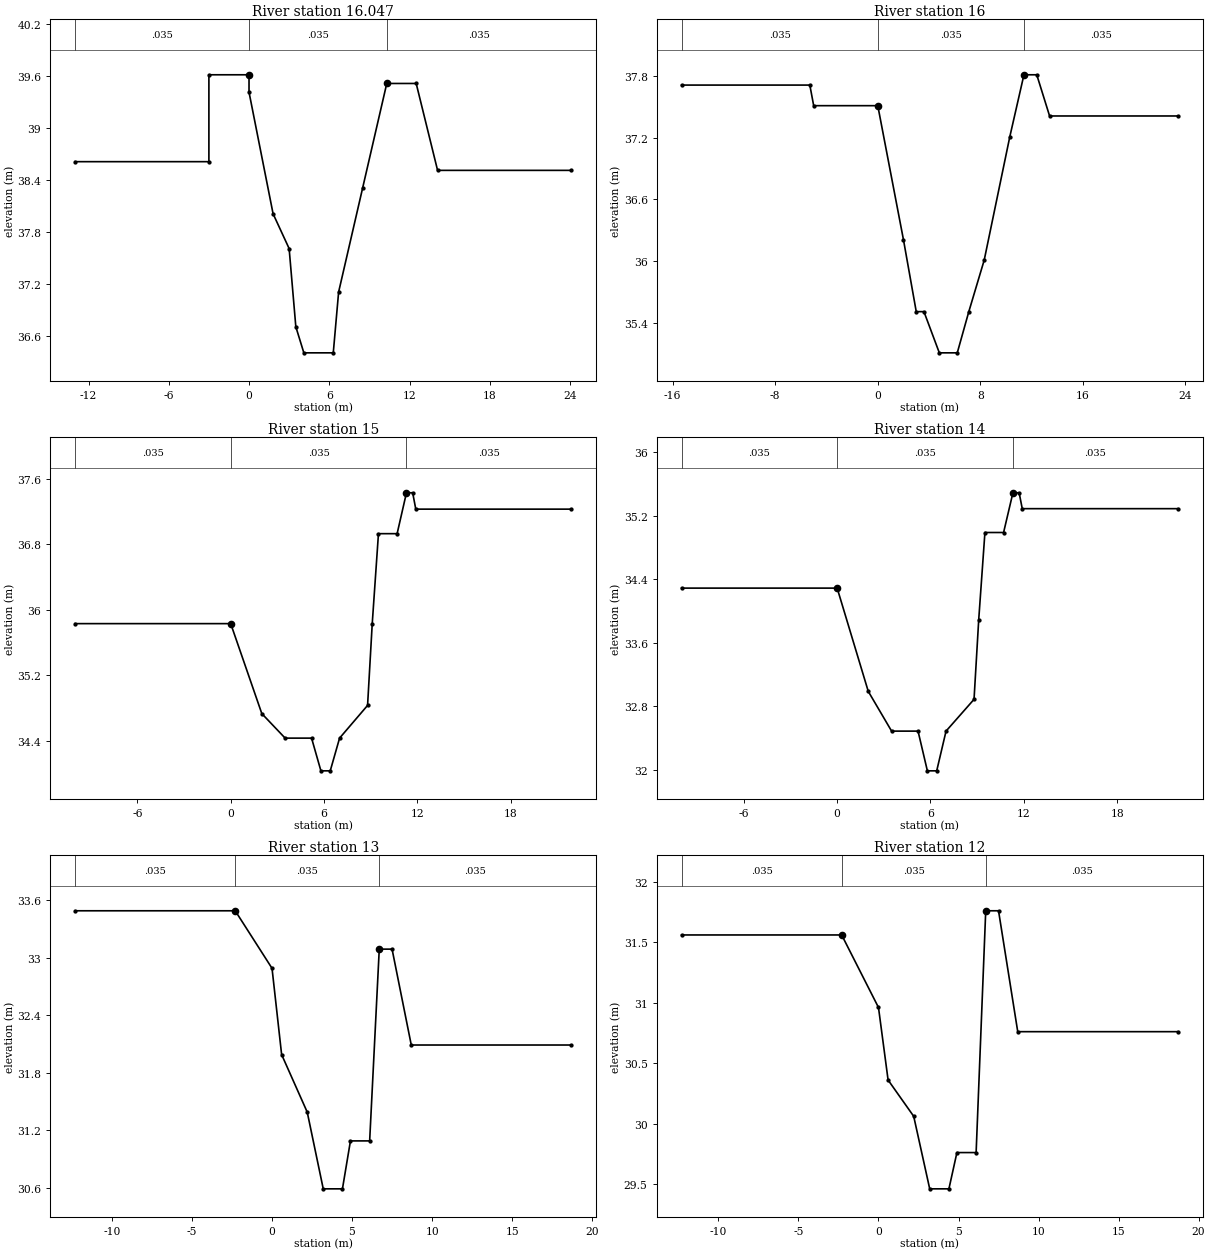
Type RM Length L Ch R = 1 ,16.047  ,47,47,47
#Sta/Elev= 16
     -13   38.61      -3   38.61      -3   39.61       0   39.61       0   39.41
     1.8   38.01       3   37.61     3.5   36.71     4.1   36.41     6.3   36.41
     6.7   37.11     8.5   38.31    10.3   39.51    12.5   39.51    14.1   38.51
    24.1   38.51
#Mann= 3 , 0 , 0
     -13    .035       0       0    .035       0    10.3    .035       0
Bank Sta=0,10.3
XS Rating Curve= 0
Exp/Cntr=.3,.1

Type RM Length L Ch R = 1 ,16      ,50,50,50
#Sta/Elev= 16
   -15.3   37.71    -5.3   37.71      -5   37.51       0   37.51       2   36.21
       3   35.51     3.6   35.51     4.8   35.11     6.2   35.11     7.1   35.51
     8.3   36.01    10.3   37.21    11.4   37.81    12.4   37.81    13.4   37.41
    23.4   37.41
#Mann= 3 , 0 , 0
   -15.3    .035       0       0    .035       0    11.4    .035       0
Bank Sta=0,11.4
XS Rating Curve= 0
Exp/Cntr=.3,.1

Type RM Length L Ch R = 1 ,15      ,50,50,50
#Sta/Elev= 16
     -10   35.83       0   35.83       2   34.73     3.5   34.43     5.2   34.43
     5.8   34.03     6.4   34.03       7   34.43     8.8   34.83     9.1   35.83
     9.5   36.93    10.7   36.93    11.3   37.43    11.7   37.43    11.9   37.23
    21.9   37.23
#Mann= 3 , 0 , 0
     -10    .035       0       0    .035       0    11.3    .035       0
Bank Sta=0,11.3
XS Rating Curve= 0
Exp/Cntr=.3,.1

Type RM Length L Ch R = 1 ,14      ,50,50,50
#Sta/Elev= 16
     -10   34.29       0   34.29       2   32.99     3.5   32.49     5.2   32.49
     5.8   31.99     6.4   31.99       7   32.49     8.8   32.89     9.1   33.89
     9.5   34.99    10.7   34.99    11.3   35.49    11.7   35.49    11.9   35.29
    21.9   35.29
#Mann= 3 , 0 , 0
     -10    .035       0       0    .035       0    11.3    .035       0
Bank Sta=0,11.3
XS Rating Curve= 0
Exp/Cntr=.3,.1

Type RM Length L Ch R = 1 ,13      ,50,50,50
#Sta/Elev= 13
   -12.3   33.49    -2.3   33.49       0   32.89      .6   31.99     2.2   31.39
     3.2   30.59     4.4   30.59     4.9   31.09     6.1   31.09     6.7   33.09
     7.5   33.09     8.7   32.09    18.7   32.09
#Mann= 3 , 0 , 0
   -12.3    .035       0    -2.3    .035       0     6.7    .035       0
Bank Sta=-2.3,6.7
XS Rating Curve= 0
Exp/Cntr=.3,.1

Type RM Length L Ch R = 1 ,12      ,9,9,9
#Sta/Elev= 13
   -12.3   31.56    -2.3   31.56       0   30.96      .6   30.36     2.2   30.06
     3.2   29.46     4.4   29.46     4.9   29.76     6.1   29.76     6.7   31.76
     7.5   31.76     8.7   30.76    18.7   30.76
#Mann= 3 , 0 , 0
   -12.3    .035       0    -2.3    .035       0     6.7    .035       0
Bank Sta=-2.3,6.7
XS Rating Curve= 0
Exp/Cntr=.3,.1

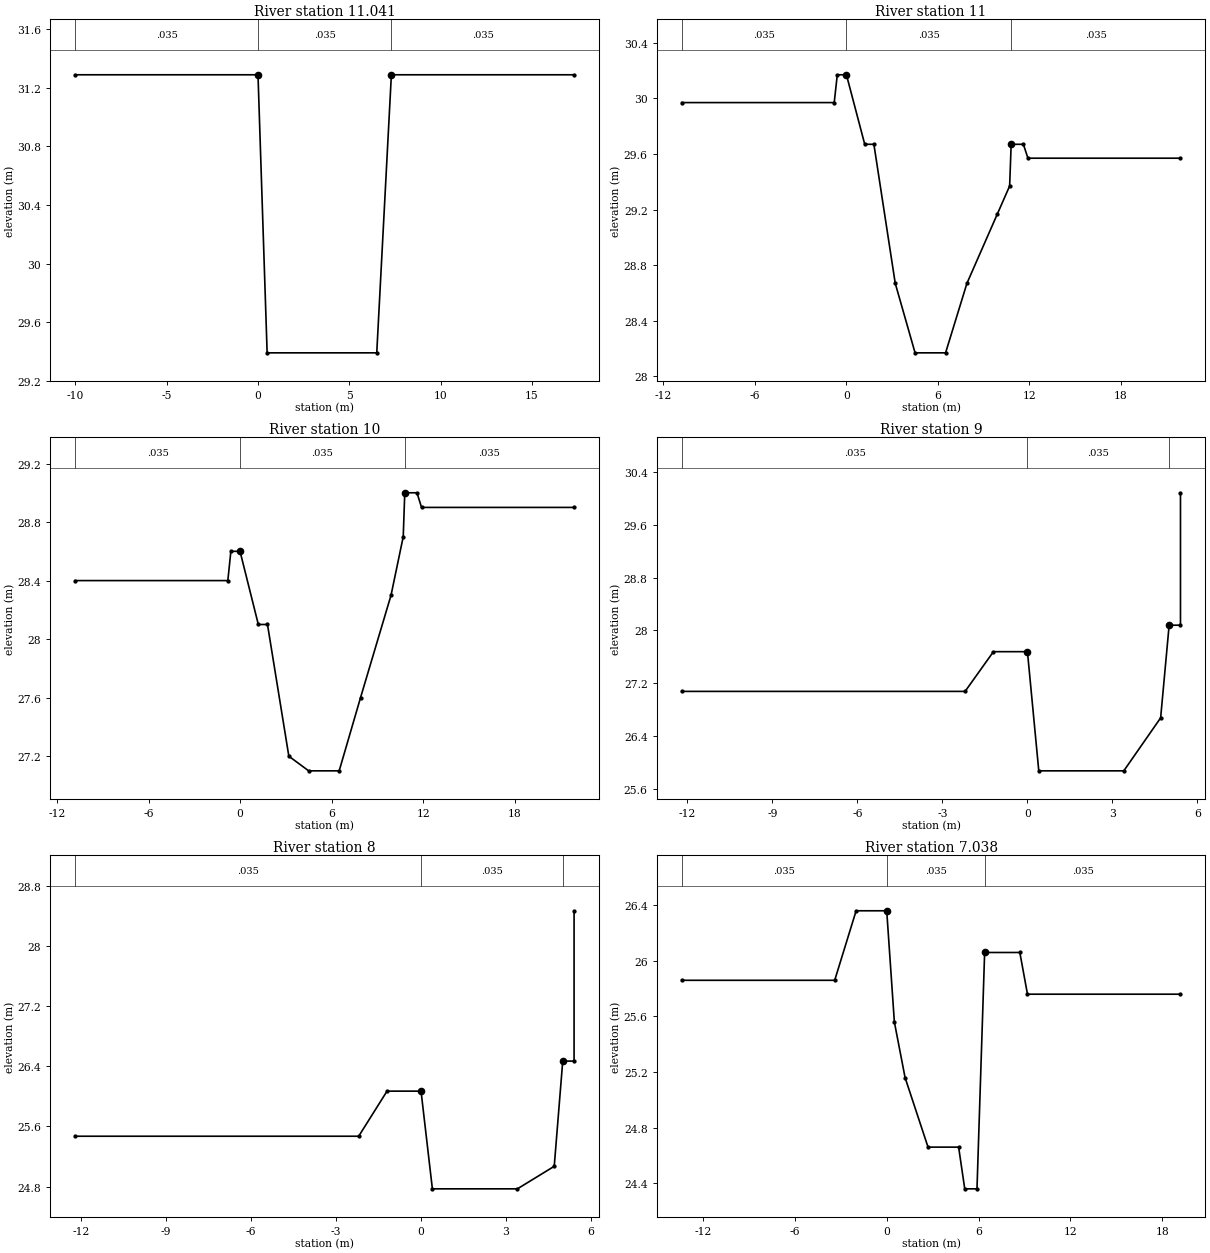
Type RM Length L Ch R = 1 ,11.041  ,41,41,41
#Sta/Elev= 6
     -10   31.29       0   31.29      .5   29.39     6.5   29.39     7.3   31.29
    17.3   31.29
#Mann= 3 , 0 , 0
     -10    .035       0       0    .035       0     7.3    .035       0
Bank Sta=0,7.3
XS Rating Curve= 0
Exp/Cntr=.3,.1

Type RM Length L Ch R = 1 ,11      ,50,50,50
#Sta/Elev= 16
   -10.8   29.97     -.8   29.97     -.6   30.17       0   30.17     1.2   29.67
     1.8   29.67     3.2   28.67     4.5   28.17     6.5   28.17     7.9   28.67
     9.9   29.17    10.7   29.37    10.8   29.67    11.6   29.67    11.9   29.57
    21.9   29.57
#Mann= 3 , 0 , 0
   -10.8    .035       0       0    .035       0    10.8    .035       0
Bank Sta=0,10.8
XS Rating Curve= 0
Exp/Cntr=.3,.1

Type RM Length L Ch R = 1 ,10      ,50,50,50
#Sta/Elev= 16
   -10.8    28.4     -.8    28.4     -.6    28.6       0    28.6     1.2    28.1
     1.8    28.1     3.2    27.2     4.5    27.1     6.5    27.1     7.9    27.6
     9.9    28.3    10.7    28.7    10.8      29    11.6      29    11.9    28.9
    21.9    28.9
#Mann= 3 , 0 , 0
   -10.8    .035       0       0    .035       0    10.8    .035       0
Bank Sta=0,10.8
XS Rating Curve= 0
Exp/Cntr=.3,.1

Type RM Length L Ch R = 1 ,9       ,50,50,50
#Sta/Elev= 10
   -12.2   27.08    -2.2   27.08    -1.2   27.68       0   27.68      .4   25.88
     3.4   25.88     4.7   26.68       5   28.08     5.4   28.08     5.4   30.08
#Mann= 3 , 0 , 0
   -12.2    .035       0       0    .035       0       5    .035       0
Bank Sta=0,5
XS Rating Curve= 0
Exp/Cntr=.3,.1

Type RM Length L Ch R = 1 ,8       ,12,12,12
#Sta/Elev= 10
   -12.2   25.47    -2.2   25.47    -1.2   26.07       0   26.07      .4   24.77
     3.4   24.77     4.7   25.07       5   26.47     5.4   26.47     5.4   28.47
#Mann= 3 , 0 , 0
   -12.2    .035       0       0    .035       0       5    .035       0
Bank Sta=0,5
XS Rating Curve= 0
Exp/Cntr=.3,.1

Type RM Length L Ch R = 1 ,7.038   ,29,29,29
#Sta/Elev= 14
   -13.4   25.86    -3.4   25.86      -2   26.36       0   26.36      .5   25.56
     1.2   25.16     2.7   24.66     4.7   24.66     5.1   24.36     5.9   24.36
     6.4   26.06     8.7   26.06     9.2   25.76    19.2   25.76
#Mann= 3 , 0 , 0
   -13.4    .035       0       0    .035       0     6.4    .035       0
Bank Sta=0,6.4
XS Rating Curve= 0
Exp/Cntr=.3,.1

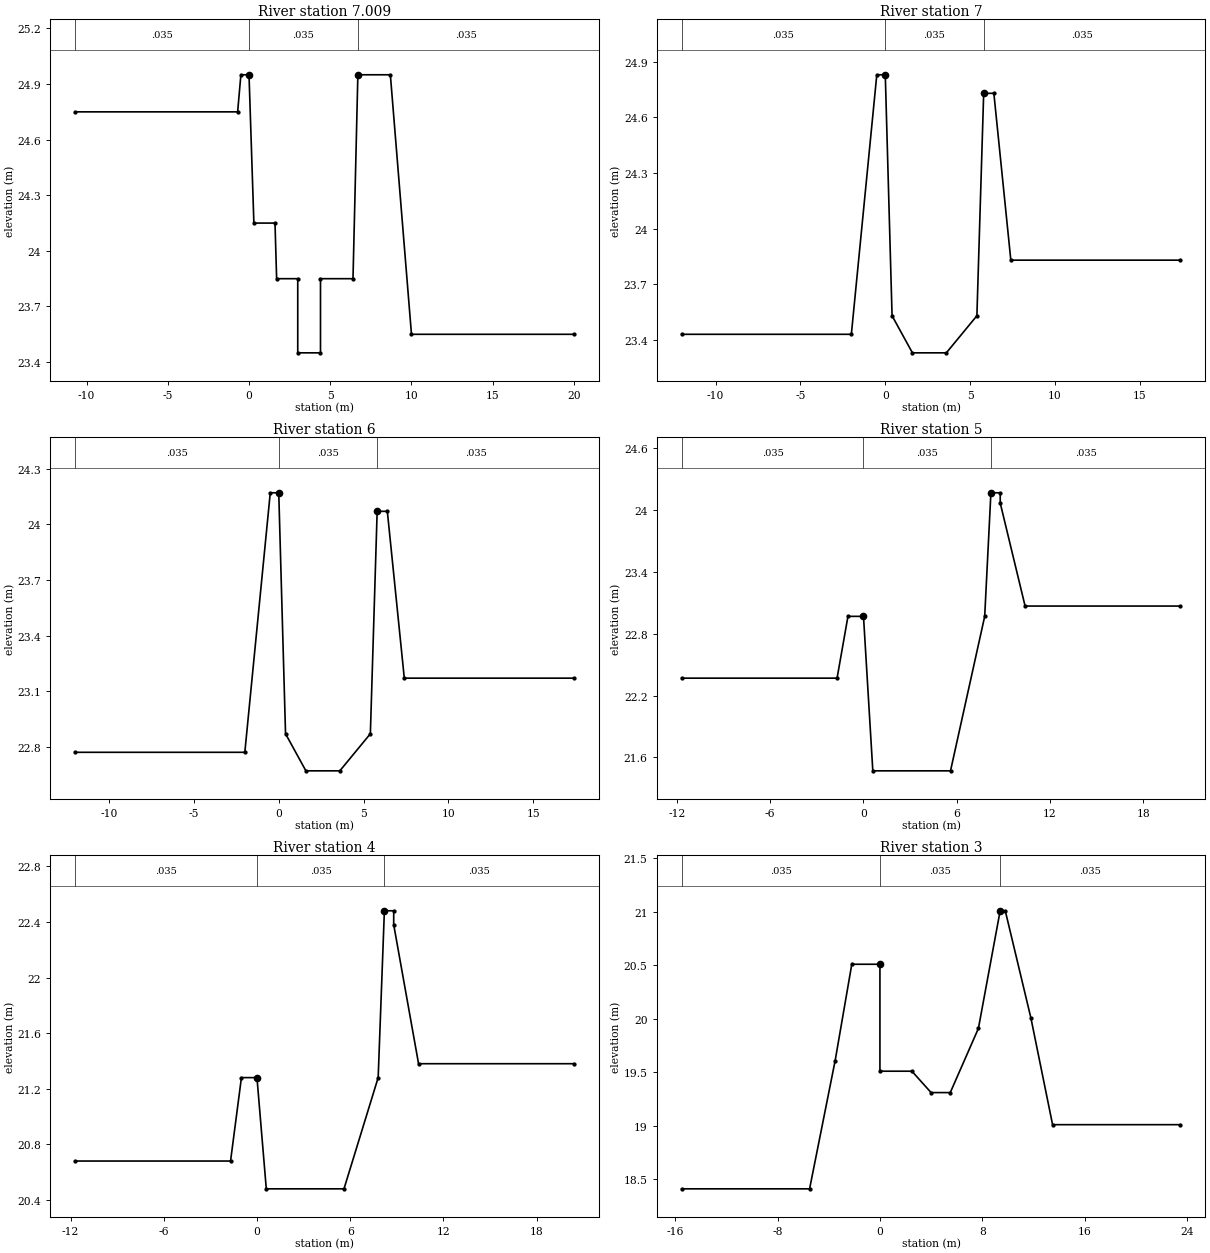
Type RM Length L Ch R = 1 ,7.009   ,9,9,9
#Sta/Elev= 16
   -10.7   24.75     -.7   24.75     -.5   24.95       0   24.95      .3   24.15
     1.6   24.15     1.7   23.85       3   23.85       3   23.45     4.4   23.45
     4.4   23.85     6.4   23.85     6.7   24.95     8.7   24.95      10   23.55
      20   23.55
#Mann= 3 , 0 , 0
   -10.7    .035       0       0    .035       0     6.7    .035       0
Bank Sta=0,6.7
XS Rating Curve= 0
Exp/Cntr=.3,.1

Type RM Length L Ch R = 1 ,7       ,50,50,50
#Sta/Elev= 12
     -12   23.43      -2   23.43     -.5   24.83       0   24.83      .4   23.53
     1.6   23.33     3.6   23.33     5.4   23.53     5.8   24.73     6.4   24.73
     7.4   23.83    17.4   23.83
#Mann= 3 , 0 , 0
     -12    .035       0       0    .035       0     5.8    .035       0
Bank Sta=0,5.8
XS Rating Curve= 0
Exp/Cntr=.3,.1

Type RM Length L Ch R = 1 ,6       ,50,50,50
#Sta/Elev= 12
     -12   22.77      -2   22.77     -.5   24.17       0   24.17      .4   22.87
     1.6   22.67     3.6   22.67     5.4   22.87     5.8   24.07     6.4   24.07
     7.4   23.17    17.4   23.17
#Mann= 3 , 0 , 0
     -12    .035       0       0    .035       0     5.8    .035       0
Bank Sta=0,5.8
XS Rating Curve= 0
Exp/Cntr=.3,.1

Type RM Length L Ch R = 1 ,5       ,50,50,50
#Sta/Elev= 12
   -11.7   22.37    -1.7   22.37      -1   22.97       0   22.97      .6   21.47
     5.6   21.47     7.8   22.97     8.2   24.17     8.8   24.17     8.8   24.07
    10.4   23.07    20.4   23.07
#Mann= 3 , 0 , 0
   -11.7    .035       0       0    .035       0     8.2    .035       0
Bank Sta=0,8.2
XS Rating Curve= 0
Exp/Cntr=.3,.1

Type RM Length L Ch R = 1 ,4       ,50,50,50
#Sta/Elev= 12
   -11.7   20.68    -1.7   20.68      -1   21.28       0   21.28      .6   20.48
     5.6   20.48     7.8   21.28     8.2   22.48     8.8   22.48     8.8   22.38
    10.4   21.38    20.4   21.38
#Mann= 3 , 0 , 0
   -11.7    .035       0       0    .035       0     8.2    .035       0
Bank Sta=0,8.2
XS Rating Curve= 0
Exp/Cntr=.3,.1

Type RM Length L Ch R = 1 ,3       ,3,3,3
#Sta/Elev= 15
   -15.5   18.41    -5.5   18.41    -3.5   19.61    -2.2   20.51       0   20.51
       0   19.51     2.5   19.51       4   19.31     5.5   19.31     7.7   19.91
     9.4   21.01     9.8   21.01    11.8   20.01    13.5   19.01    23.5   19.01
#Mann= 3 , 0 , 0
   -15.5    .035       0       0    .035       0     9.4    .035       0
Bank Sta=0,9.4
XS Rating Curve= 0
Exp/Cntr=.3,.1

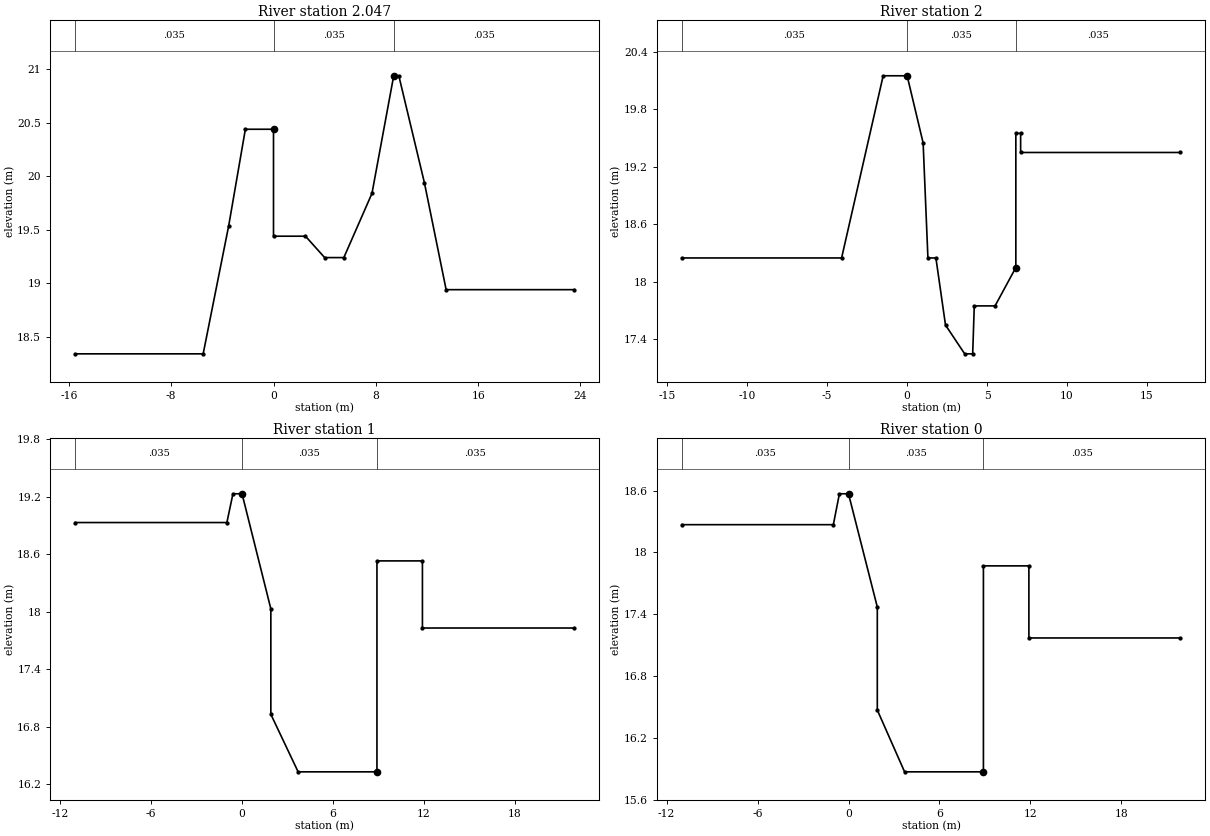
Type RM Length L Ch R = 1 ,2.047   ,47,47,47
#Sta/Elev= 15
   -15.5   18.34    -5.5   18.34    -3.5   19.54    -2.2   20.44       0   20.44
       0   19.44     2.5   19.44       4   19.24     5.5   19.24     7.7   19.84
     9.4   20.94     9.8   20.94    11.8   19.94    13.5   18.94    23.5   18.94
#Mann= 3 , 0 , 0
   -15.5    .035       0       0    .035       0     9.4    .035       0
Bank Sta=0,9.4
XS Rating Curve= 0
Exp/Cntr=.3,.1

Type RM Length L Ch R = 1 ,2       ,50,50,50
#Sta/Elev= 17
   -14.1   18.25    -4.1   18.25    -1.5   20.15       0   20.15       1   19.45
     1.3   18.25     1.8   18.25     2.4   17.55     3.6   17.25     4.1   17.25
     4.2   17.75     5.5   17.75     6.8   18.15     6.8   19.55     7.1   19.55
     7.1   19.35    17.1   19.35
#Mann= 3 , 0 , 0
   -14.1    .035       0       0    .035       0     6.8    .035       0
Bank Sta=0,6.8
XS Rating Curve= 0
Exp/Cntr=.3,.1

Type RM Length L Ch R = 1 ,1       ,50,50,50
#Sta/Elev= 12
     -11   18.93      -1   18.93     -.6   19.23       0   19.23     1.9   18.03
     1.9   16.93     3.7   16.33     8.9   16.33     8.9   18.53    11.9   18.53
    11.9   17.83    21.9   17.83
#Mann= 3 , 0 , 0
     -11    .035       0       0    .035       0     8.9    .035       0
Bank Sta=0,8.9
XS Rating Curve= 0
Exp/Cntr=.3,.1

Type RM Length L Ch R = 1 ,0       ,0,0,0
#Sta/Elev= 12
     -11   18.27      -1   18.27     -.6   18.57       0   18.57     1.9   17.47
     1.9   16.47     3.7   15.87     8.9   15.87     8.9   17.87    11.9   17.87
    11.9   17.17    21.9   17.17
#Mann= 3 , 0 , 0
     -11    .035       0       0    .035       0     8.9    .035       0
Bank Sta=0,8.9
XS Rating Curve= 0
Exp/Cntr=.3,.1

Chan Stop Cuts=-1