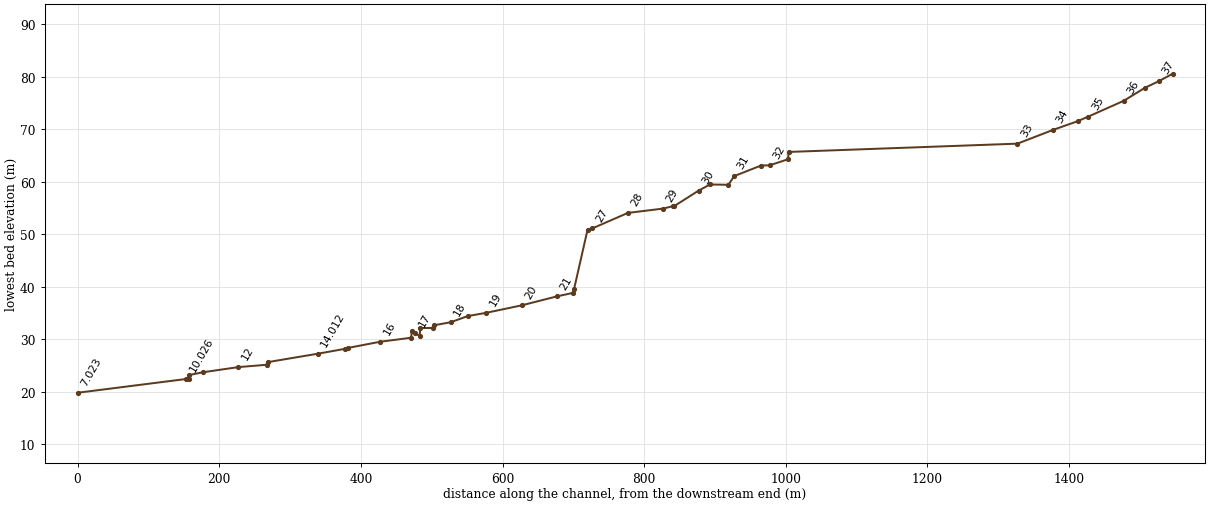
--- HEUNGKOK.prj (project) ---

Proj Title=HEUNGKOK
Current Plan=p01
Default Exp/Contr=.3,.1
SI Units
Geom File=g01
Flow File=f01
Plan File=p01
Y Axis Title=Elevation
X Axis Title(PF)=Main Channel Distance
X Axis Title(XS)=Station
BEGIN DESCRIPTION:
           BACK WATER COMPUTATION
      APPLICATION OF HEC-2 BY Samju Construction Engineering
      HEUNGKOK-STREEM : 30 YR
END DESCRIPTION:
DSS Export Rating Curves= 0
DSS Export Rating Curve Sorted= 0
DSS Export Volume Flow Curves= 0
DXF OffsetX= 0
DXF OffsetY= 0
DXF ScaleX= 1
DXF ScaleY= 10

--- HEUNGKOK.p01 (plan) ---

Plan Title=Imported Plan 01
Version=Version 3.0.1  Mar 2001
Short Identifier=Imported Pla
Geom File=g01
Flow File=f01
Subcritical Flow
K Sum by GR= 0
Std Step Tol= 0.003
Critical Tol= 0.003
Num of Std Step Trials= 20
Max Error Tol= 0.1
Flow Tol Ratio= 0.001
Split Flow NTrial= 30
Split Flow Tol= 0.02
Split Flow Ratio= 0.02
Log Output Level= 0
Friction Slope Method= 1
Unsteady Friction Slope Method= 2
Parabolic Critical Depth
Global Vel Dist= 0 , 0 , 0
Global Log Level= 0
CheckData=True
Encroach Param=-1 ,0,0, 0
Computation Interval=1HOUR
Output Interval=1HOUR
Run HTab= 0
Run UNet= 0
Run PostProcess= 0
UNET Theta= 1
UNET ZTol= 0.02
UNET ZSATol= 0.1
UNET MxIter= 20
UNET MaxInSteps= 20
UNET DtIC= 0
UNET DtMin= 0
UNET MaxCRTS= 20
UNET WFStab= 2
UNET SFStab= 1
UNET WFX= 1
UNET SFX= 1
UNET Convert EG Bridges=-1
UNET Use Existing IB Tables=-1
Instantaneous Interval=1HOUR
Write IC File= 0
Write Velocity= 0
Write Detailed= 0

--- HEUNGKOK.f01 (steady flow) ---

Flow Title=Imported Flow 01
Version=Version 3.0.1  Mar 2001
Number of Profiles= 1
Profile Names=PF 1
River Rch & RM=RIVER-1,Reach-1         ,37.019
      75
River Rch & RM=HEUNGKOK,HEUNGKOK        ,37.019
      75
Boundary for River Rch & Prof#=HEUNGKOK,HEUNGKOK        , 1
Up Type= 0
Dn Type= 3
Dn Slope=.0109
DSS Import GetInterval= 0
DSS Import GetPeak= 0
DSS Import FillOption= 0

--- HEUNGKOK.g01 (geometry) ---

Geom Title=Imported Geom 01
Version=Version 3.0.1  Mar 2001

River Reach=HEUNGKOK        ,HEUNGKOK
Reach XY= 2
              .5             .95              .5             .05

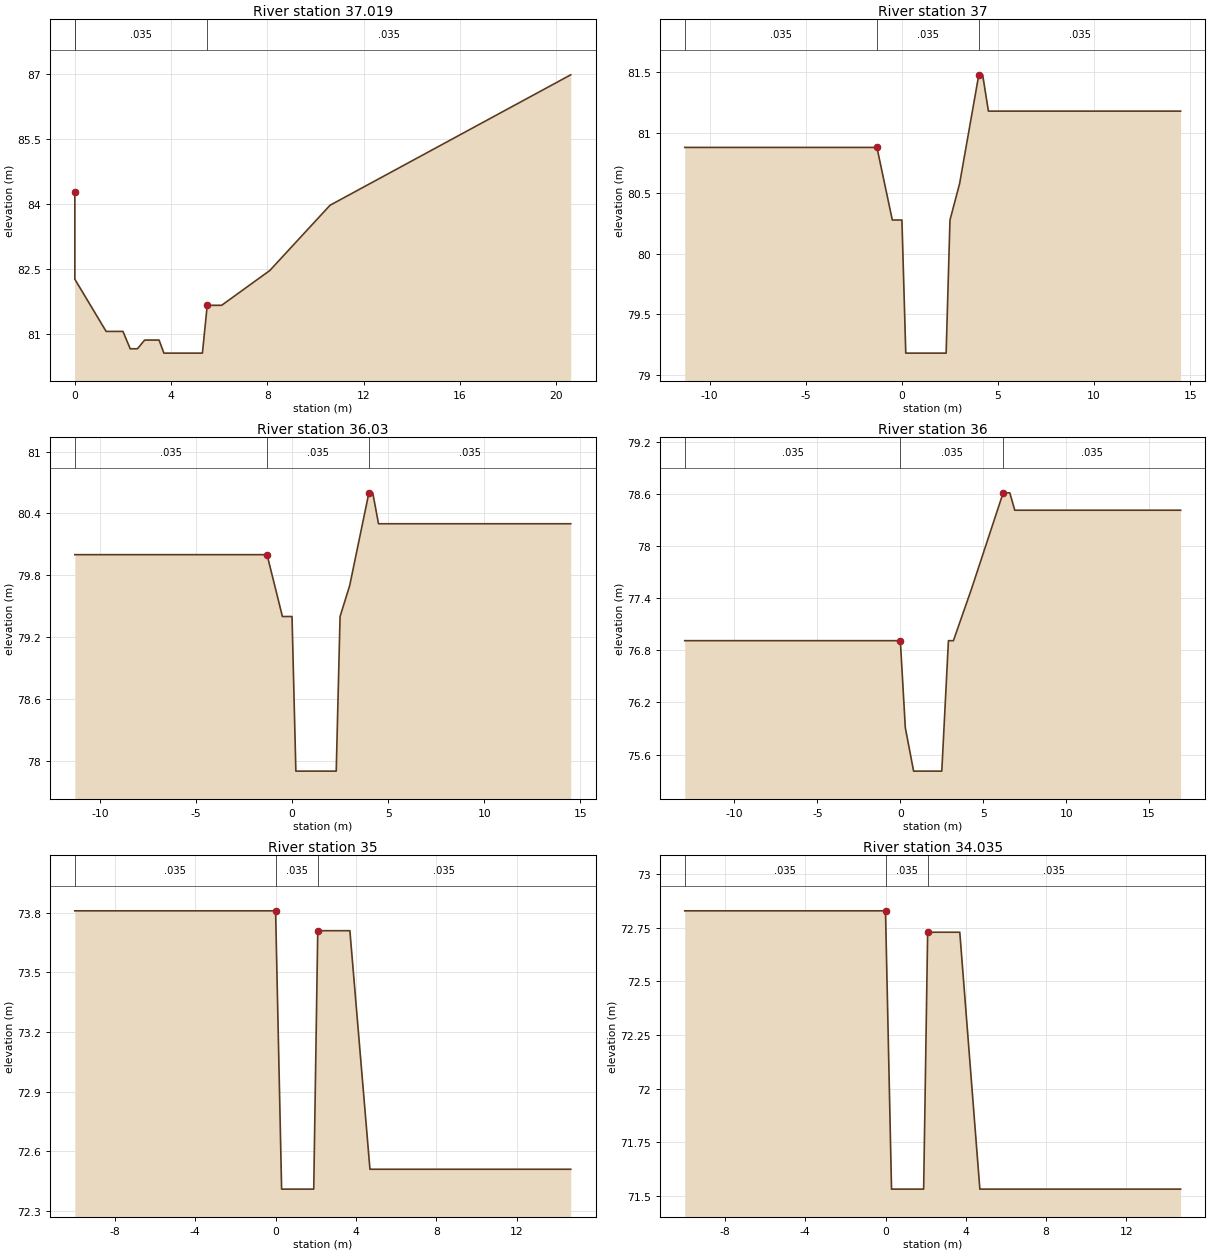
Type RM Length L Ch R = 1 ,37.019  ,19,19,19
#Sta/Elev= 16
       0   84.27       0   82.27     1.3   81.07       2   81.07     2.3   80.67
     2.6   80.67     2.9   80.87     3.5   80.87     3.7   80.57     5.3   80.57
     5.5   81.67     6.1   81.67     8.1   82.47    10.6   83.97    15.6   85.47
    20.6   86.97
#Mann= 3 , 0 , 0
       0    .035       0       0    .035       0     5.5    .035       0
Bank Sta=0,5.5
XS Rating Curve= 0
Exp/Cntr=.3,.1

Type RM Length L Ch R = 1 ,37      ,20,20,20
#Sta/Elev= 12
   -11.3   80.88    -1.3   80.88     -.5   80.28       0   80.28      .2   79.18
     2.3   79.18     2.5   80.28       3   80.58       4   81.48     4.2   81.48
     4.5   81.18    14.5   81.18
#Mann= 3 , 0 , 0
   -11.3    .035       0    -1.3    .035       0       4    .035       0
Bank Sta=-1.3,4
XS Rating Curve= 0
Exp/Cntr=.3,.1

Type RM Length L Ch R = 1 ,36.03   ,30,30,30
#Sta/Elev= 12
   -11.3      80    -1.3      80     -.5    79.4       0    79.4      .2    77.9
     2.3    77.9     2.5    79.4       3    79.7       4    80.6     4.2    80.6
     4.5    80.3    14.5    80.3
#Mann= 3 , 0 , 0
   -11.3    .035       0    -1.3    .035       0       4    .035       0
Bank Sta=-1.3,4
XS Rating Curve= 0
Exp/Cntr=.3,.1

Type RM Length L Ch R = 1 ,36      ,50,50,50
#Sta/Elev= 13
     -13   76.91      -3   76.91       0   76.91      .3   75.91      .8   75.41
     2.5   75.41     2.9   76.91     3.2   76.91     4.3   77.51     6.2   78.61
     6.6   78.61     6.9   78.41    16.9   78.41
#Mann= 3 , 0 , 0
     -13    .035       0       0    .035       0     6.2    .035       0
Bank Sta=0,6.2
XS Rating Curve= 0
Exp/Cntr=.3,.1

Type RM Length L Ch R = 1 ,35      ,15,15,15
#Sta/Elev= 8
     -10   73.81       0   73.81      .3   72.41     1.9   72.41     2.1   73.71
     3.7   73.71     4.7   72.51    14.7   72.51
#Mann= 3 , 0 , 0
     -10    .035       0       0    .035       0     2.1    .035       0
Bank Sta=0,2.1
XS Rating Curve= 0
Exp/Cntr=.3,.1

Type RM Length L Ch R = 1 ,34.035  ,35,35,35
#Sta/Elev= 8
     -10   72.83       0   72.83      .3   71.53     1.9   71.53     2.1   72.73
     3.7   72.73     4.7   71.53    14.7   71.53
#Mann= 3 , 0 , 0
     -10    .035       0       0    .035       0     2.1    .035       0
Bank Sta=0,2.1
XS Rating Curve= 0
Exp/Cntr=.3,.1

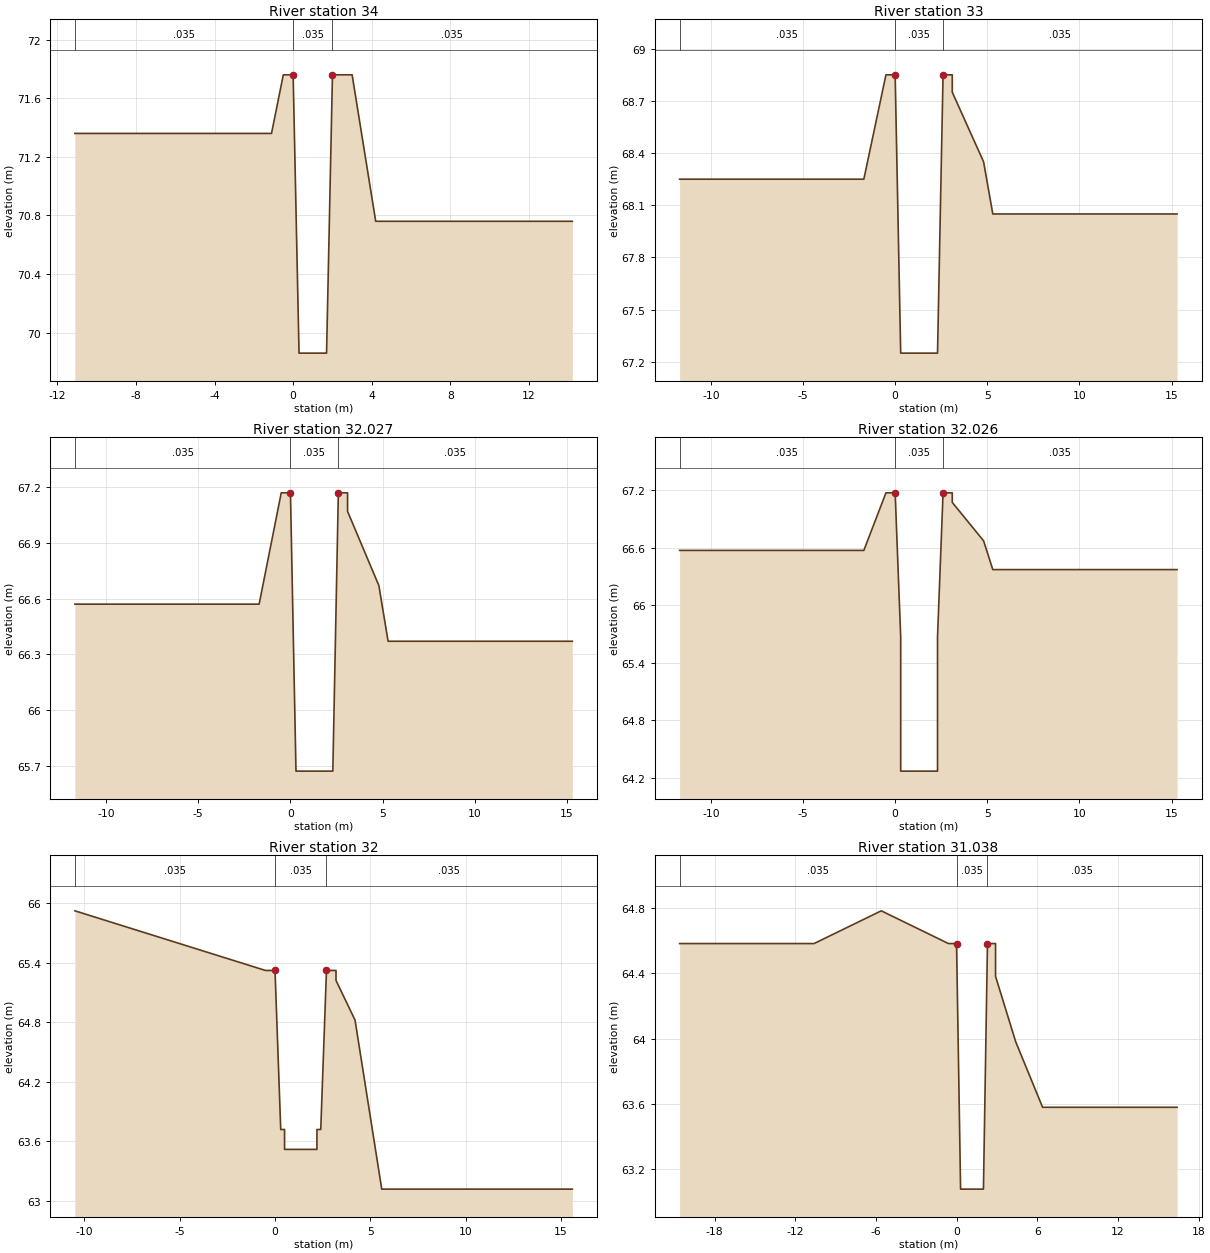
Type RM Length L Ch R = 1 ,34      ,50,50,50
#Sta/Elev= 10
   -11.1   71.36    -1.1   71.36     -.5   71.76       0   71.76      .3   69.86
     1.7   69.86       2   71.76       3   71.76     4.2   70.76    14.2   70.76
#Mann= 3 , 0 , 0
   -11.1    .035       0       0    .035       0       2    .035       0
Bank Sta=0,2
XS Rating Curve= 0
Exp/Cntr=.3,.1

Type RM Length L Ch R = 1 ,33      ,23,323,23
#Sta/Elev= 12
   -11.7   68.25    -1.7   68.25     -.5   68.85       0   68.85      .3   67.25
     2.3   67.25     2.6   68.85     3.1   68.85     3.1   68.75     4.8   68.35
     5.3   68.05    15.3   68.05
#Mann= 3 , 0 , 0
   -11.7    .035       0       0    .035       0     2.6    .035       0
Bank Sta=0,2.6
XS Rating Curve= 0
Exp/Cntr=.3,.1

Type RM Length L Ch R = 1 ,32.027  ,1,1,1
#Sta/Elev= 12
   -11.7   66.57    -1.7   66.57     -.5   67.17       0   67.17      .3   65.67
     2.3   65.67     2.6   67.17     3.1   67.17     3.1   67.07     4.8   66.67
     5.3   66.37    15.3   66.37
#Mann= 3 , 0 , 0
   -11.7    .035       0       0    .035       0     2.6    .035       0
Bank Sta=0,2.6
XS Rating Curve= 0
Exp/Cntr=.3,.1

Type RM Length L Ch R = 1 ,32.026  ,26,26,26
#Sta/Elev= 14
   -11.7   66.57    -1.7   66.57     -.5   67.17       0   67.17      .3   65.67
      .3   64.27     2.3   64.27     2.3   65.67     2.6   67.17     3.1   67.17
     3.1   67.07     4.8   66.67     5.3   66.37    15.3   66.37
#Mann= 3 , 0 , 0
   -11.7    .035       0       0    .035       0     2.6    .035       0
Bank Sta=0,2.6
XS Rating Curve= 0
Exp/Cntr=.3,.1

Type RM Length L Ch R = 1 ,32      ,12,12,12
#Sta/Elev= 16
   -10.5   65.92    -5.5   65.62     -.5   65.32       0   65.32      .3   63.72
      .5   63.72      .5   63.52     2.2   63.52     2.2   63.72     2.4   63.72
     2.7   65.32     3.2   65.32     3.2   65.22     4.2   64.82     5.6   63.12
    15.6   63.12
#Mann= 3 , 0 , 0
   -10.5    .035       0       0    .035       0     2.7    .035       0
Bank Sta=0,2.7
XS Rating Curve= 0
Exp/Cntr=.3,.1

Type RM Length L Ch R = 1 ,31.038  ,38,38,38
#Sta/Elev= 13
   -20.6   64.58   -10.6   64.58    -5.6   64.78     -.6   64.58       0   64.58
      .3   63.08       2   63.08     2.3   64.58     2.9   64.58     2.9   64.38
     4.4   63.98     6.4   63.58    16.4   63.58
#Mann= 3 , 0 , 0
   -20.6    .035       0       0    .035       0     2.3    .035       0
Bank Sta=0,2.3
XS Rating Curve= 0
Exp/Cntr=.3,.1

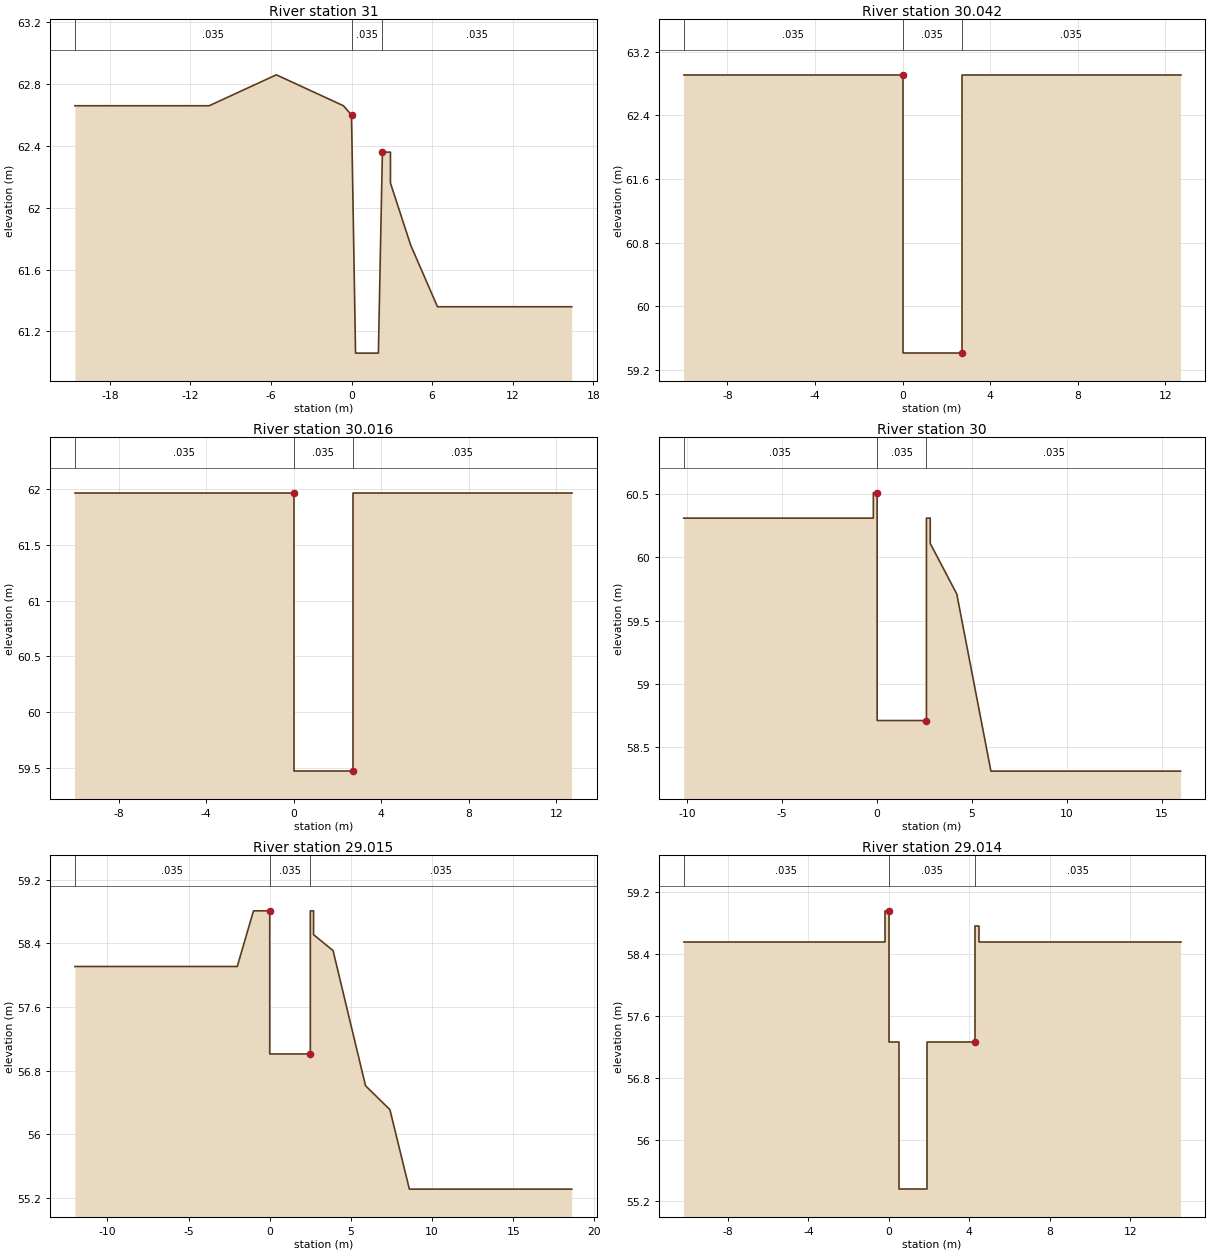
Type RM Length L Ch R = 1 ,31      ,8,8,8
#Sta/Elev= 13
   -20.6   62.66   -10.6   62.66    -5.6   62.86     -.6   62.66       0    62.6
      .3   61.06       2   61.06     2.3   62.36     2.9   62.36     2.9   62.16
     4.4   61.76     6.4   61.36    16.4   61.36
#Mann= 3 , 0 , 0
   -20.6    .035       0       0    .035       0     2.3    .035       0
Bank Sta=0,2.3
XS Rating Curve= 0
Exp/Cntr=.3,.1

Type RM Length L Ch R = 1 ,30.042  ,26,26,26
#Sta/Elev= 6
     -10   62.91       0   62.91       0   59.41     2.7   59.41     2.7   62.91
    12.7   62.91
#Mann= 3 , 0 , 0
     -10    .035       0       0    .035       0     2.7    .035       0
Bank Sta=0,2.7
XS Rating Curve= 0
Exp/Cntr=.3,.1

Type RM Length L Ch R = 1 ,30.016  ,16,16,16
#Sta/Elev= 6
     -10   61.97       0   61.97       0   59.47     2.7   59.47     2.7   61.97
    12.7   61.97
#Mann= 3 , 0 , 0
     -10    .035       0       0    .035       0     2.7    .035       0
Bank Sta=0,2.7
XS Rating Curve= 0
Exp/Cntr=.3,.1

Type RM Length L Ch R = 1 ,30      ,35,35,35
#Sta/Elev= 12
   -10.2   60.31     -.2   60.31     -.2   60.51       0   60.51       0   58.71
     2.6   58.71     2.6   60.31     2.8   60.31     2.8   60.11     4.2   59.71
       6   58.31      16   58.31
#Mann= 3 , 0 , 0
   -10.2    .035       0       0    .035       0     2.6    .035       0
Bank Sta=0,2.6
XS Rating Curve= 0
Exp/Cntr=.3,.1

Type RM Length L Ch R = 1 ,29.015  ,1,1,1
#Sta/Elev= 14
     -12   58.11      -2   58.11      -1   58.81       0   58.81       0   57.01
     2.5   57.01     2.5   58.81     2.7   58.81     2.7   58.51     3.9   58.31
     5.9   56.61     7.4   56.31     8.6   55.31    18.6   55.31
#Mann= 3 , 0 , 0
     -12    .035       0       0    .035       0     2.5    .035       0
Bank Sta=0,2.5
XS Rating Curve= 0
Exp/Cntr=.3,.1

Type RM Length L Ch R = 1 ,29.014  ,14,14,14
#Sta/Elev= 14
   -10.2   58.56     -.2   58.56     -.2   58.96       0   58.96       0   57.26
      .5   57.26      .5   55.36     1.9   55.36     1.9   57.26     4.3   57.26
     4.3   58.76     4.5   58.76     4.5   58.56    14.5   58.56
#Mann= 3 , 0 , 0
   -10.2    .035       0       0    .035       0     4.3    .035       0
Bank Sta=0,4.3
XS Rating Curve= 0
Exp/Cntr=.3,.1

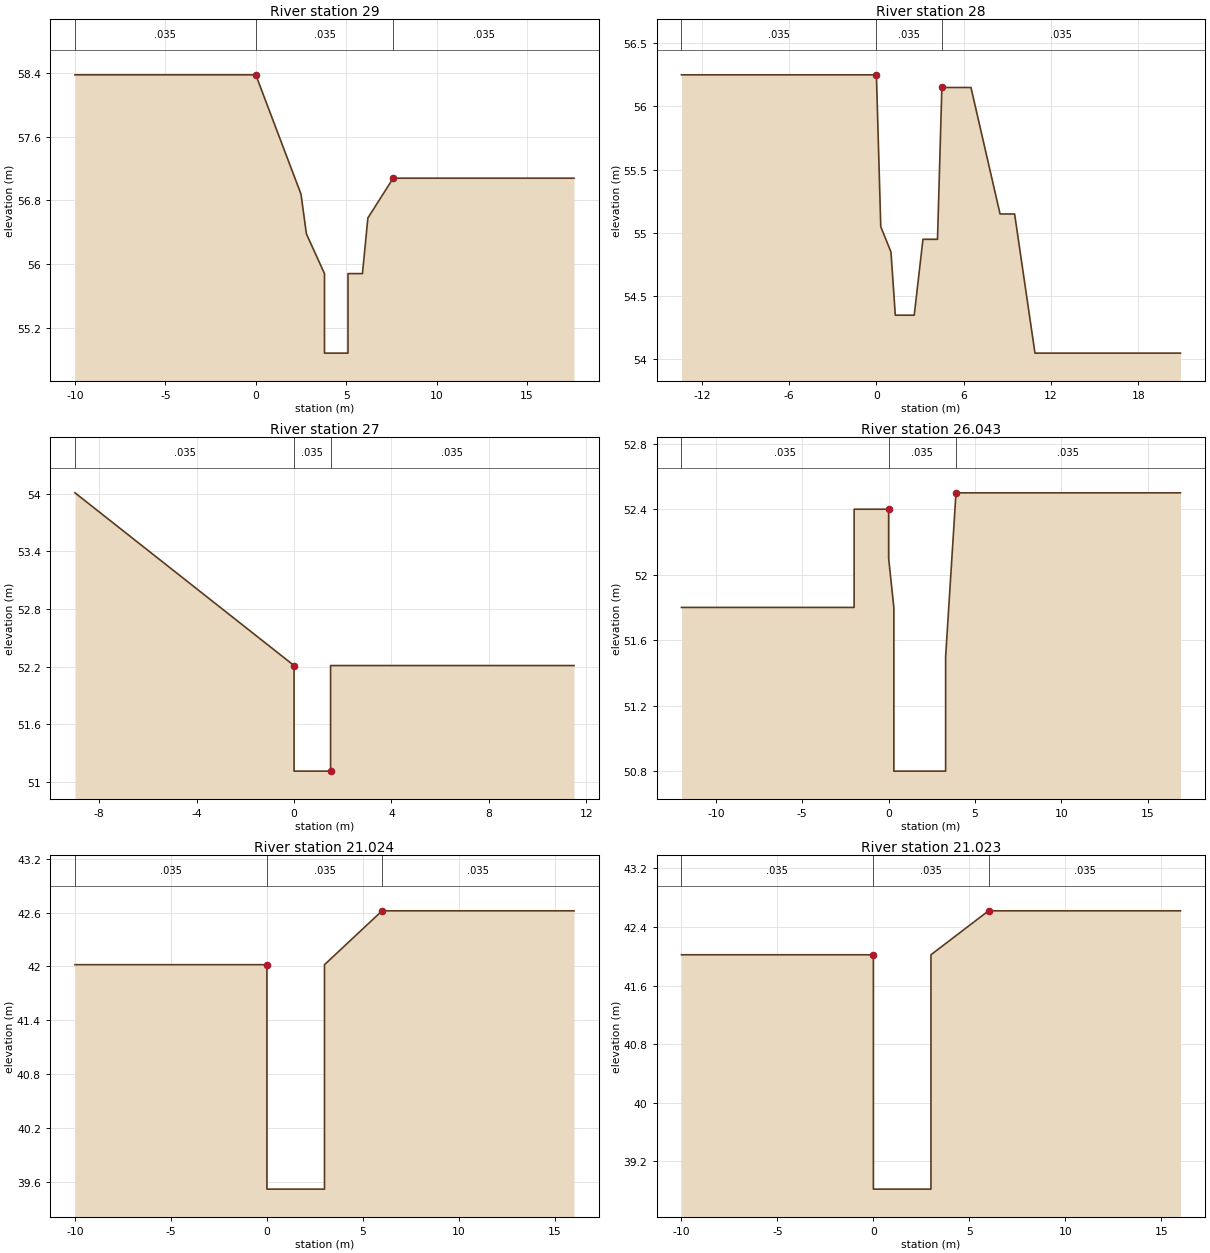
Type RM Length L Ch R = 1 ,29      ,50,50,50
#Sta/Elev= 12
     -10   58.38       0   58.38     2.5   56.88     2.8   56.38     3.8   55.88
     3.8   54.88     5.1   54.88     5.1   55.88     5.9   55.88     6.2   56.58
     7.6   57.08    17.6   57.08
#Mann= 3 , 0 , 0
     -10    .035       0       0    .035       0     7.6    .035       0
Bank Sta=0,7.6
XS Rating Curve= 0
Exp/Cntr=.3,.1

Type RM Length L Ch R = 1 ,28      ,50,50,50
#Sta/Elev= 15
   -13.4   56.25    -3.4   56.25       0   56.25      .3   55.05       1   54.85
     1.3   54.35     2.6   54.35     3.2   54.95     4.2   54.95     4.5   56.15
     6.5   56.15     8.5   55.15     9.5   55.15    10.9   54.05    20.9   54.05
#Mann= 3 , 0 , 0
   -13.4    .035       0       0    .035       0     4.5    .035       0
Bank Sta=0,4.5
XS Rating Curve= 0
Exp/Cntr=.3,.1

Type RM Length L Ch R = 1 ,27      ,7,7,7
#Sta/Elev= 8
      -9   54.01      -6   53.41      -3   52.81       0   52.21       0   51.11
     1.5   51.11     1.5   52.21    11.5   52.21
#Mann= 3 , 0 , 0
      -9    .035       0       0    .035       0     1.5    .035       0
Bank Sta=0,1.5
XS Rating Curve= 0
Exp/Cntr=.3,.1

Type RM Length L Ch R = 1 ,26.043  ,19,19,19
#Sta/Elev= 12
     -12    51.8      -2    51.8      -2    52.4       0    52.4       0    52.1
      .3    51.8      .3    50.8     3.3    50.8     3.3    51.5     3.9    52.5
     6.9    52.5    16.9    52.5
#Mann= 3 , 0 , 0
     -12    .035       0       0    .035       0     3.9    .035       0
Bank Sta=0,3.9
XS Rating Curve= 0
Exp/Cntr=.3,.1

Type RM Length L Ch R = 1 ,21.024  ,1,1,1
#Sta/Elev= 7
     -10   42.02       0   42.02       0   39.52       3   39.52       3   42.02
       6   42.62      16   42.62
#Mann= 3 , 0 , 0
     -10    .035       0       0    .035       0       6    .035       0
Bank Sta=0,6
XS Rating Curve= 0
Exp/Cntr=.3,.1

Type RM Length L Ch R = 1 ,21.023  ,23,23,23
#Sta/Elev= 9
     -10   42.02       0   42.02       0   39.52       0   38.82       3   38.82
       3   39.52       3   42.02       6   42.62      16   42.62
#Mann= 3 , 0 , 0
     -10    .035       0       0    .035       0       6    .035       0
Bank Sta=0,6
XS Rating Curve= 0
Exp/Cntr=.3,.1

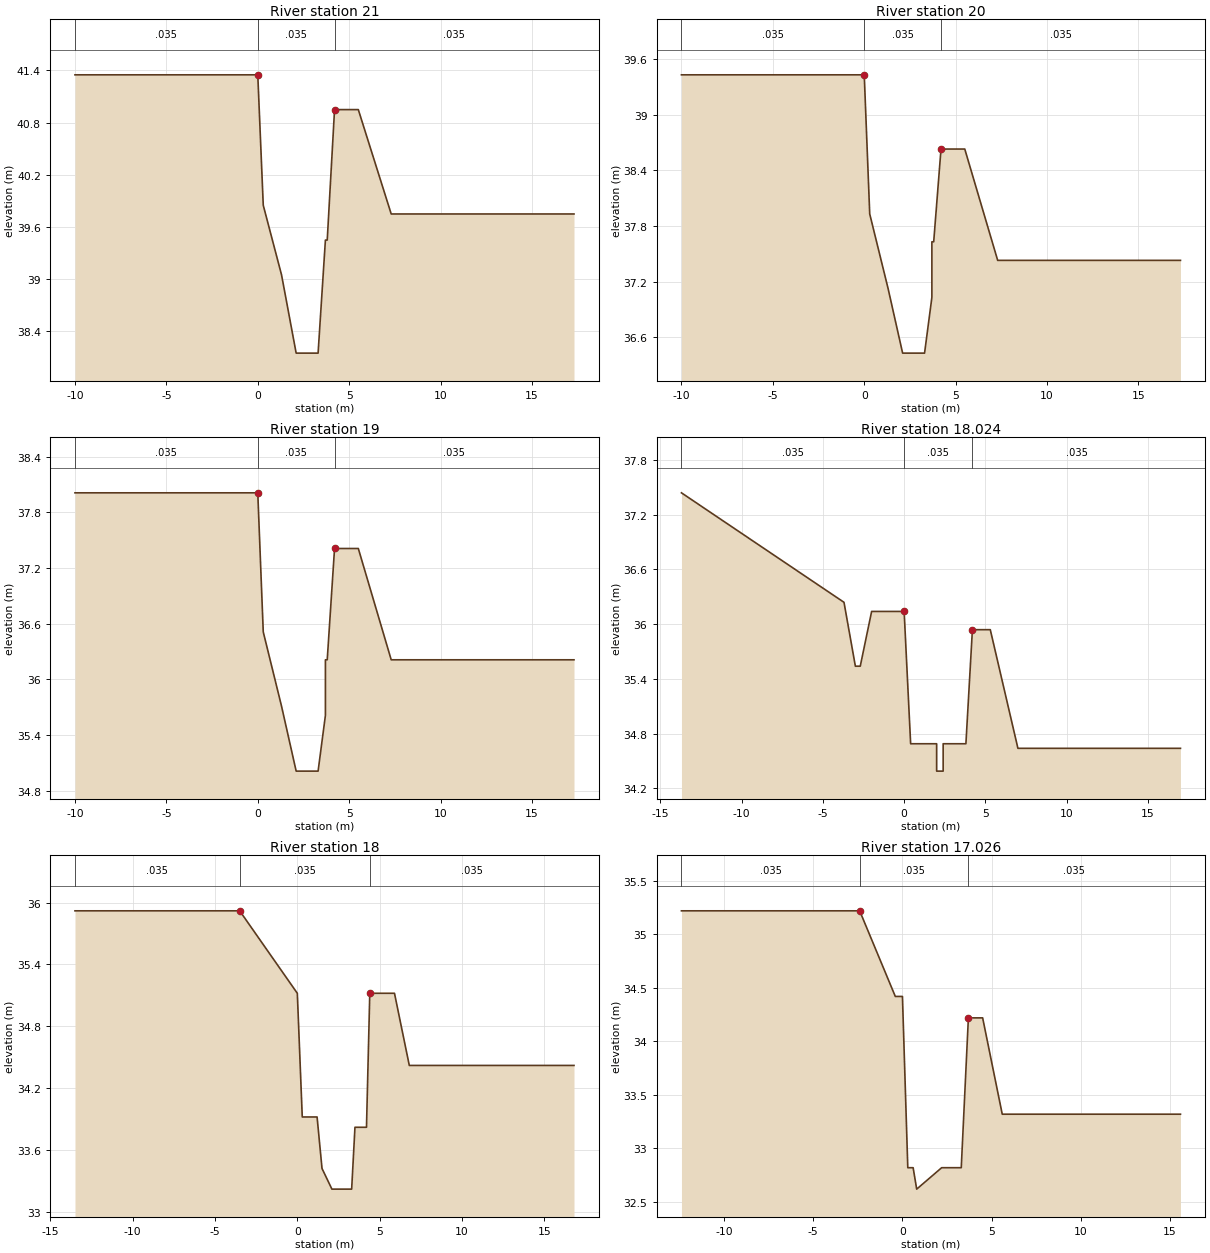
Type RM Length L Ch R = 1 ,21      ,50,50,50
#Sta/Elev= 12
     -10   41.35       0   41.35      .3   39.85     1.3   39.05     2.1   38.15
     3.3   38.15     3.7   39.45     3.8   39.45     4.2   40.95     5.5   40.95
     7.3   39.75    17.3   39.75
#Mann= 3 , 0 , 0
     -10    .035       0       0    .035       0     4.2    .035       0
Bank Sta=0,4.2
XS Rating Curve= 0
Exp/Cntr=.3,.1

Type RM Length L Ch R = 1 ,20      ,50,50,50
#Sta/Elev= 13
     -10   39.43       0   39.43      .3   37.93     1.3   37.13     2.1   36.43
     3.3   36.43     3.7   37.03     3.7   37.63     3.8   37.63     4.2   38.63
     5.5   38.63     7.3   37.43    17.3   37.43
#Mann= 3 , 0 , 0
     -10    .035       0       0    .035       0     4.2    .035       0
Bank Sta=0,4.2
XS Rating Curve= 0
Exp/Cntr=.3,.1

Type RM Length L Ch R = 1 ,19      ,26,26,26
#Sta/Elev= 13
     -10   38.01       0   38.01      .3   36.51     1.3   35.71     2.1   35.01
     3.3   35.01     3.7   35.61     3.7   36.21     3.8   36.21     4.2   37.41
     5.5   37.41     7.3   36.21    17.3   36.21
#Mann= 3 , 0 , 0
     -10    .035       0       0    .035       0     4.2    .035       0
Bank Sta=0,4.2
XS Rating Curve= 0
Exp/Cntr=.3,.1

Type RM Length L Ch R = 1 ,18.024  ,24,24,24
#Sta/Elev= 17
   -13.7   37.44    -8.7   36.84    -3.7   36.24      -3   35.54    -2.7   35.54
      -2   36.14       0   36.14      .4   34.69       2   34.69       2   34.39
     2.4   34.39     2.4   34.69     3.8   34.69     4.2   35.94     5.3   35.94
       7   34.64      17   34.64
#Mann= 3 , 0 , 0
   -13.7    .035       0       0    .035       0     4.2    .035       0
Bank Sta=0,4.2
XS Rating Curve= 0
Exp/Cntr=.3,.1

Type RM Length L Ch R = 1 ,18      ,24,24,24
#Sta/Elev= 14
   -13.5   35.92    -3.5   35.92       0   35.12      .3   33.92     1.2   33.92
     1.5   33.42     2.1   33.22     3.3   33.22     3.5   33.82     4.2   33.82
     4.4   35.12     5.9   35.12     6.8   34.42    16.8   34.42
#Mann= 3 , 0 , 0
   -13.5    .035       0    -3.5    .035       0     4.4    .035       0
Bank Sta=-3.5,4.4
XS Rating Curve= 0
Exp/Cntr=.3,.1

Type RM Length L Ch R = 1 ,17.026  ,1,1,1
#Sta/Elev= 14
   -12.4   35.22    -2.4   35.22     -.4   34.42       0   34.42      .3   32.82
      .6   32.82      .8   32.62      .8   32.62     2.2   32.82     3.3   32.82
     3.7   34.22     4.5   34.22     5.6   33.32    15.6   33.32
#Mann= 3 , 0 , 0
   -12.4    .035       0    -2.4    .035       0     3.7    .035       0
Bank Sta=-2.4,3.7
XS Rating Curve= 0
Exp/Cntr=.3,.1

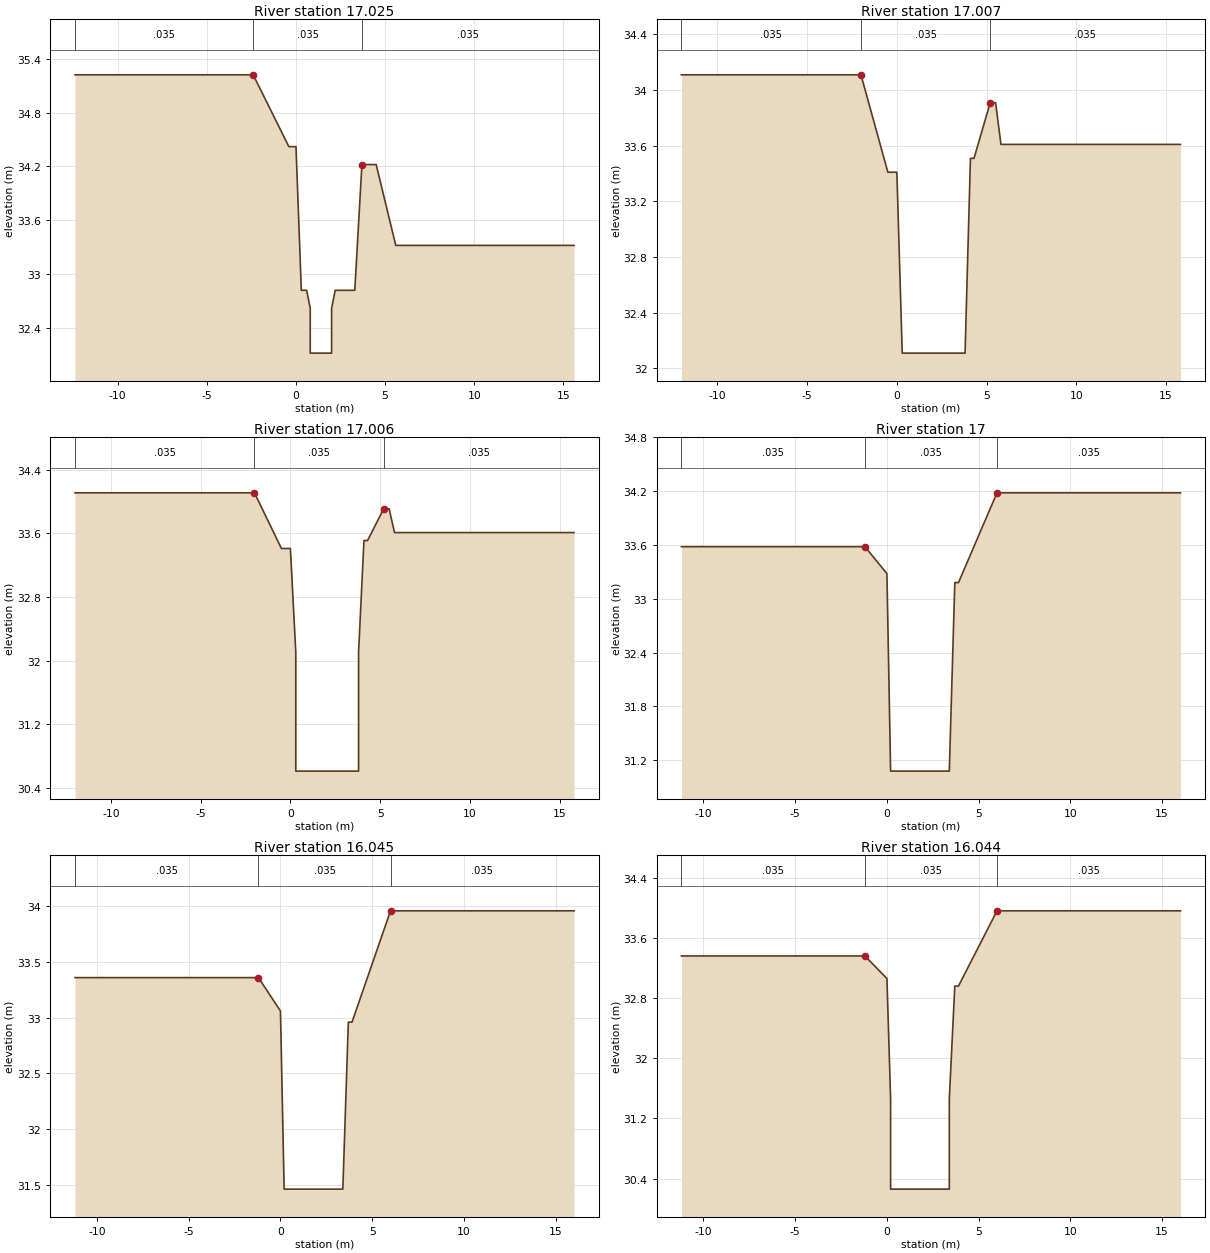
Type RM Length L Ch R = 1 ,17.025  ,18,18,18
#Sta/Elev= 16
   -12.4   35.22    -2.4   35.22     -.4   34.42       0   34.42      .3   32.82
      .6   32.82      .8   32.62      .8   32.12       2   32.12       2   32.62
     2.2   32.82     3.3   32.82     3.7   34.22     4.5   34.22     5.6   33.32
    15.6   33.32
#Mann= 3 , 0 , 0
   -12.4    .035       0    -2.4    .035       0     3.7    .035       0
Bank Sta=-2.4,3.7
XS Rating Curve= 0
Exp/Cntr=.3,.1

Type RM Length L Ch R = 1 ,17.007  ,1,1,1
#Sta/Elev= 12
     -12   34.11      -2   34.11     -.5   33.41       0   33.41      .3   32.11
     3.8   32.11     4.1   33.51     4.3   33.51     5.2   33.91     5.5   33.91
     5.8   33.61    15.8   33.61
#Mann= 3 , 0 , 0
     -12    .035       0      -2    .035       0     5.2    .035       0
Bank Sta=-2,5.2
XS Rating Curve= 0
Exp/Cntr=.3,.1

Type RM Length L Ch R = 1 ,17.006  ,6,6,6
#Sta/Elev= 14
     -12   34.11      -2   34.11     -.5   33.41       0   33.41      .3   32.11
      .3   30.61     3.8   30.61     3.8   32.11     4.1   33.51     4.3   33.51
     5.2   33.91     5.5   33.91     5.8   33.61    15.8   33.61
#Mann= 3 , 0 , 0
     -12    .035       0      -2    .035       0     5.2    .035       0
Bank Sta=-2,5.2
XS Rating Curve= 0
Exp/Cntr=.3,.1

Type RM Length L Ch R = 1 ,17      ,5,5,5
#Sta/Elev= 9
   -11.2   33.58    -1.2   33.58       0   33.28      .2   31.08     3.4   31.08
     3.7   33.18     3.9   33.18       6   34.18      16   34.18
#Mann= 3 , 0 , 0
   -11.2    .035       0    -1.2    .035       0       6    .035       0
Bank Sta=-1.2,6
XS Rating Curve= 0
Exp/Cntr=.3,.1

Type RM Length L Ch R = 1 ,16.045  ,1,1,1
#Sta/Elev= 9
   -11.2   33.36    -1.2   33.36       0   33.06      .2   31.46     3.4   31.46
     3.7   32.96     3.9   32.96       6   33.96      16   33.96
#Mann= 3 , 0 , 0
   -11.2    .035       0    -1.2    .035       0       6    .035       0
Bank Sta=-1.2,6
XS Rating Curve= 0
Exp/Cntr=.3,.1

Type RM Length L Ch R = 1 ,16.044  ,44,44,44
#Sta/Elev= 11
   -11.2   33.36    -1.2   33.36       0   33.06      .2   31.46      .2   30.26
     3.4   30.26     3.4   31.46     3.7   32.96     3.9   32.96       6   33.96
      16   33.96
#Mann= 3 , 0 , 0
   -11.2    .035       0    -1.2    .035       0       6    .035       0
Bank Sta=-1.2,6
XS Rating Curve= 0
Exp/Cntr=.3,.1

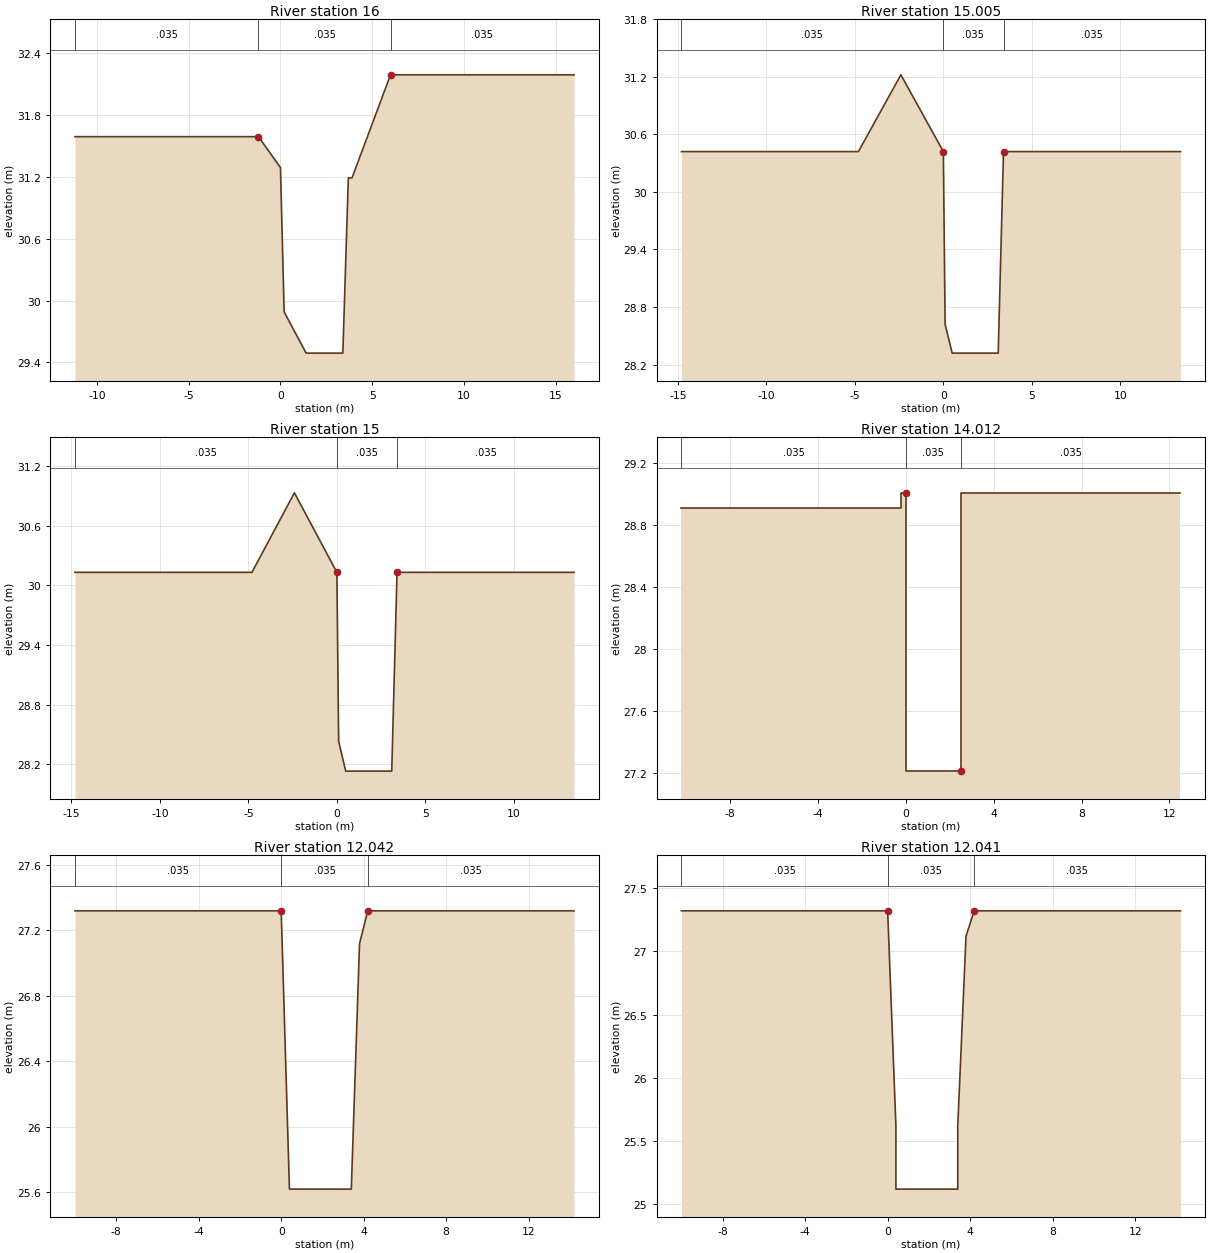
Type RM Length L Ch R = 1 ,16      ,45,45,45
#Sta/Elev= 10
   -11.2   31.59    -1.2   31.59       0   31.29      .2   29.89     1.4   29.49
     3.4   29.49     3.7   31.19     3.9   31.19       6   32.19      16   32.19
#Mann= 3 , 0 , 0
   -11.2    .035       0    -1.2    .035       0       6    .035       0
Bank Sta=-1.2,6
XS Rating Curve= 0
Exp/Cntr=.3,.1

Type RM Length L Ch R = 1 ,15.005  ,5,5,5
#Sta/Elev= 9
   -14.8   30.42    -4.8   30.42    -2.4   31.22       0   30.42      .1   28.62
      .5   28.32     3.1   28.32     3.4   30.42    13.4   30.42
#Mann= 3 , 0 , 0
   -14.8    .035       0       0    .035       0     3.4    .035       0
Bank Sta=0,3.4
XS Rating Curve= 0
Exp/Cntr=.3,.1

Type RM Length L Ch R = 1 ,15      ,38,38,38
#Sta/Elev= 9
   -14.8   30.13    -4.8   30.13    -2.4   30.93       0   30.13      .1   28.43
      .5   28.13     3.1   28.13     3.4   30.13    13.4   30.13
#Mann= 3 , 0 , 0
   -14.8    .035       0       0    .035       0     3.4    .035       0
Bank Sta=0,3.4
XS Rating Curve= 0
Exp/Cntr=.3,.1

Type RM Length L Ch R = 1 ,14.012  ,70,70,70
#Sta/Elev= 8
   -10.2   28.91     -.2   28.91     -.2   29.01       0   29.01       0   27.21
     2.5   27.21     2.5   29.01    12.5   29.01
#Mann= 3 , 0 , 0
   -10.2    .035       0       0    .035       0     2.5    .035       0
Bank Sta=0,2.5
XS Rating Curve= 0
Exp/Cntr=.3,.1

Type RM Length L Ch R = 1 ,12.042  ,1,1,1
#Sta/Elev= 7
     -10   27.32       0   27.32      .4   25.62     3.4   25.62     3.8   27.12
     4.2   27.32    14.2   27.32
#Mann= 3 , 0 , 0
     -10    .035       0       0    .035       0     4.2    .035       0
Bank Sta=0,4.2
XS Rating Curve= 0
Exp/Cntr=.3,.1

Type RM Length L Ch R = 1 ,12.041  ,41,41,41
#Sta/Elev= 9
     -10   27.32       0   27.32      .4   25.62      .4   25.12     3.4   25.12
     3.4   25.62     3.8   27.12     4.2   27.32    14.2   27.32
#Mann= 3 , 0 , 0
     -10    .035       0       0    .035       0     4.2    .035       0
Bank Sta=0,4.2
XS Rating Curve= 0
Exp/Cntr=.3,.1

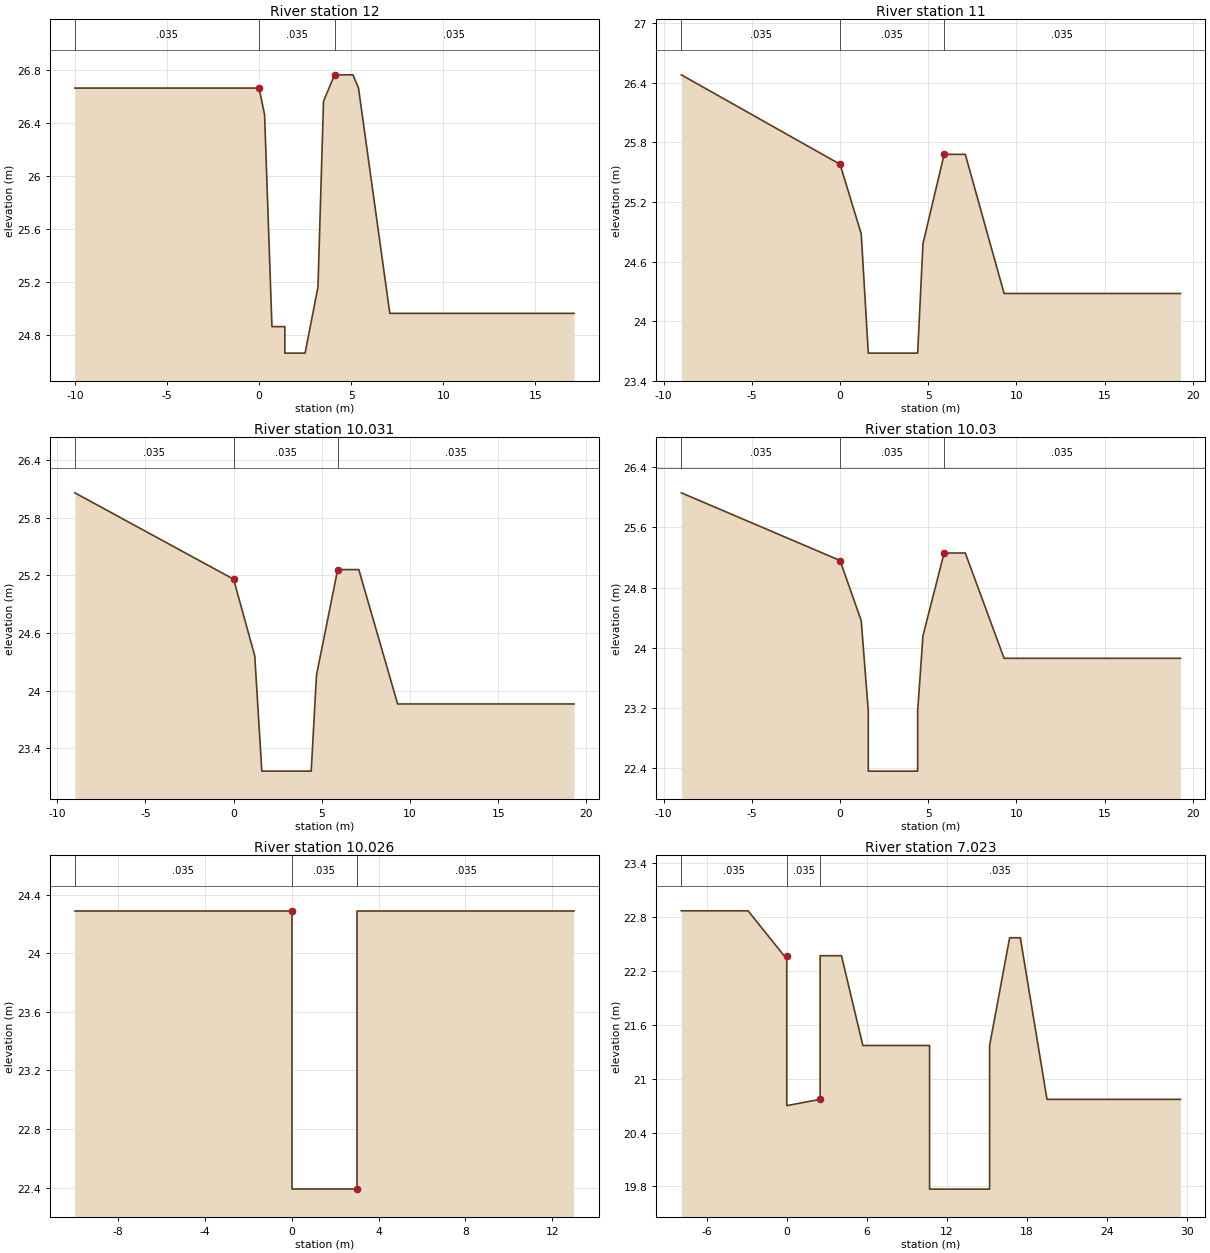
Type RM Length L Ch R = 1 ,12      ,50,50,50
#Sta/Elev= 14
     -10   26.66       0   26.66      .3   26.46      .7   24.86     1.4   24.86
     1.4   24.66     2.5   24.66     3.2   25.16     3.5   26.56     4.1   26.76
     5.1   26.76     5.4   26.66     7.1   24.96    17.1   24.96
#Mann= 3 , 0 , 0
     -10    .035       0       0    .035       0     4.1    .035       0
Bank Sta=0,4.1
XS Rating Curve= 0
Exp/Cntr=.3,.1

Type RM Length L Ch R = 1 ,11      ,19,19,19
#Sta/Elev= 12
      -9   26.48      -6   26.18      -3   25.88       0   25.58     1.2   24.88
     1.6   23.68     4.4   23.68     4.7   24.78     5.9   25.68     7.1   25.68
     9.3   24.28    19.3   24.28
#Mann= 3 , 0 , 0
      -9    .035       0       0    .035       0     5.9    .035       0
Bank Sta=0,5.9
XS Rating Curve= 0
Exp/Cntr=.3,.1

Type RM Length L Ch R = 1 ,10.031  ,1,1,1
#Sta/Elev= 12
      -9   26.06      -6   25.76      -3   25.46       0   25.16     1.2   24.36
     1.6   23.16     4.4   23.16     4.7   24.16     5.9   25.26     7.1   25.26
     9.3   23.86    19.3   23.86
#Mann= 3 , 0 , 0
      -9    .035       0       0    .035       0     5.9    .035       0
Bank Sta=0,5.9
XS Rating Curve= 0
Exp/Cntr=.3,.1

Type RM Length L Ch R = 1 ,10.03   ,4,4,4
#Sta/Elev= 14
      -9   26.06      -6   25.76      -3   25.46       0   25.16     1.2   24.36
     1.6   23.16     1.6   22.36     4.4   22.36     4.4   23.16     4.7   24.16
     5.9   25.26     7.1   25.26     9.3   23.86    19.3   23.86
#Mann= 3 , 0 , 0
      -9    .035       0       0    .035       0     5.9    .035       0
Bank Sta=0,5.9
XS Rating Curve= 0
Exp/Cntr=.3,.1

Type RM Length L Ch R = 1 ,10.026  ,153,153,153
#Sta/Elev= 6
     -10   24.29       0   24.29       0   22.39       3   22.39       3   24.29
      13   24.29
#Mann= 3 , 0 , 0
     -10    .035       0       0    .035       0       3    .035       0
Bank Sta=0,3
XS Rating Curve= 0
Exp/Cntr=.3,.1

Type RM Length L Ch R = 1 ,7.023   ,23,23,23
#Sta/Elev= 17
    -7.9   22.87    -2.9   22.87     -.2   22.37       0   22.37       0    20.7
     2.5   20.77     2.5   22.37     4.1   22.37     5.7   21.37    10.7   21.37
    10.7   19.77    15.2   19.77    15.2   21.37    16.7   22.57    17.5   22.57
    19.5   20.77    29.5   20.77
#Mann= 3 , 0 , 0
    -7.9    .035       0       0    .035       0     2.5    .035       0
Bank Sta=0,2.5
XS Rating Curve= 0
Exp/Cntr=.3,.1