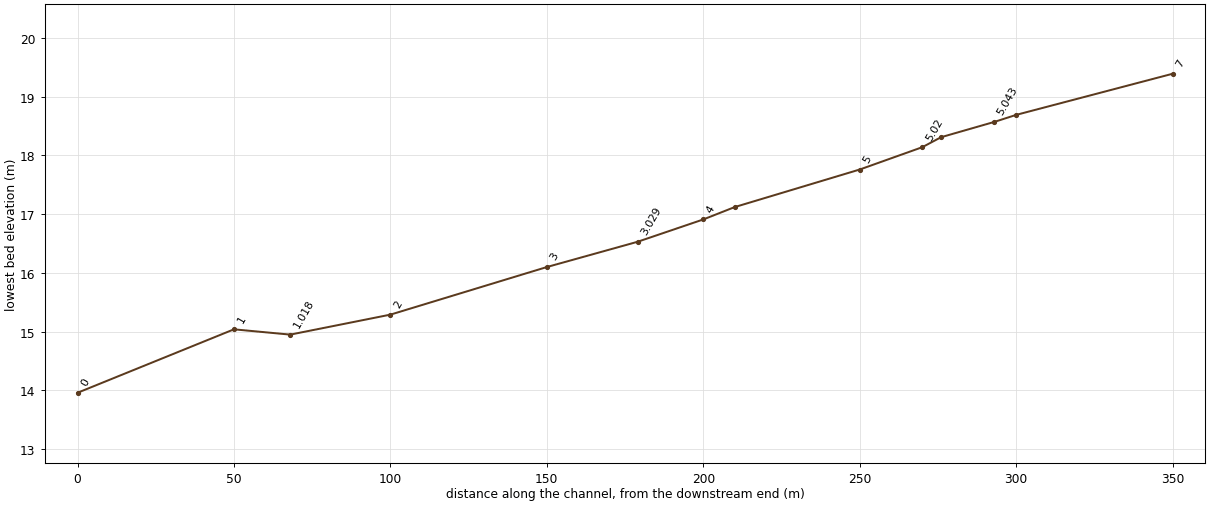
HEC-RAS study HEUNGKOK.prj: HEUNGKOK

--- HEUNGKOK.g01 (geometry) --- (continued)

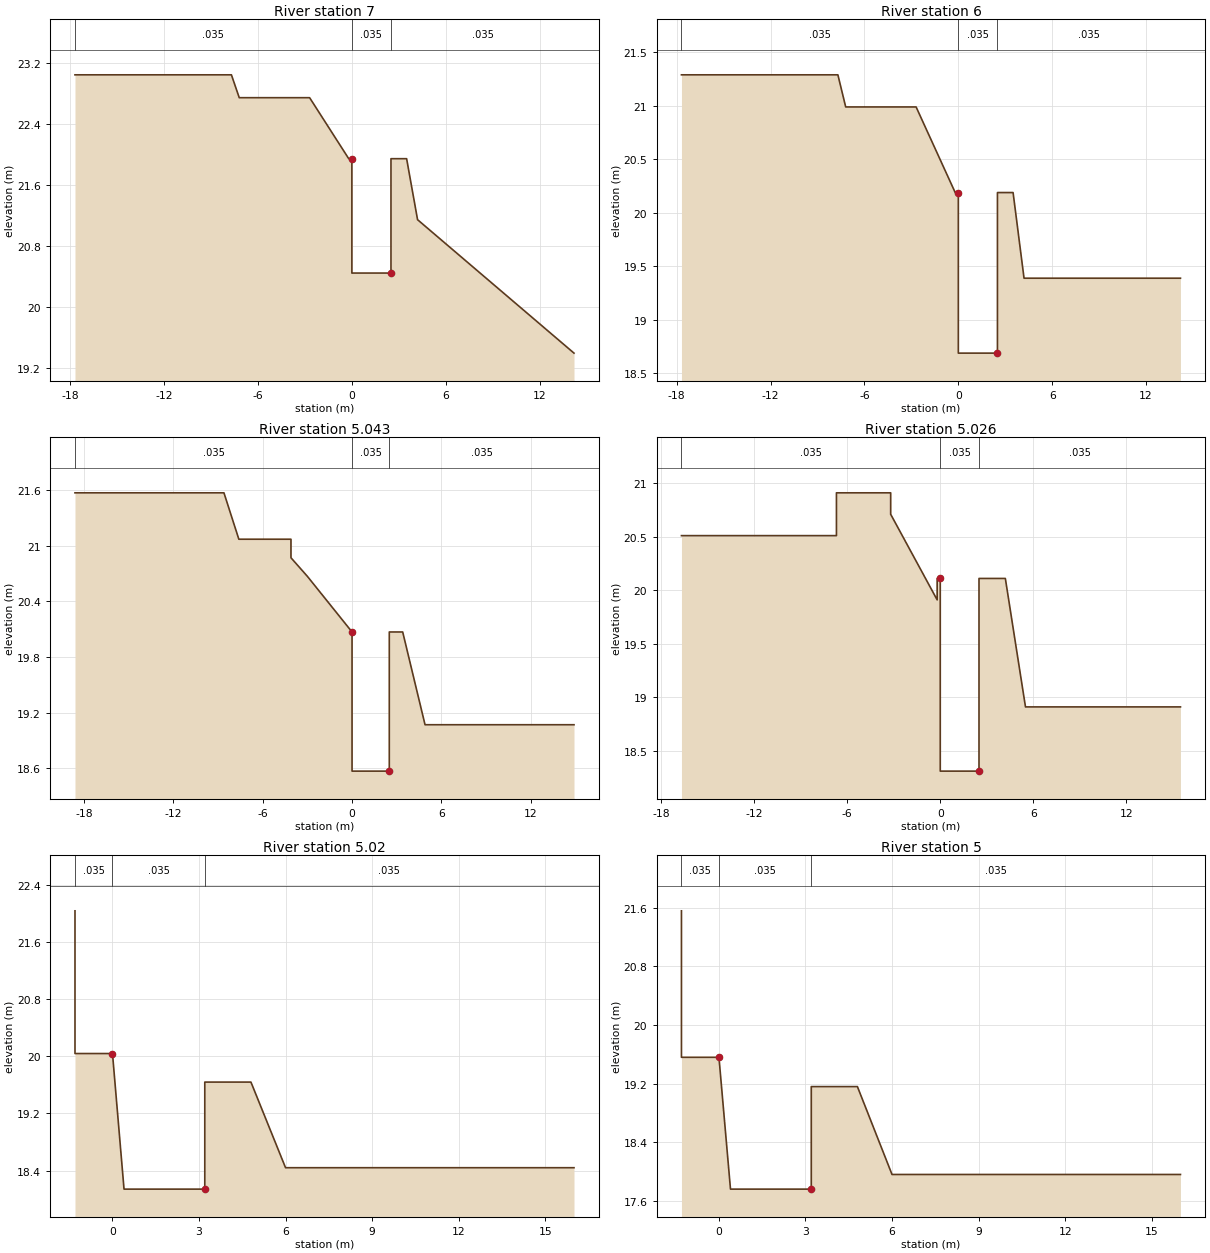
Type RM Length L Ch R = 1 ,7       ,50,50,50
#Sta/Elev= 13
   -17.7   23.04    -7.7   23.04    -7.2   22.74    -3.7   22.74    -2.7   22.74
     -.2   21.94       0   21.94       0   20.44     2.5   20.44     2.5   21.94
     3.5   21.94     4.2   21.14    14.2   19.39
#Mann= 3 , 0 , 0
   -17.7    .035       0       0    .035       0     2.5    .035       0
Bank Sta=0,2.5
XS Rating Curve= 0
Exp/Cntr=.3,.1

Type RM Length L Ch R = 1 ,6       ,7,7,7
#Sta/Elev= 13
   -17.7   21.29    -7.7   21.29    -7.2   20.99    -3.7   20.99    -2.7   20.99
     -.2   20.19       0   20.19       0   18.69     2.5   18.69     2.5   20.19
     3.5   20.19     4.2   19.39    14.2   19.39
#Mann= 3 , 0 , 0
   -17.7    .035       0       0    .035       0     2.5    .035       0
Bank Sta=0,2.5
XS Rating Curve= 0
Exp/Cntr=.3,.1

Type RM Length L Ch R = 1 ,5.043   ,17,17,17
#Sta/Elev= 13
   -18.6   21.57    -8.6   21.57    -7.6   21.07    -4.1   21.07    -4.1   20.87
      -3   20.67       0   20.07       0   18.57     2.5   18.57     2.5   20.07
     3.4   20.07     4.9   19.07    14.9   19.07
#Mann= 3 , 0 , 0
   -18.6    .035       0       0    .035       0     2.5    .035       0
Bank Sta=0,2.5
XS Rating Curve= 0
Exp/Cntr=.3,.1

Type RM Length L Ch R = 1 ,5.026   ,6,6,6
#Sta/Elev= 15
   -16.7   20.51    -6.7   20.51    -6.7   20.91    -3.2   20.91    -3.2   20.71
     -.2   19.91     -.2   20.11       0   20.11       0   18.31     2.5   18.31
     2.5   20.11     2.7   20.11     4.2   20.11     5.5   18.91    15.5   18.91
#Mann= 3 , 0 , 0
   -16.7    .035       0       0    .035       0     2.5    .035       0
Bank Sta=0,2.5
XS Rating Curve= 0
Exp/Cntr=.3,.1

Type RM Length L Ch R = 1 ,5.02    ,20,20,20
#Sta/Elev= 10
    -1.3   22.04    -1.3   20.04       0   20.04      .4   18.14     3.2   18.14
     3.2   19.64     3.4   19.64     4.8   19.64       6   18.44      16   18.44
#Mann= 3 , 0 , 0
    -1.3    .035       0       0    .035       0     3.2    .035       0
Bank Sta=0,3.2
XS Rating Curve= 0
Exp/Cntr=.3,.1

Type RM Length L Ch R = 1 ,5       ,40,40,40
#Sta/Elev= 10
    -1.3   21.56    -1.3   19.56       0   19.56      .4   17.76     3.2   17.76
     3.2   19.16     3.4   19.16     4.8   19.16       6   17.96      16   17.96
#Mann= 3 , 0 , 0
    -1.3    .035       0       0    .035       0     3.2    .035       0
Bank Sta=0,3.2
XS Rating Curve= 0
Exp/Cntr=.3,.1

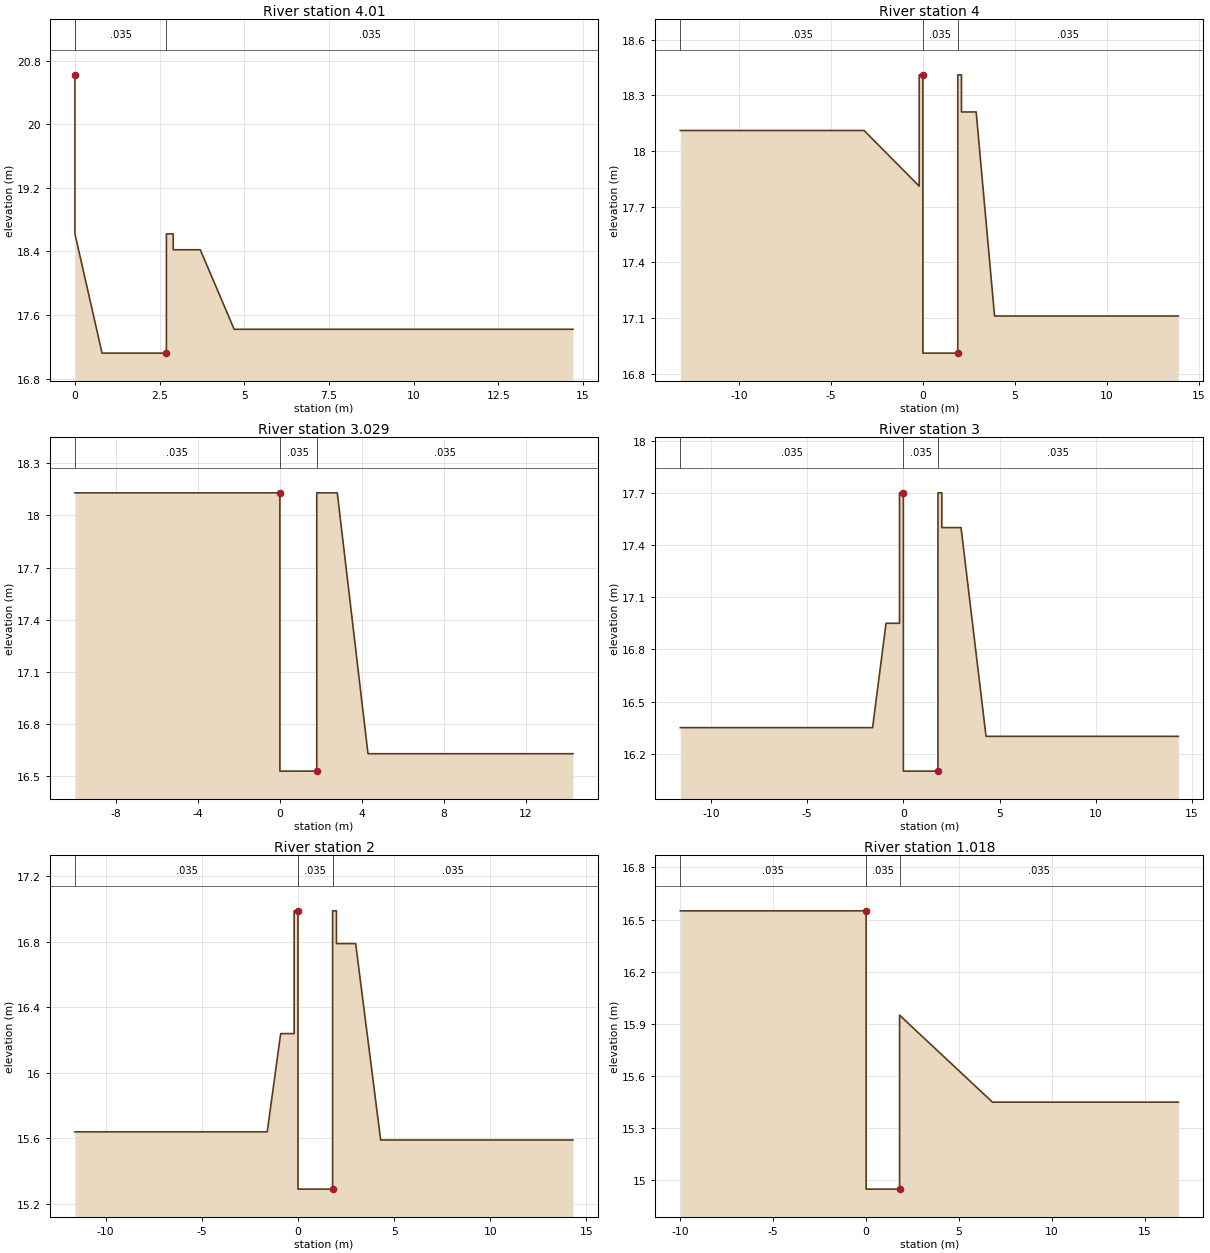
Type RM Length L Ch R = 1 ,4.01    ,10,10,10
#Sta/Elev= 10
       0   20.62       0   18.62      .8   17.12     2.7   17.12     2.7   18.62
     2.9   18.62     2.9   18.42     3.7   18.42     4.7   17.42    14.7   17.42
#Mann= 3 , 0 , 0
       0    .035       0       0    .035       0     2.7    .035       0
Bank Sta=0,2.7
XS Rating Curve= 0
Exp/Cntr=.3,.1

Type RM Length L Ch R = 1 ,4       ,21,21,21
#Sta/Elev= 13
   -13.2   18.11    -3.2   18.11     -.2   17.81     -.2   18.41       0   18.41
       0   16.91     1.9   16.91     1.9   18.41     2.1   18.41     2.1   18.21
     2.9   18.21     3.9   17.11    13.9   17.11
#Mann= 3 , 0 , 0
   -13.2    .035       0       0    .035       0     1.9    .035       0
Bank Sta=0,1.9
XS Rating Curve= 0
Exp/Cntr=.3,.1

Type RM Length L Ch R = 1 ,3.029   ,29,29,29
#Sta/Elev= 8
     -10   18.13       0   18.13       0   16.53     1.8   16.53     1.8   18.13
     2.8   18.13     4.3   16.63    14.3   16.63
#Mann= 3 , 0 , 0
     -10    .035       0       0    .035       0     1.8    .035       0
Bank Sta=0,1.8
XS Rating Curve= 0
Exp/Cntr=.3,.1

Type RM Length L Ch R = 1 ,3       ,50,50,50
#Sta/Elev= 14
   -11.6   16.35    -1.6   16.35     -.9   16.95     -.2   16.95     -.2    17.7
       0    17.7       0    16.1     1.8    16.1     1.8    17.7       2    17.7
       2    17.5       3    17.5     4.3    16.3    14.3    16.3
#Mann= 3 , 0 , 0
   -11.6    .035       0       0    .035       0     1.8    .035       0
Bank Sta=0,1.8
XS Rating Curve= 0
Exp/Cntr=.3,.1

Type RM Length L Ch R = 1 ,2       ,32,32,32
#Sta/Elev= 14
   -11.6   15.64    -1.6   15.64     -.9   16.24     -.2   16.24     -.2   16.99
       0   16.99       0   15.29     1.8   15.29     1.8   16.99       2   16.99
       2   16.79       3   16.79     4.3   15.59    14.3   15.59
#Mann= 3 , 0 , 0
   -11.6    .035       0       0    .035       0     1.8    .035       0
Bank Sta=0,1.8
XS Rating Curve= 0
Exp/Cntr=.3,.1

Type RM Length L Ch R = 1 ,1.018   ,18,18,18
#Sta/Elev= 7
     -10   16.55       0   16.55       0   14.95     1.8   14.95     1.8   15.95
     6.8   15.45    16.8   15.45
#Mann= 3 , 0 , 0
     -10    .035       0       0    .035       0     1.8    .035       0
Bank Sta=0,1.8
XS Rating Curve= 0
Exp/Cntr=.3,.1

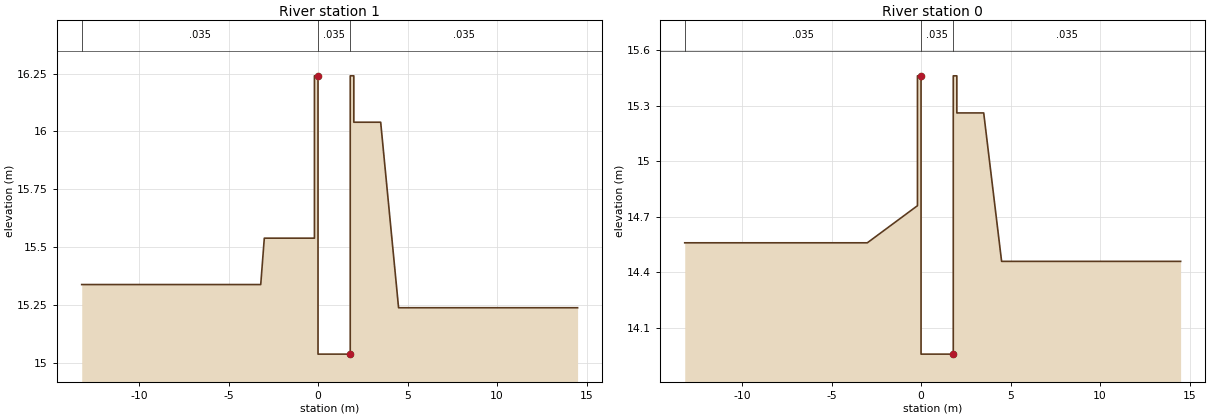
Type RM Length L Ch R = 1 ,1       ,50,50,50
#Sta/Elev= 14
   -13.2   15.34    -3.2   15.34      -3   15.54     -.2   15.54     -.2   16.24
       0   16.24       0   15.04     1.8   15.04     1.8   16.24       2   16.24
       2   16.04     3.5   16.04     4.5   15.24    14.5   15.24
#Mann= 3 , 0 , 0
   -13.2    .035       0       0    .035       0     1.8    .035       0
Bank Sta=0,1.8
XS Rating Curve= 0
Exp/Cntr=.3,.1

Type RM Length L Ch R = 1 ,0       ,0,0,0
#Sta/Elev= 14
   -13.2   14.56    -3.2   14.56      -3   14.56     -.2   14.76     -.2   15.46
       0   15.46       0   13.96     1.8   13.96     1.8   15.46       2   15.46
       2   15.26     3.5   15.26     4.5   14.46    14.5   14.46
#Mann= 3 , 0 , 0
   -13.2    .035       0       0    .035       0     1.8    .035       0
Bank Sta=0,1.8
XS Rating Curve= 0
Exp/Cntr=.3,.1

Chan Stop Cuts=-1