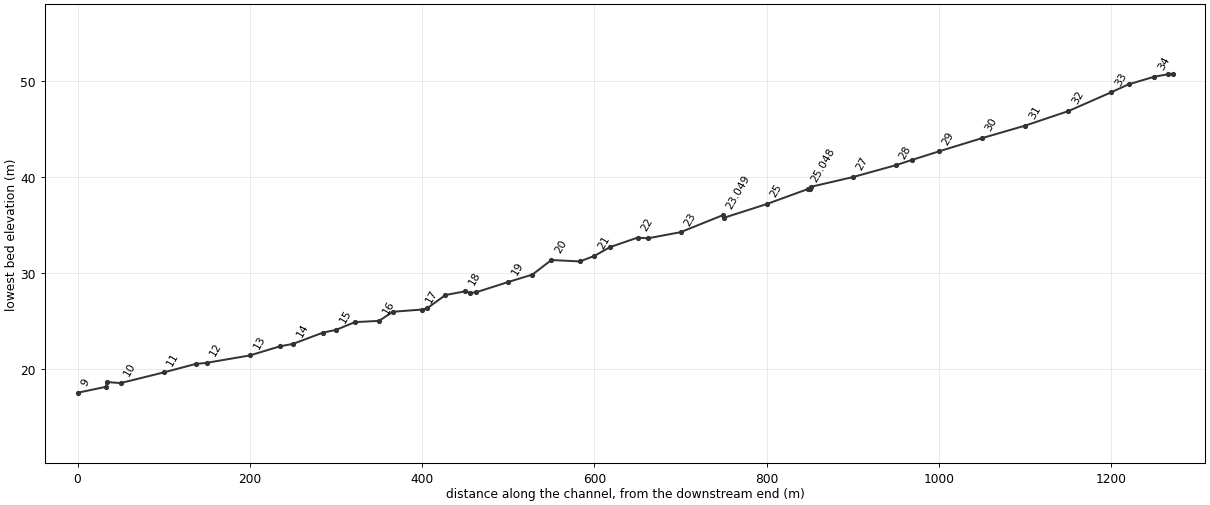
--- MYUNGAM.prj (project) ---

Proj Title=MYUNGAM
Current Plan=p01
Default Exp/Contr=.3,.1
SI Units
Geom File=g01
Flow File=f01
Plan File=p01
Y Axis Title=Elevation
X Axis Title(PF)=Main Channel Distance
X Axis Title(XS)=Station
BEGIN DESCRIPTION:
           BACK WATER COMPUTATION
      APPLICATION OF HEC-2 BY Samju Construction Engineering
      MYUNGAM-STREEM : 30 YR
END DESCRIPTION:
DSS Export Rating Curves= 0
DSS Export Rating Curve Sorted= 0
DSS Export Volume Flow Curves= 0
DXF OffsetX= 0
DXF OffsetY= 0
DXF ScaleX= 1
DXF ScaleY= 10

--- MYUNGAM.p01 (plan) ---

Plan Title=Imported Plan 01
Version=Version 3.0.1  Mar 2001
Short Identifier=Imported Pla
Geom File=g01
Flow File=f01
Subcritical Flow
K Sum by GR= 0
Std Step Tol= 0.003
Critical Tol= 0.003
Num of Std Step Trials= 20
Max Error Tol= 0.1
Flow Tol Ratio= 0.001
Split Flow NTrial= 30
Split Flow Tol= 0.02
Split Flow Ratio= 0.02
Log Output Level= 0
Friction Slope Method= 1
Unsteady Friction Slope Method= 2
Parabolic Critical Depth
Global Vel Dist= 0 , 0 , 0
Global Log Level= 0
CheckData=True
Encroach Param=-1 ,0,0, 0
Computation Interval=1HOUR
Output Interval=1HOUR
Run HTab= 0
Run UNet= 0
Run PostProcess= 0
UNET Theta= 1
UNET ZTol= 0.02
UNET ZSATol= 0.1
UNET MxIter= 20
UNET MaxInSteps= 20
UNET DtIC= 0
UNET DtMin= 0
UNET MaxCRTS= 20
UNET WFStab= 2
UNET SFStab= 1
UNET WFX= 1
UNET SFX= 1
UNET Convert EG Bridges=-1
UNET Use Existing IB Tables=-1
Instantaneous Interval=1HOUR
Write IC File= 0
Write Velocity= 0
Write Detailed= 0

--- MYUNGAM.f01 (steady flow) ---

Flow Title=Imported Flow 01
Version=Version 3.0.1  Mar 2001
Number of Profiles= 1
Profile Names=PF 1
River Rch & RM=RIVER-1,Reach-1         ,34.021
      75
River Rch & RM=MYUNGAM,MYUNGAM         ,34.021
      75
Boundary for River Rch & Prof#=MYUNGAM,MYUNGAM         , 1
Up Type= 0
Dn Type= 3
Dn Slope=.0109
DSS Import GetInterval= 0
DSS Import GetPeak= 0
DSS Import FillOption= 0

--- MYUNGAM.g01 (geometry) ---

Geom Title=Imported Geom 01
Version=Version 3.0.1  Mar 2001

River Reach=MYUNGAM         ,MYUNGAM
Reach XY= 2
              .5             .95              .5             .05

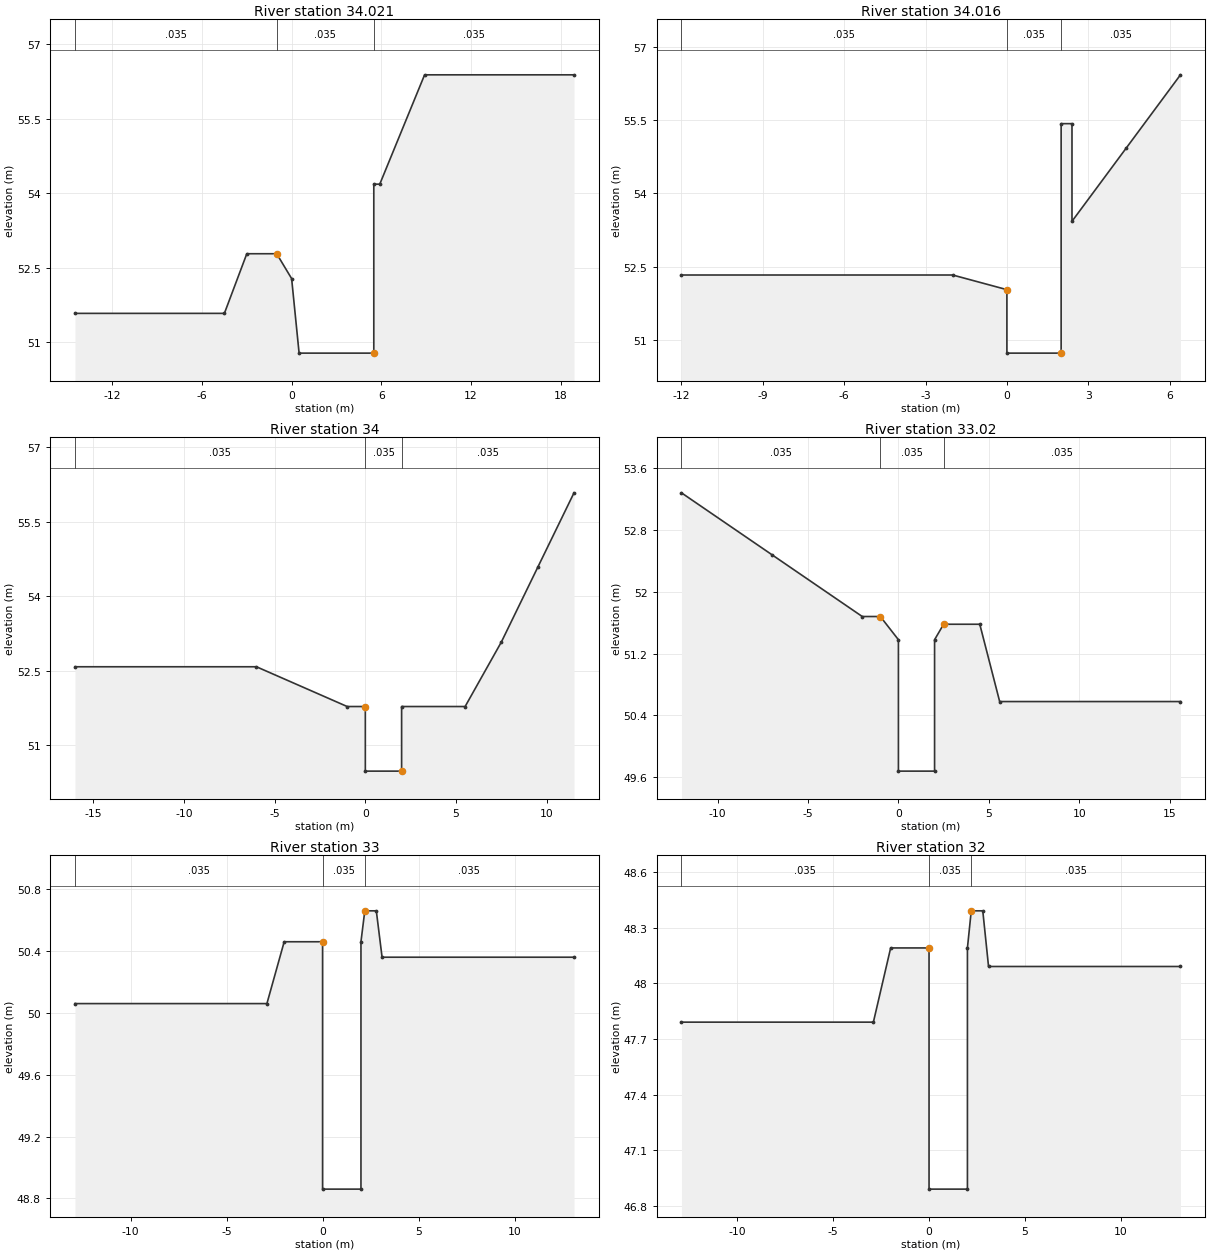
Type RM Length L Ch R = 1 ,34.021  ,5,5,5
#Sta/Elev= 11
   -14.5   51.58    -4.5   51.58      -3   52.78      -1   52.78       0   52.28
      .5   50.78     5.5   50.78     5.5   54.18     5.9   54.18     8.9   56.38
    18.9   56.38
#Mann= 3 , 0 , 0
   -14.5    .035       0      -1    .035       0     5.5    .035       0
Bank Sta=-1,5.5
XS Rating Curve= 0
Exp/Cntr=.3,.1

Type RM Length L Ch R = 1 ,34.016  ,16,16,16
#Sta/Elev= 10
     -12   52.33      -2   52.33       0   52.03       0   50.73       2   50.73
       2   55.43     2.4   55.43     2.4   53.43     4.4   54.93     6.4   56.43
#Mann= 3 , 0 , 0
     -12    .035       0       0    .035       0       2    .035       0
Bank Sta=0,2
XS Rating Curve= 0
Exp/Cntr=.3,.1

Type RM Length L Ch R = 1 ,34      ,30,30,30
#Sta/Elev= 11
     -16   52.58      -6   52.58      -1   51.78       0   51.78       0   50.48
       2   50.48       2   51.78     5.5   51.78     7.5   53.08     9.5   54.58
    11.5   56.08
#Mann= 3 , 0 , 0
     -16    .035       0       0    .035       0       2    .035       0
Bank Sta=0,2
XS Rating Curve= 0
Exp/Cntr=.3,.1

Type RM Length L Ch R = 1 ,33.02   ,20,20,20
#Sta/Elev= 12
     -12   53.28      -7   52.48      -2   51.68      -1   51.68       0   51.38
       0   49.68       2   49.68       2   51.38     2.5   51.58     4.5   51.58
     5.6   50.58    15.6   50.58
#Mann= 3 , 0 , 0
     -12    .035       0      -1    .035       0     2.5    .035       0
Bank Sta=-1,2.5
XS Rating Curve= 0
Exp/Cntr=.3,.1

Type RM Length L Ch R = 1 ,33      ,50,50,50
#Sta/Elev= 11
   -12.9   50.06    -2.9   50.06      -2   50.46       0   50.46       0   48.86
       2   48.86       2   50.46     2.2   50.66     2.8   50.66     3.1   50.36
    13.1   50.36
#Mann= 3 , 0 , 0
   -12.9    .035       0       0    .035       0     2.2    .035       0
Bank Sta=0,2.2
XS Rating Curve= 0
Exp/Cntr=.3,.1

Type RM Length L Ch R = 1 ,32      ,50,50,50
#Sta/Elev= 11
   -12.9   47.79    -2.9   47.79      -2   48.19       0   48.19       0   46.89
       2   46.89       2   48.19     2.2   48.39     2.8   48.39     3.1   48.09
    13.1   48.09
#Mann= 3 , 0 , 0
   -12.9    .035       0       0    .035       0     2.2    .035       0
Bank Sta=0,2.2
XS Rating Curve= 0
Exp/Cntr=.3,.1

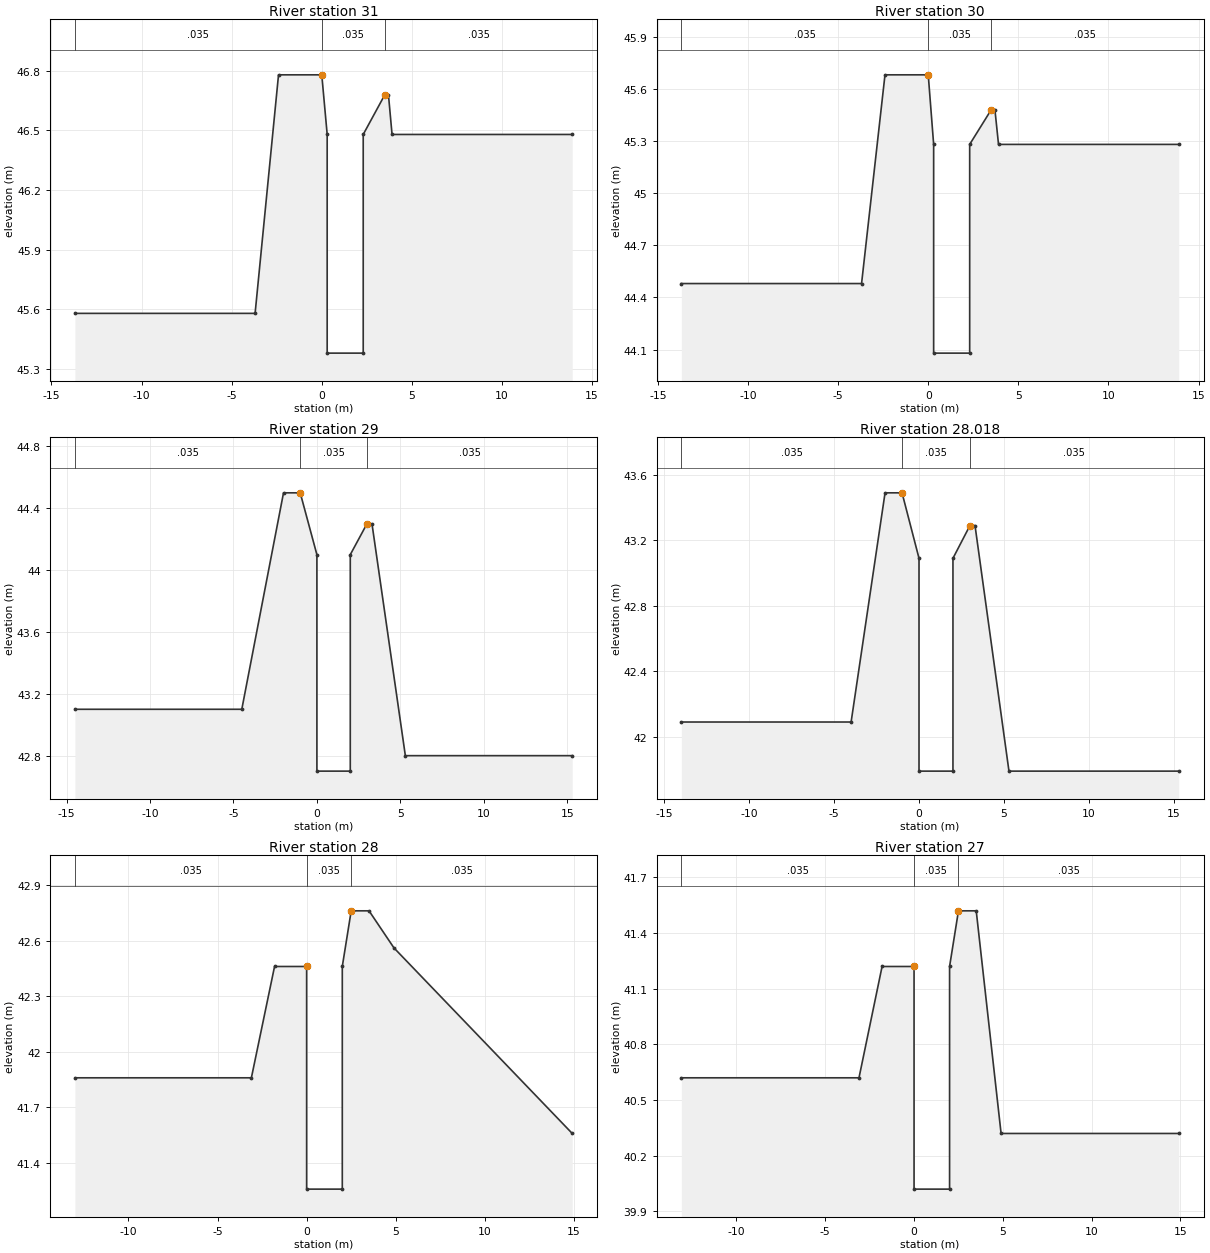
Type RM Length L Ch R = 1 ,31      ,50,50,50
#Sta/Elev= 12
   -13.7   45.58    -3.7   45.58    -2.4   46.78       0   46.78      .3   46.48
      .3   45.38     2.3   45.38     2.3   46.48     3.5   46.68     3.7   46.68
     3.9   46.48    13.9   46.48
#Mann= 3 , 0 , 0
   -13.7    .035       0       0    .035       0     3.5    .035       0
Bank Sta=0,3.5
XS Rating Curve= 0
Exp/Cntr=.3,.1

Type RM Length L Ch R = 1 ,30      ,50,50,50
#Sta/Elev= 12
   -13.7   44.48    -3.7   44.48    -2.4   45.68       0   45.68      .3   45.28
      .3   44.08     2.3   44.08     2.3   45.28     3.5   45.48     3.7   45.48
     3.9   45.28    13.9   45.28
#Mann= 3 , 0 , 0
   -13.7    .035       0       0    .035       0     3.5    .035       0
Bank Sta=0,3.5
XS Rating Curve= 0
Exp/Cntr=.3,.1

Type RM Length L Ch R = 1 ,29      ,32,32,32
#Sta/Elev= 12
   -14.5    43.1    -4.5    43.1      -2    44.5      -1    44.5       0    44.1
       0    42.7       2    42.7       2    44.1       3    44.3     3.3    44.3
     5.3    42.8    15.3    42.8
#Mann= 3 , 0 , 0
   -14.5    .035       0      -1    .035       0       3    .035       0
Bank Sta=-1,3
XS Rating Curve= 0
Exp/Cntr=.3,.1

Type RM Length L Ch R = 1 ,28.018  ,18,18,18
#Sta/Elev= 12
     -14   42.09      -4   42.09      -2   43.49      -1   43.49       0   43.09
       0   41.79       2   41.79       2   43.09       3   43.29     3.3   43.29
     5.3   41.79    15.3   41.79
#Mann= 3 , 0 , 0
     -14    .035       0      -1    .035       0       3    .035       0
Bank Sta=-1,3
XS Rating Curve= 0
Exp/Cntr=.3,.1

Type RM Length L Ch R = 1 ,28      ,50,50,50
#Sta/Elev= 11
     -13   41.86    -3.1   41.86    -1.8   42.46       0   42.46       0   41.26
       2   41.26       2   42.46     2.5   42.76     3.5   42.76     4.9   42.56
    14.9   41.56
#Mann= 3 , 0 , 0
     -13    .035       0       0    .035       0     2.5    .035       0
Bank Sta=0,2.5
XS Rating Curve= 0
Exp/Cntr=.3,.1

Type RM Length L Ch R = 1 ,27      ,49,49,49
#Sta/Elev= 11
   -13.1   40.62    -3.1   40.62    -1.8   41.22       0   41.22       0   40.02
       2   40.02       2   41.22     2.5   41.52     3.5   41.52     4.9   40.32
    14.9   40.32
#Mann= 3 , 0 , 0
   -13.1    .035       0       0    .035       0     2.5    .035       0
Bank Sta=0,2.5
XS Rating Curve= 0
Exp/Cntr=.3,.1

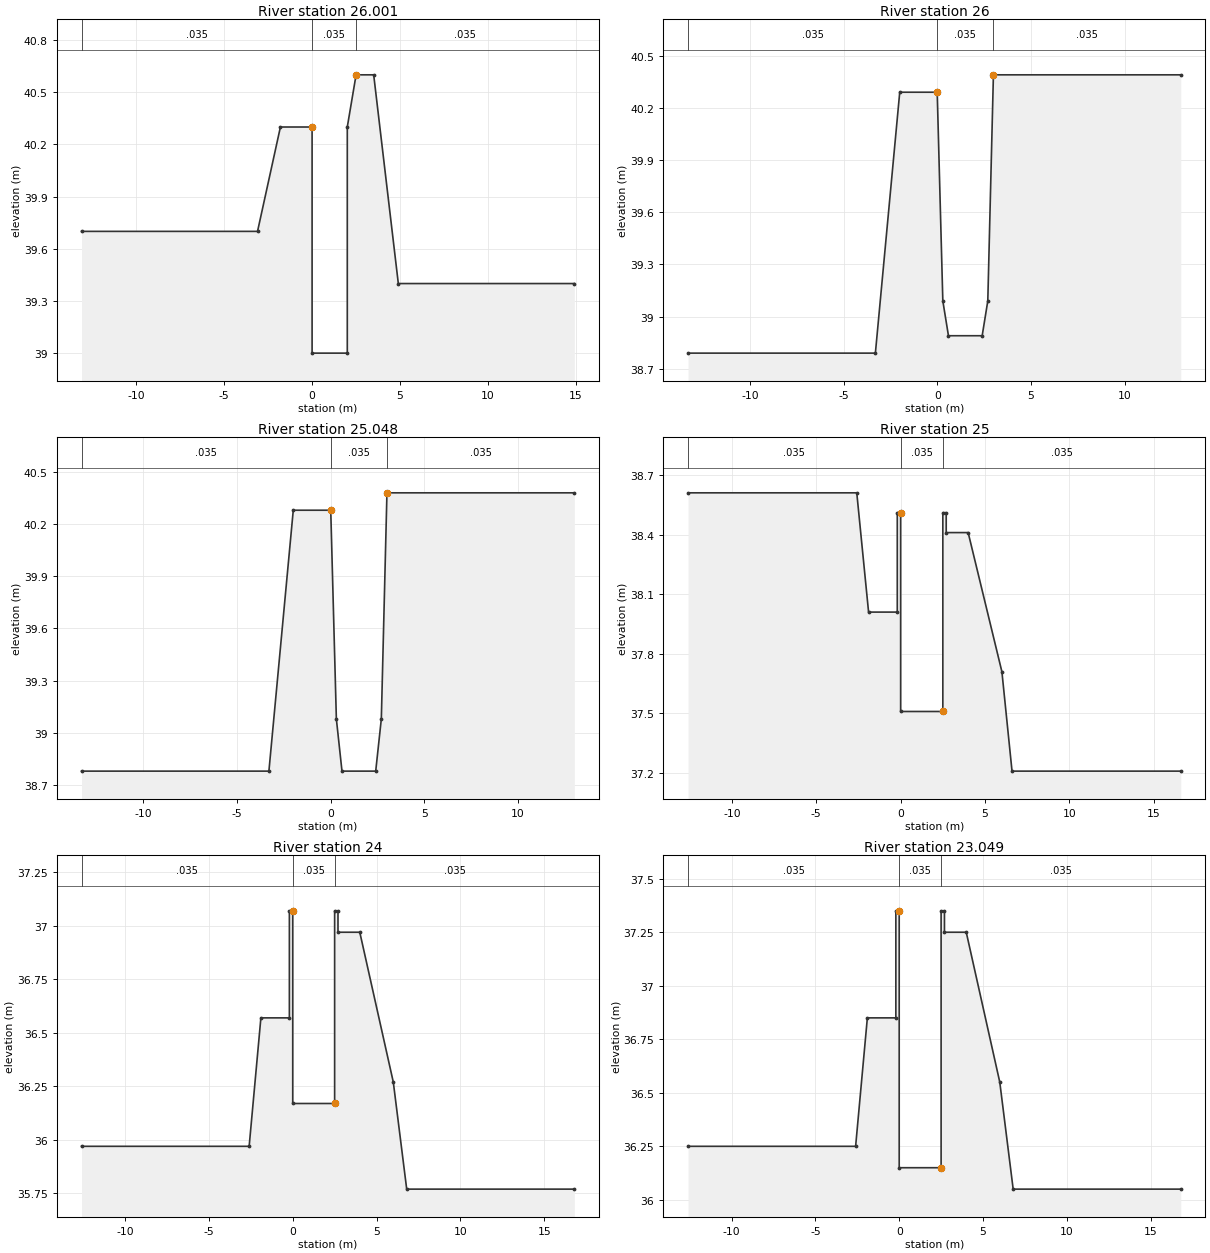
Type RM Length L Ch R = 1 ,26.001  ,1,1,1
#Sta/Elev= 11
   -13.1    39.7    -3.1    39.7    -1.8    40.3       0    40.3       0      39
       2      39       2    40.3     2.5    40.6     3.5    40.6     4.9    39.4
    14.9    39.4
#Mann= 3 , 0 , 0
   -13.1    .035       0       0    .035       0     2.5    .035       0
Bank Sta=0,2.5
XS Rating Curve= 0
Exp/Cntr=.3,.1

Type RM Length L Ch R = 1 ,26      ,2,2,2
#Sta/Elev= 10
   -13.3   38.79    -3.3   38.79      -2   40.29       0   40.29      .3   39.09
      .6   38.89     2.4   38.89     2.7   39.09       3   40.39      13   40.39
#Mann= 3 , 0 , 0
   -13.3    .035       0       0    .035       0       3    .035       0
Bank Sta=0,3
XS Rating Curve= 0
Exp/Cntr=.3,.1

Type RM Length L Ch R = 1 ,25.048  ,48,48,48
#Sta/Elev= 10
   -13.3   38.78    -3.3   38.78      -2   40.28       0   40.28      .3   39.08
      .6   38.78     2.4   38.78     2.7   39.08       3   40.38      13   40.38
#Mann= 3 , 0 , 0
   -13.3    .035       0       0    .035       0       3    .035       0
Bank Sta=0,3
XS Rating Curve= 0
Exp/Cntr=.3,.1

Type RM Length L Ch R = 1 ,25      ,50,50,50
#Sta/Elev= 15
   -12.6   38.61    -2.6   38.61    -1.9   38.01     -.2   38.01     -.2   38.51
       0   38.51       0   37.51     2.5   37.51     2.5   38.51     2.7   38.51
     2.7   38.41       4   38.41       6   37.71     6.6   37.21    16.6   37.21
#Mann= 3 , 0 , 0
   -12.6    .035       0       0    .035       0     2.5    .035       0
Bank Sta=0,2.5
XS Rating Curve= 0
Exp/Cntr=.3,.1

Type RM Length L Ch R = 1 ,24      ,1,1,1
#Sta/Elev= 15
   -12.6   35.97    -2.6   35.97    -1.9   36.57     -.2   36.57     -.2   37.07
       0   37.07       0   36.17     2.5   36.17     2.5   37.07     2.7   37.07
     2.7   36.97       4   36.97       6   36.27     6.8   35.77    16.8   35.77
#Mann= 3 , 0 , 0
   -12.6    .035       0       0    .035       0     2.5    .035       0
Bank Sta=0,2.5
XS Rating Curve= 0
Exp/Cntr=.3,.1

Type RM Length L Ch R = 1 ,23.049  ,49,49,49
#Sta/Elev= 15
   -12.6   36.25    -2.6   36.25    -1.9   36.85     -.2   36.85     -.2   37.35
       0   37.35       0   36.15     2.5   36.15     2.5   37.35     2.7   37.35
     2.7   37.25       4   37.25       6   36.55     6.8   36.05    16.8   36.05
#Mann= 3 , 0 , 0
   -12.6    .035       0       0    .035       0     2.5    .035       0
Bank Sta=0,2.5
XS Rating Curve= 0
Exp/Cntr=.3,.1

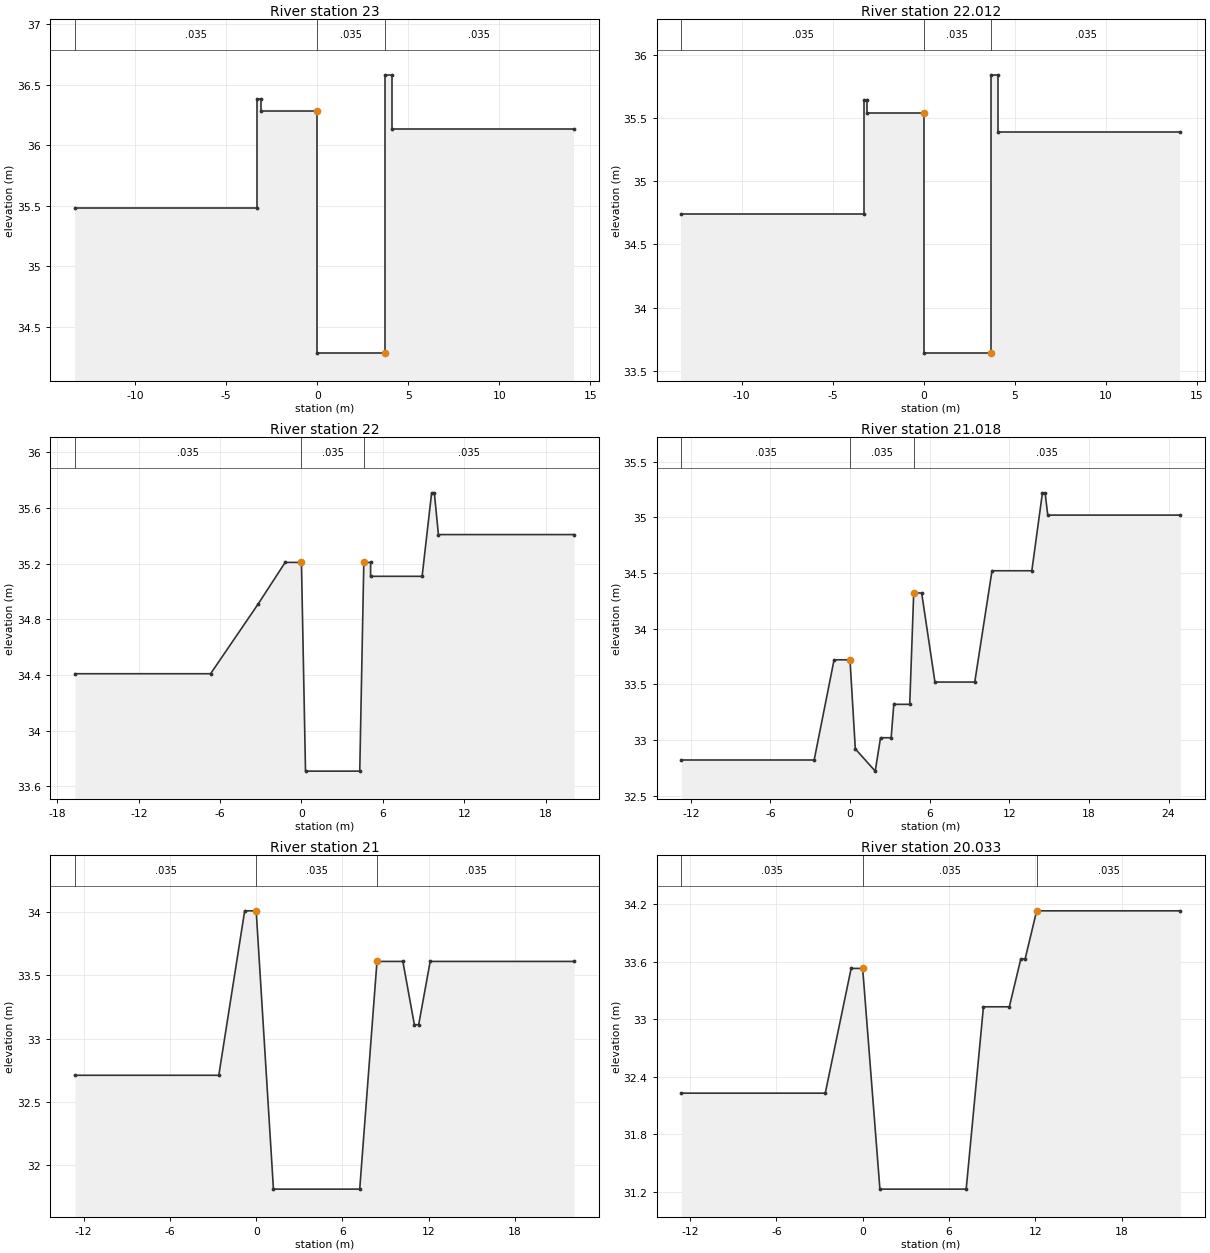
Type RM Length L Ch R = 1 ,23      ,38,38,38
#Sta/Elev= 12
   -13.3   35.48    -3.3   35.48    -3.3   36.38    -3.1   36.38    -3.1   36.28
       0   36.28       0   34.28     3.7   34.28     3.7   36.58     4.1   36.58
     4.1   36.13    14.1   36.13
#Mann= 3 , 0 , 0
   -13.3    .035       0       0    .035       0     3.7    .035       0
Bank Sta=0,3.7
XS Rating Curve= 0
Exp/Cntr=.3,.1

Type RM Length L Ch R = 1 ,22.012  ,12,12,12
#Sta/Elev= 12
   -13.3   34.74    -3.3   34.74    -3.3   35.64    -3.1   35.64    -3.1   35.54
       0   35.54       0   33.64     3.7   33.64     3.7   35.84     4.1   35.84
     4.1   35.39    14.1   35.39
#Mann= 3 , 0 , 0
   -13.3    .035       0       0    .035       0     3.7    .035       0
Bank Sta=0,3.7
XS Rating Curve= 0
Exp/Cntr=.3,.1

Type RM Length L Ch R = 1 ,22      ,32,32,32
#Sta/Elev= 15
   -16.7   34.41    -6.7   34.41    -3.2   34.91    -1.2   35.21       0   35.21
      .3   33.71     4.3   33.71     4.6   35.21     5.1   35.21     5.1   35.11
     8.9   35.11     9.6   35.71     9.8   35.71    10.1   35.41    20.1   35.41
#Mann= 3 , 0 , 0
   -16.7    .035       0       0    .035       0     4.6    .035       0
Bank Sta=0,4.6
XS Rating Curve= 0
Exp/Cntr=.3,.1

Type RM Length L Ch R = 1 ,21.018  ,18,18,18
#Sta/Elev= 20
   -12.7   32.82    -2.7   32.82    -1.2   33.72       0   33.72      .4   32.92
     1.9   32.72     2.3   33.02     3.1   33.02     3.3   33.32     4.5   33.32
     4.8   34.32     5.4   34.32     6.4   33.52     9.4   33.52    10.7   34.52
    13.7   34.52    14.5   35.22    14.7   35.22    14.9   35.02    24.9   35.02
#Mann= 3 , 0 , 0
   -12.7    .035       0       0    .035       0     4.8    .035       0
Bank Sta=0,4.8
XS Rating Curve= 0
Exp/Cntr=.3,.1

Type RM Length L Ch R = 1 ,21      ,17,17,17
#Sta/Elev= 12
   -12.6   32.71    -2.6   32.71     -.8   34.01       0   34.01     1.2   31.81
     7.2   31.81     8.4   33.61    10.2   33.61      11   33.11    11.3   33.11
    12.1   33.61    22.1   33.61
#Mann= 3 , 0 , 0
   -12.6    .035       0       0    .035       0     8.4    .035       0
Bank Sta=0,8.4
XS Rating Curve= 0
Exp/Cntr=.3,.1

Type RM Length L Ch R = 1 ,20.033  ,33,33,33
#Sta/Elev= 12
   -12.6   32.23    -2.6   32.23     -.8   33.53       0   33.53     1.2   31.23
     7.2   31.23     8.4   33.13    10.2   33.13      11   33.63    11.3   33.63
    12.1   34.13    22.1   34.13
#Mann= 3 , 0 , 0
   -12.6    .035       0       0    .035       0    12.1    .035       0
Bank Sta=0,12.1
XS Rating Curve= 0
Exp/Cntr=.3,.1

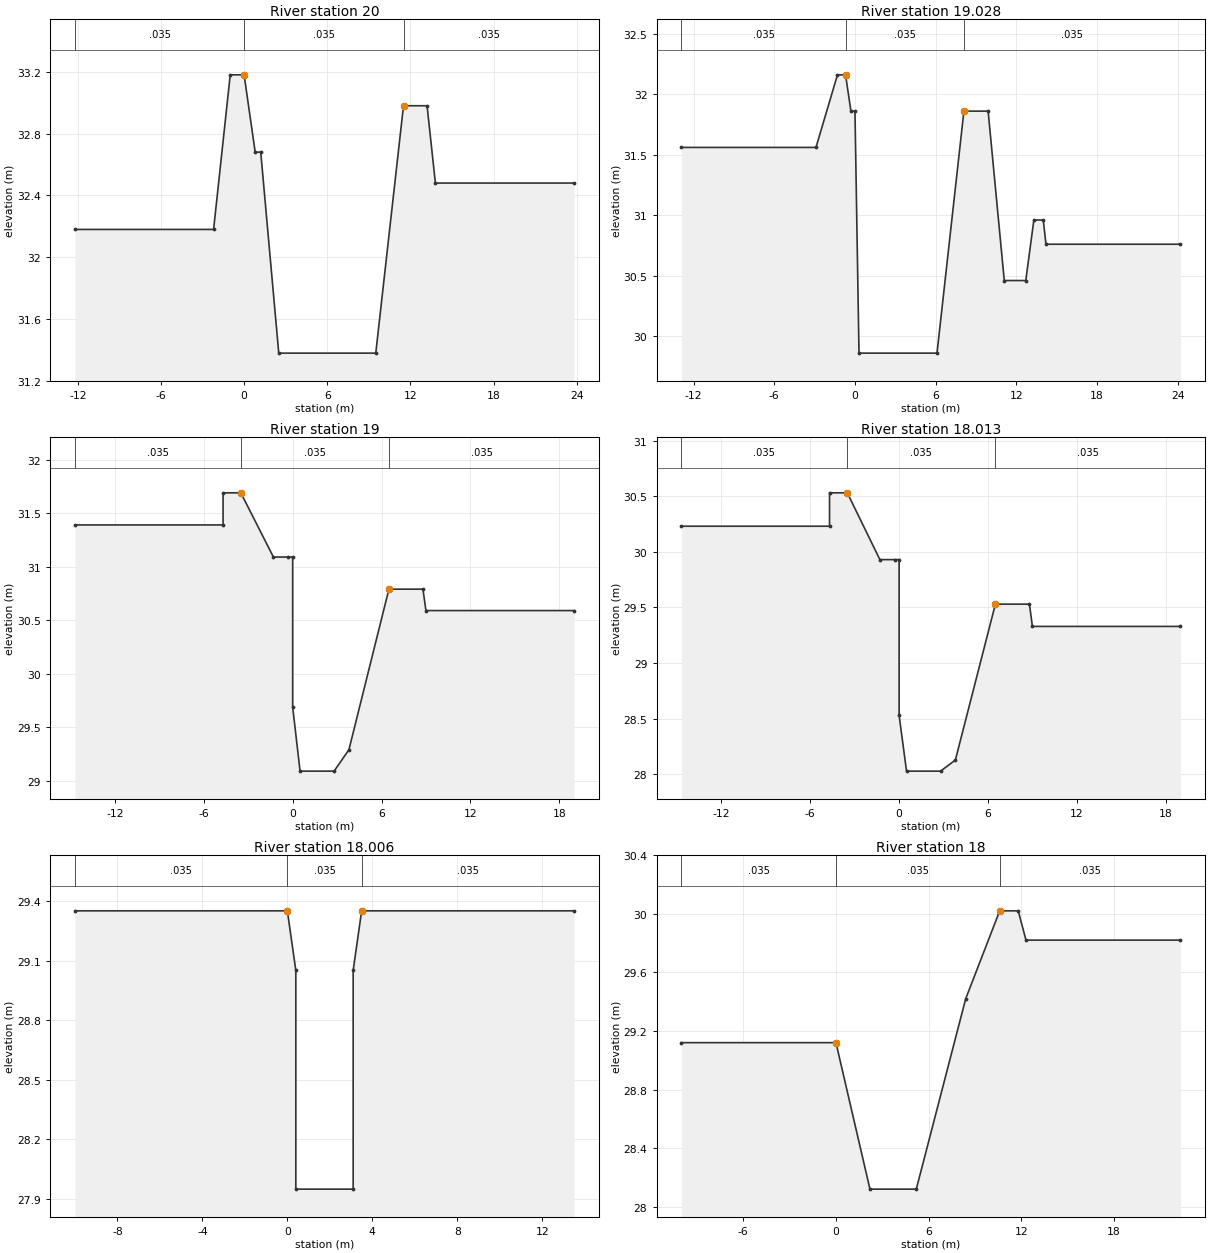
Type RM Length L Ch R = 1 ,20      ,22,22,22
#Sta/Elev= 12
   -12.2   32.18    -2.2   32.18      -1   33.18       0   33.18      .8   32.68
     1.2   32.68     2.5   31.38     9.5   31.38    11.5   32.98    13.2   32.98
    13.8   32.48    23.8   32.48
#Mann= 3 , 0 , 0
   -12.2    .035       0       0    .035       0    11.5    .035       0
Bank Sta=0,11.5
XS Rating Curve= 0
Exp/Cntr=.3,.1

Type RM Length L Ch R = 1 ,19.028  ,28,28,28
#Sta/Elev= 16
   -12.9   31.56    -2.9   31.56    -1.3   32.16     -.7   32.16     -.3   31.86
       0   31.86      .3   29.86     6.1   29.86     8.1   31.86     9.9   31.86
    11.1   30.46    12.7   30.46    13.3   30.96      14   30.96    14.2   30.76
    24.2   30.76
#Mann= 3 , 0 , 0
   -12.9    .035       0     -.7    .035       0     8.1    .035       0
Bank Sta=-.7,8.1
XS Rating Curve= 0
Exp/Cntr=.3,.1

Type RM Length L Ch R = 1 ,19      ,37,37,37
#Sta/Elev= 15
   -14.7   31.39    -4.7   31.39    -4.7   31.69    -3.5   31.69    -1.3   31.09
     -.3   31.09       0   31.09       0   29.69      .5   29.09     2.8   29.09
     3.8   29.29     6.5   30.79     8.8   30.79       9   30.59      19   30.59
#Mann= 3 , 0 , 0
   -14.7    .035       0    -3.5    .035       0     6.5    .035       0
Bank Sta=-3.5,6.5
XS Rating Curve= 0
Exp/Cntr=.3,.1

Type RM Length L Ch R = 1 ,18.013  ,7,7,7
#Sta/Elev= 15
   -14.7   30.23    -4.7   30.23    -4.7   30.53    -3.5   30.53    -1.3   29.93
     -.3   29.93       0   29.93       0   28.53      .5   28.03     2.8   28.03
     3.8   28.13     6.5   29.53     8.8   29.53       9   29.33      19   29.33
#Mann= 3 , 0 , 0
   -14.7    .035       0    -3.5    .035       0     6.5    .035       0
Bank Sta=-3.5,6.5
XS Rating Curve= 0
Exp/Cntr=.3,.1

Type RM Length L Ch R = 1 ,18.006  ,6,6,6
#Sta/Elev= 8
     -10   29.35       0   29.35      .4   29.05      .4   27.95     3.1   27.95
     3.1   29.05     3.5   29.35    13.5   29.35
#Mann= 3 , 0 , 0
     -10    .035       0       0    .035       0     3.5    .035       0
Bank Sta=0,3.5
XS Rating Curve= 0
Exp/Cntr=.3,.1

Type RM Length L Ch R = 1 ,18      ,23,23,23
#Sta/Elev= 9
     -10   29.12       0   29.12     2.2   28.12     5.2   28.12     8.4   29.42
    10.6   30.02    11.8   30.02    12.3   29.82    22.3   29.82
#Mann= 3 , 0 , 0
     -10    .035       0       0    .035       0    10.6    .035       0
Bank Sta=0,10.6
XS Rating Curve= 0
Exp/Cntr=.3,.1

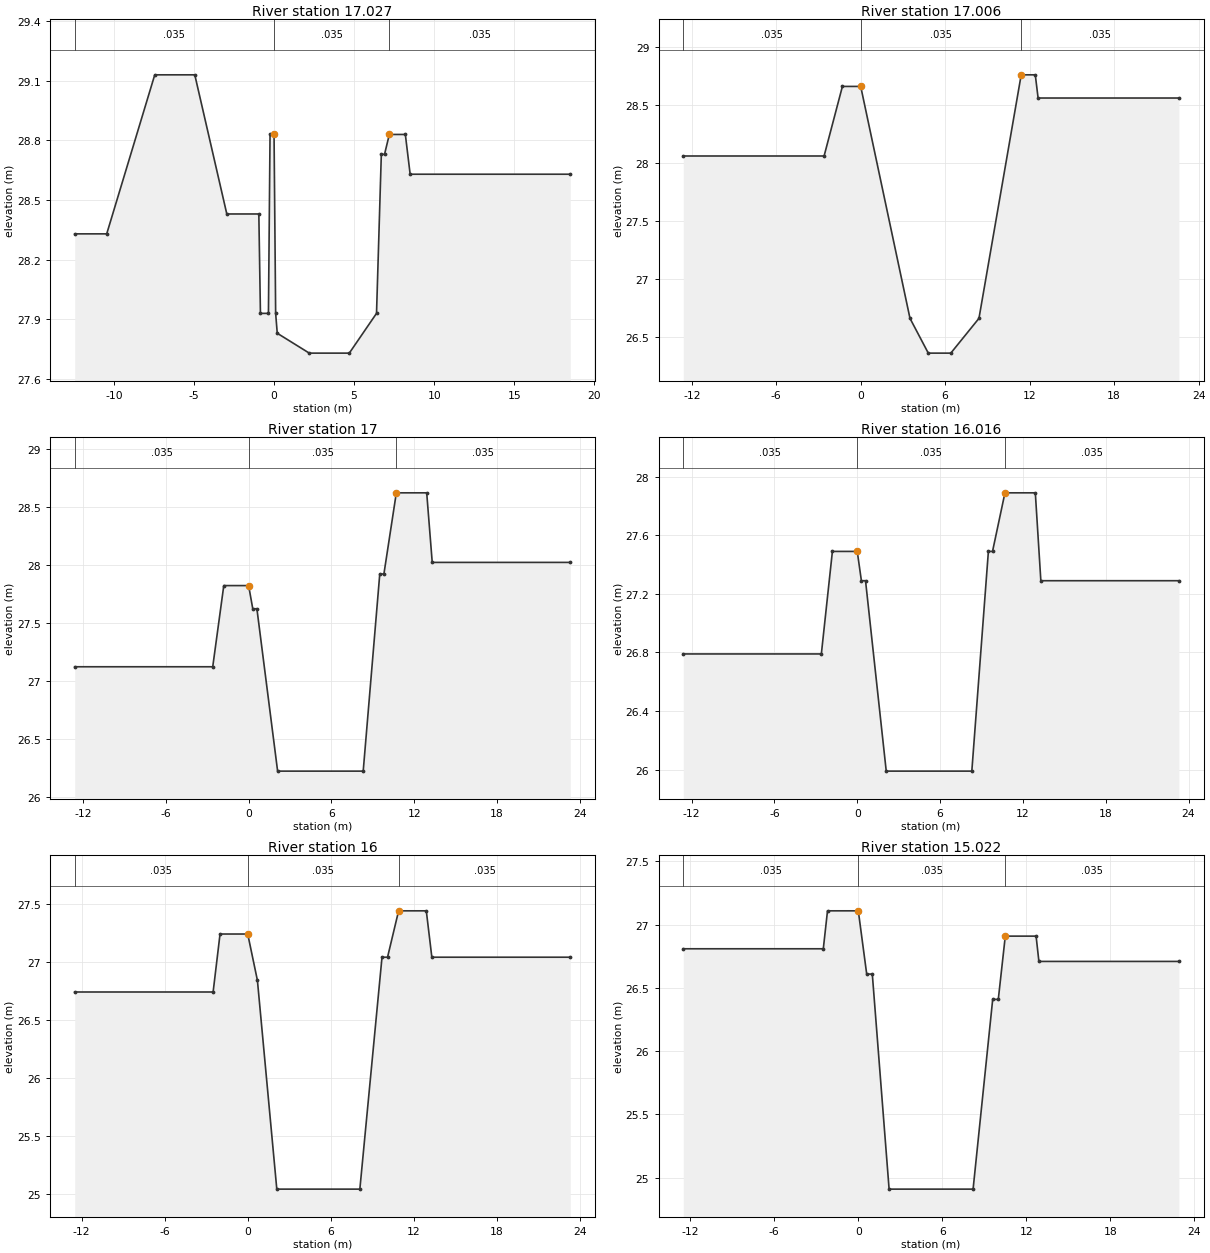
Type RM Length L Ch R = 1 ,17.027  ,21,21,21
#Sta/Elev= 21
  -12.45   28.33  -10.45   28.33   -7.45   29.13   -4.95   29.13   -2.95   28.43
    -.95   28.43    -.85   27.93    -.35   27.93    -.25   28.83       0   28.83
      .1   27.93      .2   27.83     2.2   27.73     4.7   27.73     6.4   27.93
     6.7   28.73     6.9   28.73     7.2   28.83     8.2   28.83     8.5   28.63
    18.5   28.63
#Mann= 3 , 0 , 0
  -12.45    .035       0       0    .035       0     7.2    .035       0
Bank Sta=0,7.2
XS Rating Curve= 0
Exp/Cntr=.3,.1

Type RM Length L Ch R = 1 ,17.006  ,6,6,6
#Sta/Elev= 12
   -12.6   28.06    -2.6   28.06    -1.3   28.66       0   28.66     3.5   26.66
     4.8   26.36     6.4   26.36     8.4   26.66    11.4   28.76    12.4   28.76
    12.6   28.56    22.6   28.56
#Mann= 3 , 0 , 0
   -12.6    .035       0       0    .035       0    11.4    .035       0
Bank Sta=0,11.4
XS Rating Curve= 0
Exp/Cntr=.3,.1

Type RM Length L Ch R = 1 ,17      ,34,34,34
#Sta/Elev= 14
   -12.6   27.12    -2.6   27.12    -1.8   27.82       0   27.82      .3   27.62
      .6   27.62     2.1   26.22     8.3   26.22     9.5   27.92     9.8   27.92
    10.7   28.62    12.9   28.62    13.3   28.02    23.3   28.02
#Mann= 3 , 0 , 0
   -12.6    .035       0       0    .035       0    10.7    .035       0
Bank Sta=0,10.7
XS Rating Curve= 0
Exp/Cntr=.3,.1

Type RM Length L Ch R = 1 ,16.016  ,16,16,16
#Sta/Elev= 14
   -12.6   26.79    -2.6   26.79    -1.8   27.49       0   27.49      .3   27.29
      .6   27.29     2.1   25.99     8.3   25.99     9.5   27.49     9.8   27.49
    10.7   27.89    12.9   27.89    13.3   27.29    23.3   27.29
#Mann= 3 , 0 , 0
   -12.6    .035       0       0    .035       0    10.7    .035       0
Bank Sta=0,10.7
XS Rating Curve= 0
Exp/Cntr=.3,.1

Type RM Length L Ch R = 1 ,16      ,28,28,28
#Sta/Elev= 13
   -12.5   26.74    -2.5   26.74      -2   27.24       0   27.24      .7   26.84
     2.1   25.04     8.1   25.04     9.7   27.04    10.1   27.04    10.9   27.44
    12.9   27.44    13.3   27.04    23.3   27.04
#Mann= 3 , 0 , 0
   -12.5    .035       0       0    .035       0    10.9    .035       0
Bank Sta=0,10.9
XS Rating Curve= 0
Exp/Cntr=.3,.1

Type RM Length L Ch R = 1 ,15.022  ,22,22,22
#Sta/Elev= 14
   -12.5   26.81    -2.5   26.81    -2.2   27.11       0   27.11      .6   26.61
       1   26.61     2.2   24.91     8.2   24.91     9.6   26.41      10   26.41
    10.5   26.91    12.7   26.91    12.9   26.71    22.9   26.71
#Mann= 3 , 0 , 0
   -12.5    .035       0       0    .035       0    10.5    .035       0
Bank Sta=0,10.5
XS Rating Curve= 0
Exp/Cntr=.3,.1

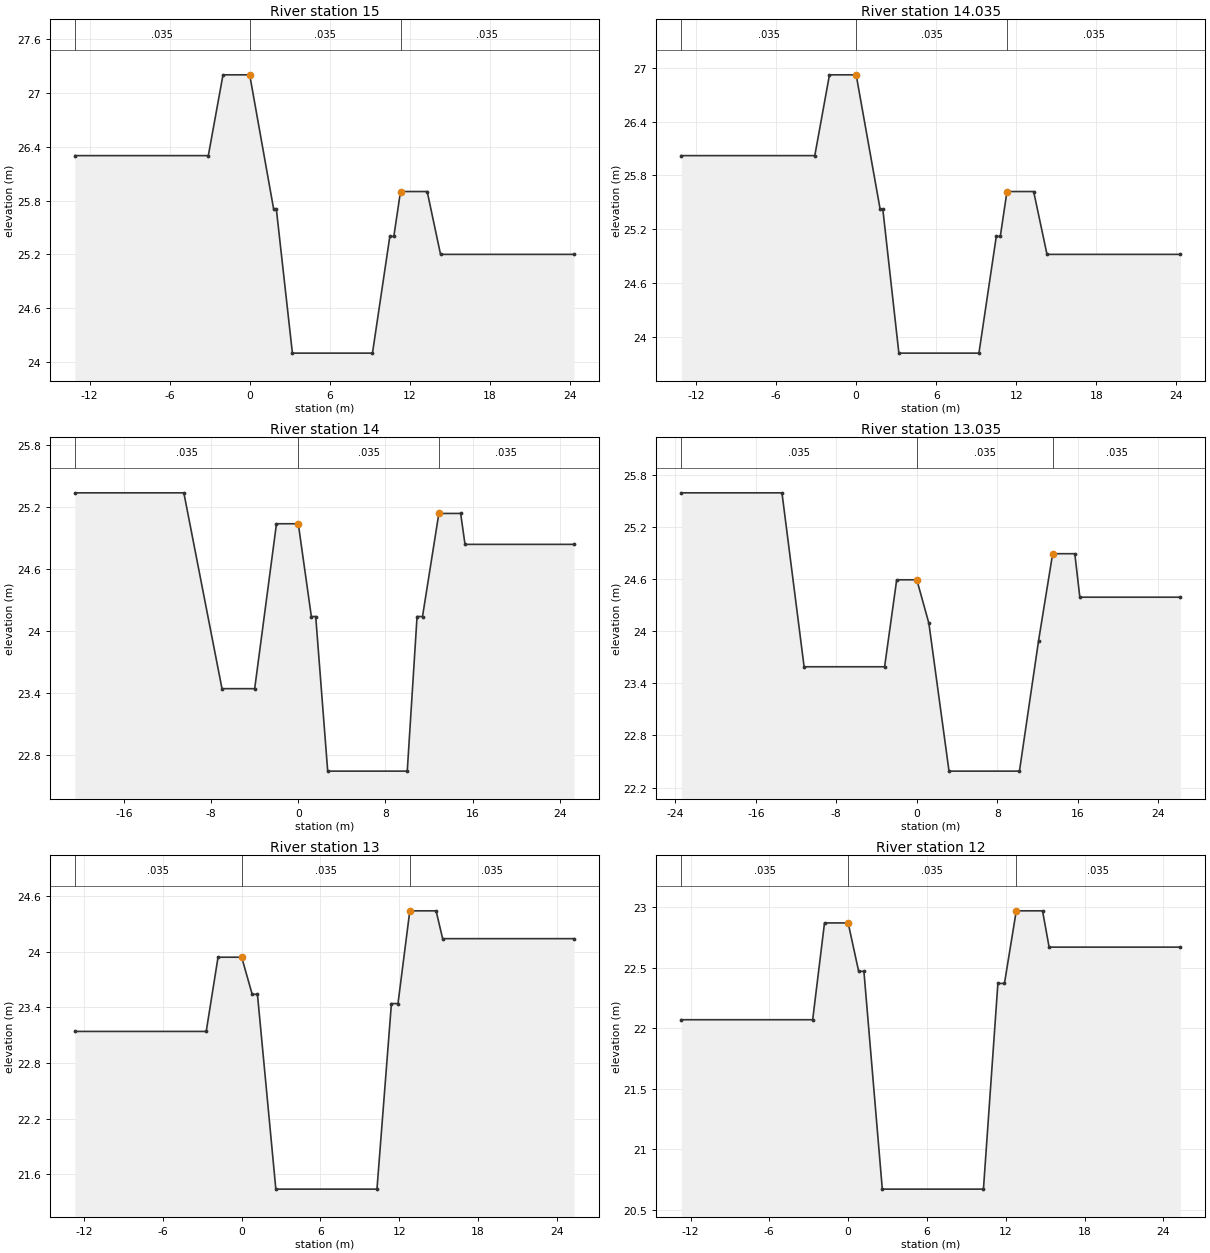
Type RM Length L Ch R = 1 ,15      ,15,15,15
#Sta/Elev= 14
   -13.1    26.3    -3.1    26.3      -2    27.2       0    27.2     1.8    25.7
       2    25.7     3.2    24.1     9.2    24.1    10.5    25.4    10.8    25.4
    11.3    25.9    13.3    25.9    14.3    25.2    24.3    25.2
#Mann= 3 , 0 , 0
   -13.1    .035       0       0    .035       0    11.3    .035       0
Bank Sta=0,11.3
XS Rating Curve= 0
Exp/Cntr=.3,.1

Type RM Length L Ch R = 1 ,14.035  ,35,35,35
#Sta/Elev= 14
   -13.1   26.02    -3.1   26.02      -2   26.92       0   26.92     1.8   25.42
       2   25.42     3.2   23.82     9.2   23.82    10.5   25.12    10.8   25.12
    11.3   25.62    13.3   25.62    14.3   24.92    24.3   24.92
#Mann= 3 , 0 , 0
   -13.1    .035       0       0    .035       0    11.3    .035       0
Bank Sta=0,11.3
XS Rating Curve= 0
Exp/Cntr=.3,.1

Type RM Length L Ch R = 1 ,14      ,15,15,15
#Sta/Elev= 16
   -20.5   25.34   -10.5   25.34      -7   23.44      -4   23.44      -2   25.04
       0   25.04     1.2   24.14     1.6   24.14     2.7   22.64      10   22.64
    10.9   24.14    11.4   24.14    12.9   25.14    14.9   25.14    15.3   24.84
    25.3   24.84
#Mann= 3 , 0 , 0
   -20.5    .035       0       0    .035       0    12.9    .035       0
Bank Sta=0,12.9
XS Rating Curve= 0
Exp/Cntr=.3,.1

Type RM Length L Ch R = 1 ,13.035  ,35,35,35
#Sta/Elev= 14
   -23.4   25.59   -13.4   25.59   -11.2   23.59    -3.2   23.59      -2   24.59
       0   24.59     1.2   24.09     3.2   22.39    10.2   22.39    12.1   23.89
    13.5   24.89    15.7   24.89    16.2   24.39    26.2   24.39
#Mann= 3 , 0 , 0
   -23.4    .035       0       0    .035       0    13.5    .035       0
Bank Sta=0,13.5
XS Rating Curve= 0
Exp/Cntr=.3,.1

Type RM Length L Ch R = 1 ,13      ,50,50,50
#Sta/Elev= 14
   -12.7   23.14    -2.7   23.14    -1.8   23.94       0   23.94      .8   23.54
     1.2   23.54     2.6   21.44    10.3   21.44    11.4   23.44    11.9   23.44
    12.8   24.44    14.8   24.44    15.3   24.14    25.3   24.14
#Mann= 3 , 0 , 0
   -12.7    .035       0       0    .035       0    12.8    .035       0
Bank Sta=0,12.8
XS Rating Curve= 0
Exp/Cntr=.3,.1

Type RM Length L Ch R = 1 ,12      ,13,13,13
#Sta/Elev= 14
   -12.7   22.07    -2.7   22.07    -1.8   22.87       0   22.87      .8   22.47
     1.2   22.47     2.6   20.67    10.3   20.67    11.4   22.37    11.9   22.37
    12.8   22.97    14.8   22.97    15.3   22.67    25.3   22.67
#Mann= 3 , 0 , 0
   -12.7    .035       0       0    .035       0    12.8    .035       0
Bank Sta=0,12.8
XS Rating Curve= 0
Exp/Cntr=.3,.1

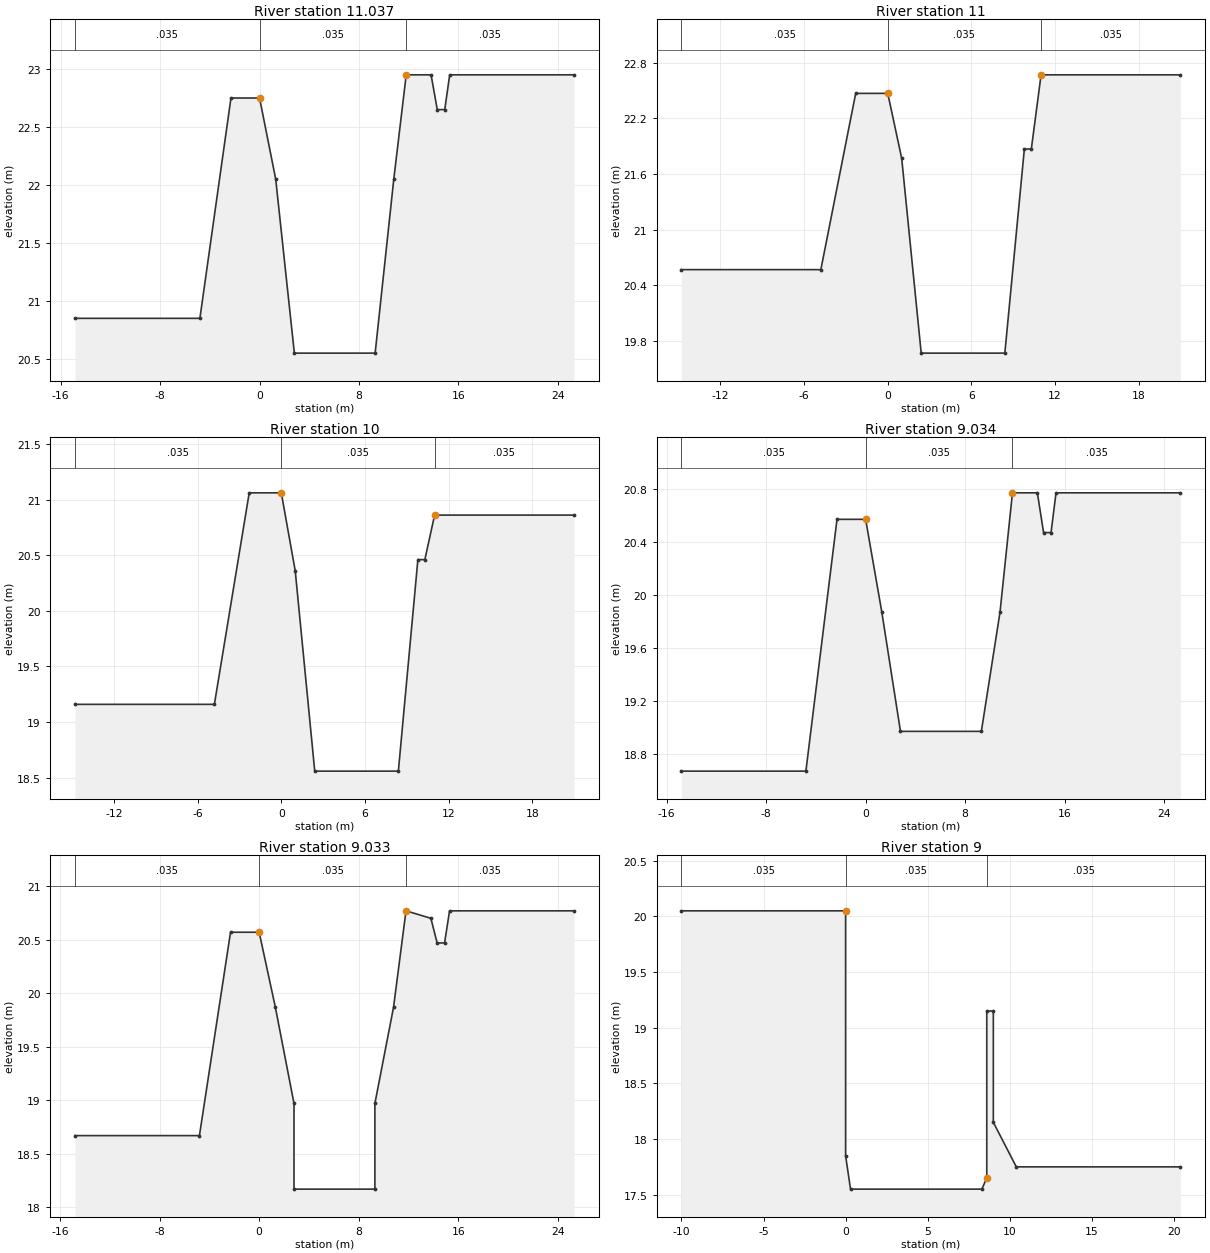
Type RM Length L Ch R = 1 ,11.037  ,37,37,37
#Sta/Elev= 14
  -14.85   20.85    -4.8   20.85    -2.3   22.75       0   22.75     1.3   22.05
     2.8   20.55     9.3   20.55    10.8   22.05    11.8   22.95    13.8   22.95
    14.3   22.65    14.9   22.65    15.3   22.95    25.3   22.95
#Mann= 3 , 0 , 0
  -14.85    .035       0       0    .035       0    11.8    .035       0
Bank Sta=0,11.8
XS Rating Curve= 0
Exp/Cntr=.3,.1

Type RM Length L Ch R = 1 ,11      ,50,50,50
#Sta/Elev= 11
   -14.8   20.57    -4.8   20.57    -2.3   22.47       0   22.47       1   21.77
     2.4   19.67     8.4   19.67     9.8   21.87    10.3   21.87      11   22.67
      21   22.67
#Mann= 3 , 0 , 0
   -14.8    .035       0       0    .035       0      11    .035       0
Bank Sta=0,11
XS Rating Curve= 0
Exp/Cntr=.3,.1

Type RM Length L Ch R = 1 ,10      ,16,16,16
#Sta/Elev= 11
   -14.8   19.16    -4.8   19.16    -2.3   21.06       0   21.06       1   20.36
     2.4   18.56     8.4   18.56     9.8   20.46    10.3   20.46      11   20.86
      21   20.86
#Mann= 3 , 0 , 0
   -14.8    .035       0       0    .035       0      11    .035       0
Bank Sta=0,11
XS Rating Curve= 0
Exp/Cntr=.3,.1

Type RM Length L Ch R = 1 ,9.034   ,1,1,1
#Sta/Elev= 14
   -14.8   18.67    -4.8   18.67    -2.3   20.57       0   20.57     1.3   19.87
     2.8   18.97     9.3   18.97    10.8   19.87    11.8   20.77    13.8   20.77
    14.3   20.47    14.9   20.47    15.3   20.77    25.3   20.77
#Mann= 3 , 0 , 0
   -14.8    .035       0       0    .035       0    11.8    .035       0
Bank Sta=0,11.8
XS Rating Curve= 0
Exp/Cntr=.3,.1

Type RM Length L Ch R = 1 ,9.033   ,33,33,33
#Sta/Elev= 16
   -14.8   18.67    -4.8   18.67    -2.3   20.57       0   20.57     1.3   19.87
     2.8   18.97     2.8   18.17     9.3   18.17     9.3   18.97    10.8   19.87
    11.8   20.77    13.8    20.7    14.3   20.47    14.9   20.47    15.3   20.77
    25.3   20.77
#Mann= 3 , 0 , 0
   -14.8    .035       0       0    .035       0    11.8    .035       0
Bank Sta=0,11.8
XS Rating Curve= 0
Exp/Cntr=.3,.1

Type RM Length L Ch R = 1 ,9       ,25,25,25
#Sta/Elev= 11
     -10   20.05       0   20.05       0   17.85      .3   17.55     8.3   17.55
     8.6   17.65     8.6   19.15       9   19.15       9   18.15    10.4   17.75
    20.4   17.75
#Mann= 3 , 0 , 0
     -10    .035       0       0    .035       0     8.6    .035       0
Bank Sta=0,8.6
XS Rating Curve= 0
Exp/Cntr=.3,.1