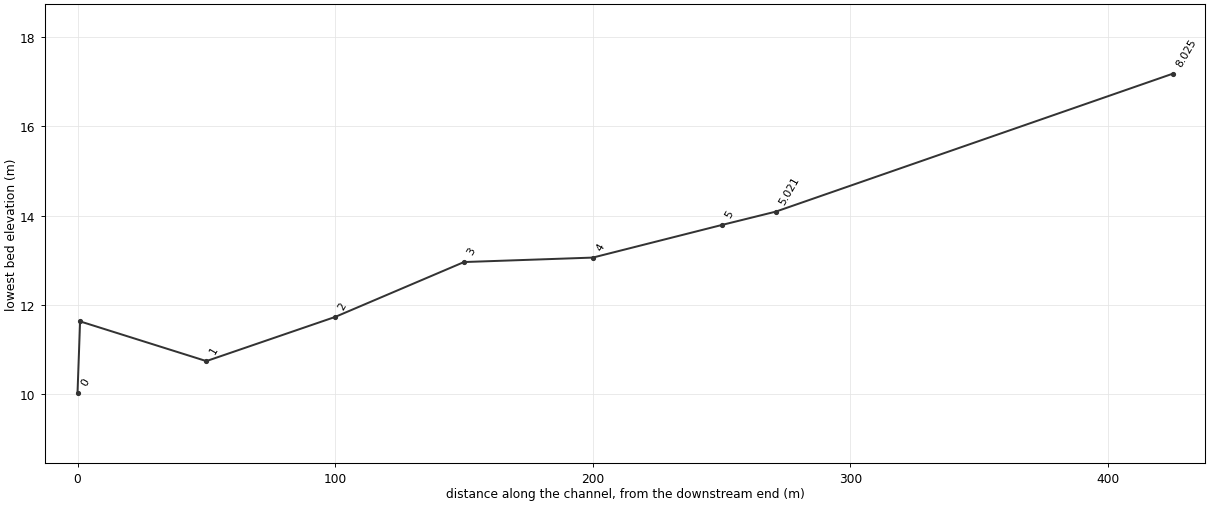
HEC-RAS study MYUNGAM.prj: MYUNGAM

--- MYUNGAM.g01 (geometry) --- (continued)

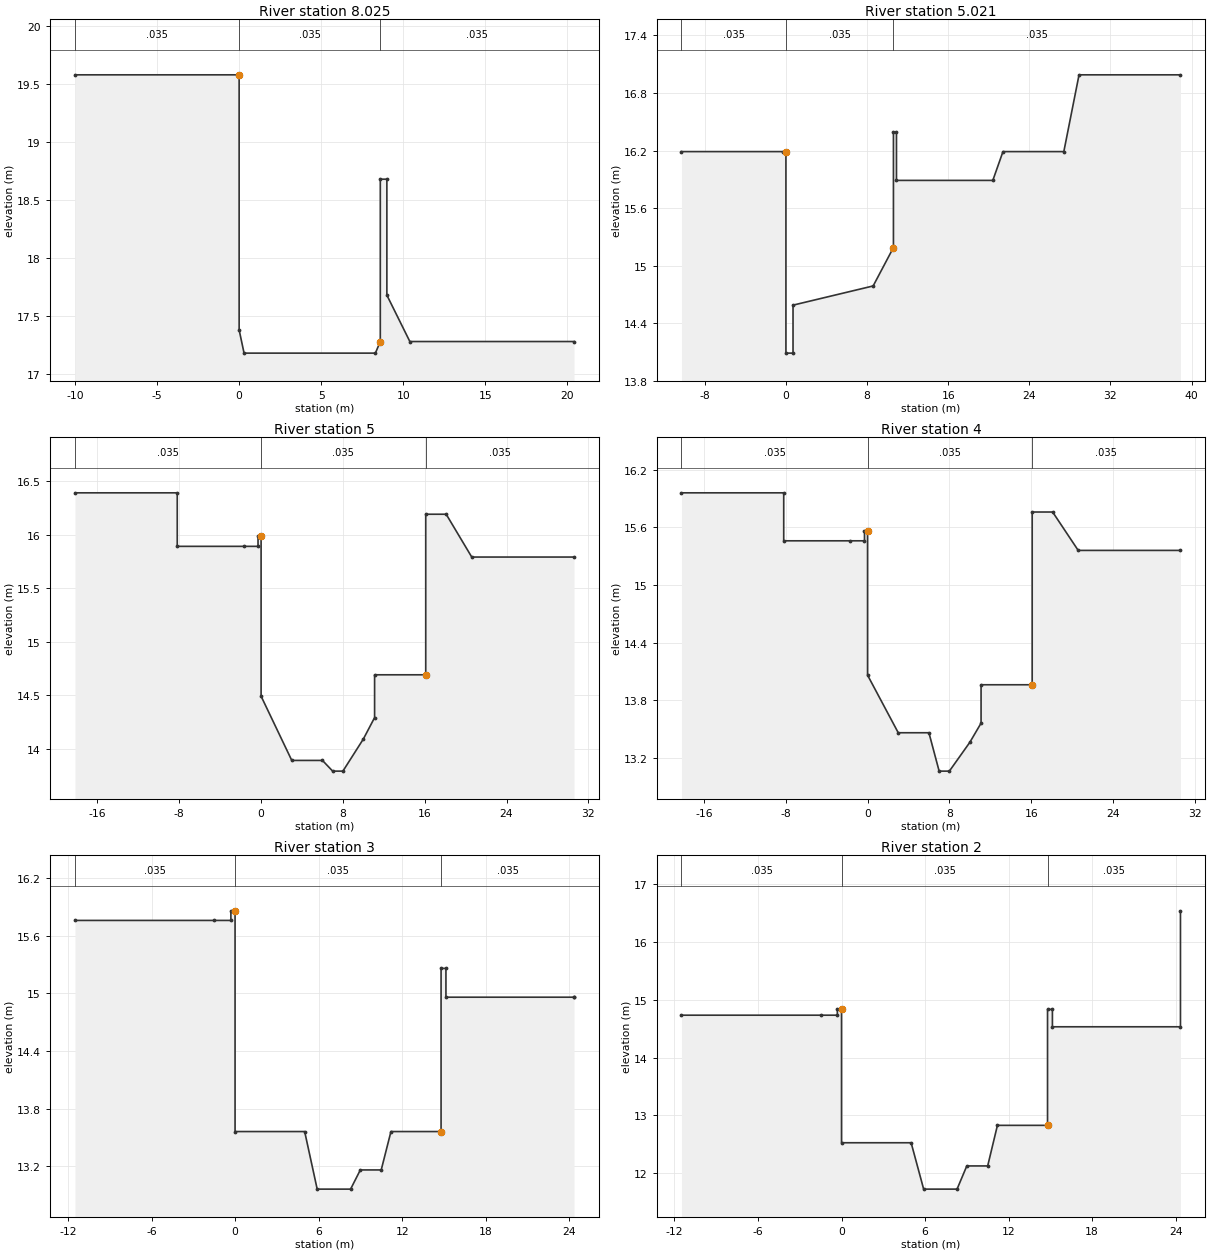
Type RM Length L Ch R = 1 ,8.025   ,154,154,154
#Sta/Elev= 11
     -10   19.58       0   19.58       0   17.38      .3   17.18     8.3   17.18
     8.6   17.28     8.6   18.68       9   18.68       9   17.68    10.4   17.28
    20.4   17.28
#Mann= 3 , 0 , 0
     -10    .035       0       0    .035       0     8.6    .035       0
Bank Sta=0,8.6
XS Rating Curve= 0
Exp/Cntr=.3,.1

Type RM Length L Ch R = 1 ,5.021   ,21,21,21
#Sta/Elev= 16
   -10.3   16.19     -.3   16.19       0   16.19       0   14.09      .7   14.09
      .7   14.59     8.6   14.79    10.6   15.19    10.6   16.39    10.9   16.39
    10.9   15.89    20.4   15.89    21.4   16.19    27.4   16.19    28.9   16.99
    38.9   16.99
#Mann= 3 , 0 , 0
   -10.3    .035       0       0    .035       0    10.6    .035       0
Bank Sta=0,10.6
XS Rating Curve= 0
Exp/Cntr=.3,.1

Type RM Length L Ch R = 1 ,5       ,50,50,50
#Sta/Elev= 20
   -18.2   16.39    -8.2   16.39    -8.2   15.89    -1.7   15.89     -.3   15.89
     -.3   15.99       0   15.99       0   14.49       3   13.89       6   13.89
       7   13.79       8   13.79      10   14.09    11.1   14.29    11.1   14.69
    16.1   14.69    16.1   16.19    18.1   16.19    20.6   15.79    30.6   15.79
#Mann= 3 , 0 , 0
   -18.2    .035       0       0    .035       0    16.1    .035       0
Bank Sta=0,16.1
XS Rating Curve= 0
Exp/Cntr=.3,.1

Type RM Length L Ch R = 1 ,4       ,50,50,50
#Sta/Elev= 20
   -18.2   15.96    -8.2   15.96    -8.2   15.46    -1.7   15.46     -.3   15.46
     -.3   15.56       0   15.56       0   14.06       3   13.46       6   13.46
       7   13.06       8   13.06      10   13.36    11.1   13.56    11.1   13.96
    16.1   13.96    16.1   15.76    18.1   15.76    20.6   15.36    30.6   15.36
#Mann= 3 , 0 , 0
   -18.2    .035       0       0    .035       0    16.1    .035       0
Bank Sta=0,16.1
XS Rating Curve= 0
Exp/Cntr=.3,.1

Type RM Length L Ch R = 1 ,3       ,50,50,50
#Sta/Elev= 18
   -11.5   15.76    -1.5   15.76     -.3   15.76     -.3   15.86       0   15.86
       0   13.56       5   13.56     5.9   12.96     8.3   12.96       9   13.16
    10.5   13.16    11.2   13.56    14.8   13.56    14.8   15.26   15.15   15.26
   15.15   14.96   24.35   14.96   24.35   14.96
#Mann= 3 , 0 , 0
   -11.5    .035       0       0    .035       0    14.8    .035       0
Bank Sta=0,14.8
XS Rating Curve= 0
Exp/Cntr=.3,.1

Type RM Length L Ch R = 1 ,2       ,50,50,50
#Sta/Elev= 18
   -11.5   14.73    -1.5   14.73     -.3   14.73     -.3   14.83       0   14.83
       0   12.53       5   12.53     5.9   11.73     8.3   11.73       9   12.13
    10.5   12.13    11.2   12.83    14.8   12.83    14.8   14.83   15.15   14.83
   15.15   14.53   24.35   14.53   24.35   16.53
#Mann= 3 , 0 , 0
   -11.5    .035       0       0    .035       0    14.8    .035       0
Bank Sta=0,14.8
XS Rating Curve= 0
Exp/Cntr=.3,.1

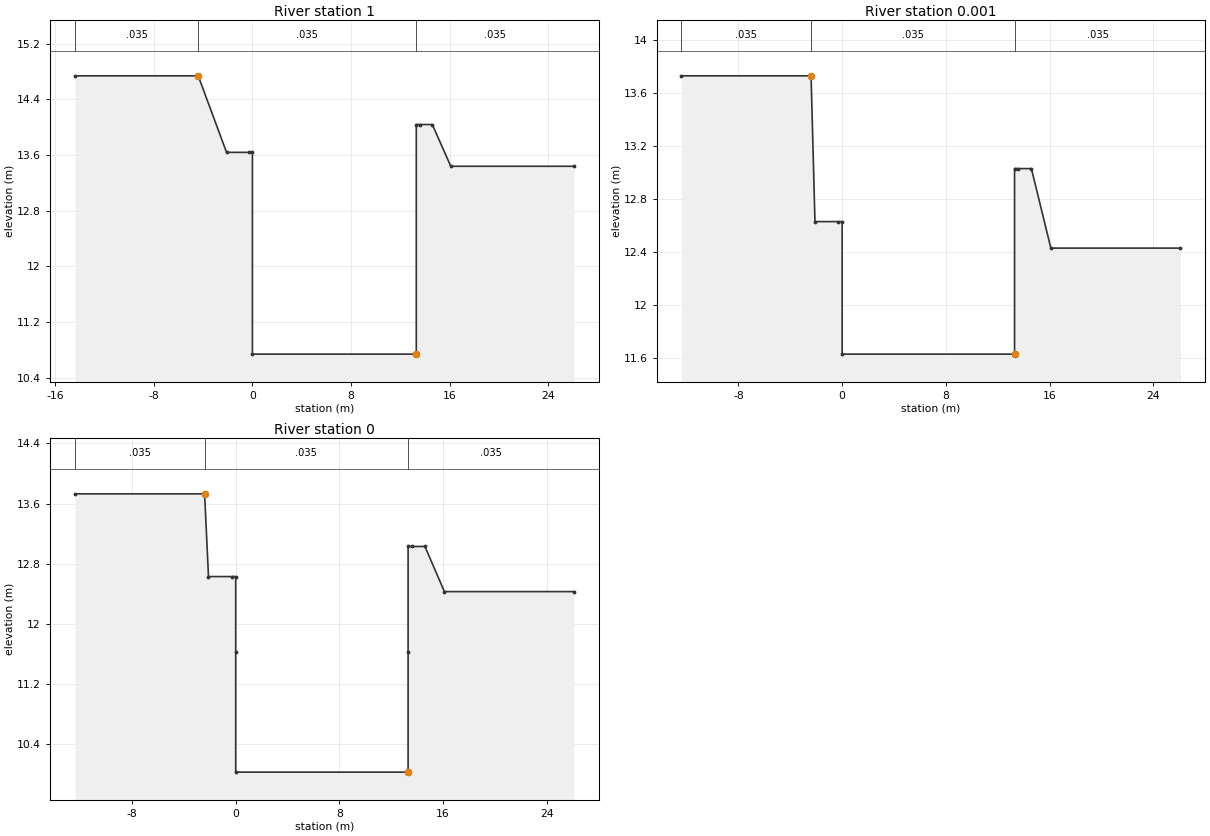
Type RM Length L Ch R = 1 ,1       ,49,49,49
#Sta/Elev= 12
   -14.4   14.74    -4.4   14.74    -2.1   13.64     -.3   13.64       0   13.64
       0   10.74    13.3   10.74    13.3   14.04    13.6   14.04    14.6   14.04
    16.1   13.44    26.1   13.44
#Mann= 3 , 0 , 0
   -14.4    .035       0    -4.4    .035       0    13.3    .035       0
Bank Sta=-4.4,13.3
XS Rating Curve= 0
Exp/Cntr=.3,.1

Type RM Length L Ch R = 1 ,0.001   ,1,1,1
#Sta/Elev= 12
   -12.4   13.73    -2.4   13.73    -2.1   12.63     -.3   12.63       0   12.63
       0   11.63    13.3   11.63    13.3   13.03    13.6   13.03    14.6   13.03
    16.1   12.43    26.1   12.43
#Mann= 3 , 0 , 0
   -12.4    .035       0    -2.4    .035       0    13.3    .035       0
Bank Sta=-2.4,13.3
XS Rating Curve= 0
Exp/Cntr=.3,.1

Type RM Length L Ch R = 1 ,0       ,0,0,0
#Sta/Elev= 14
   -12.4   13.73    -2.4   13.73    -2.1   12.63     -.3   12.63       0   12.63
       0   11.63       0   10.03    13.3   10.03    13.3   11.63    13.3   13.03
    13.6   13.03    14.6   13.03    16.1   12.43    26.1   12.43
#Mann= 3 , 0 , 0
   -12.4    .035       0    -2.4    .035       0    13.3    .035       0
Bank Sta=-2.4,13.3
XS Rating Curve= 0
Exp/Cntr=.3,.1

Chan Stop Cuts=-1