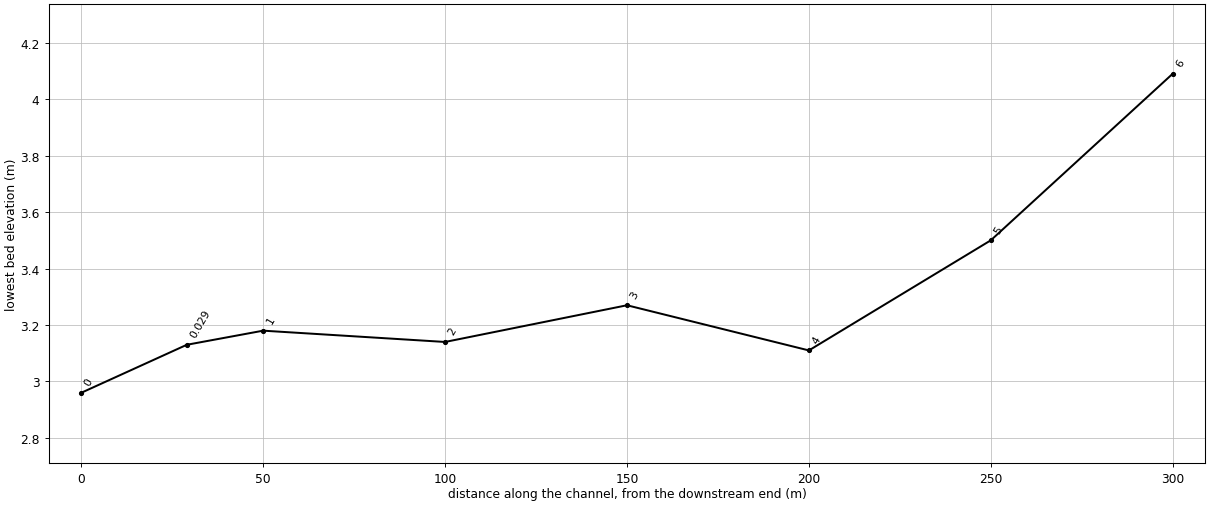
HEC-RAS study SAKOK.prj: SAKOK

--- SAKOK.g01 (geometry) --- (continued)

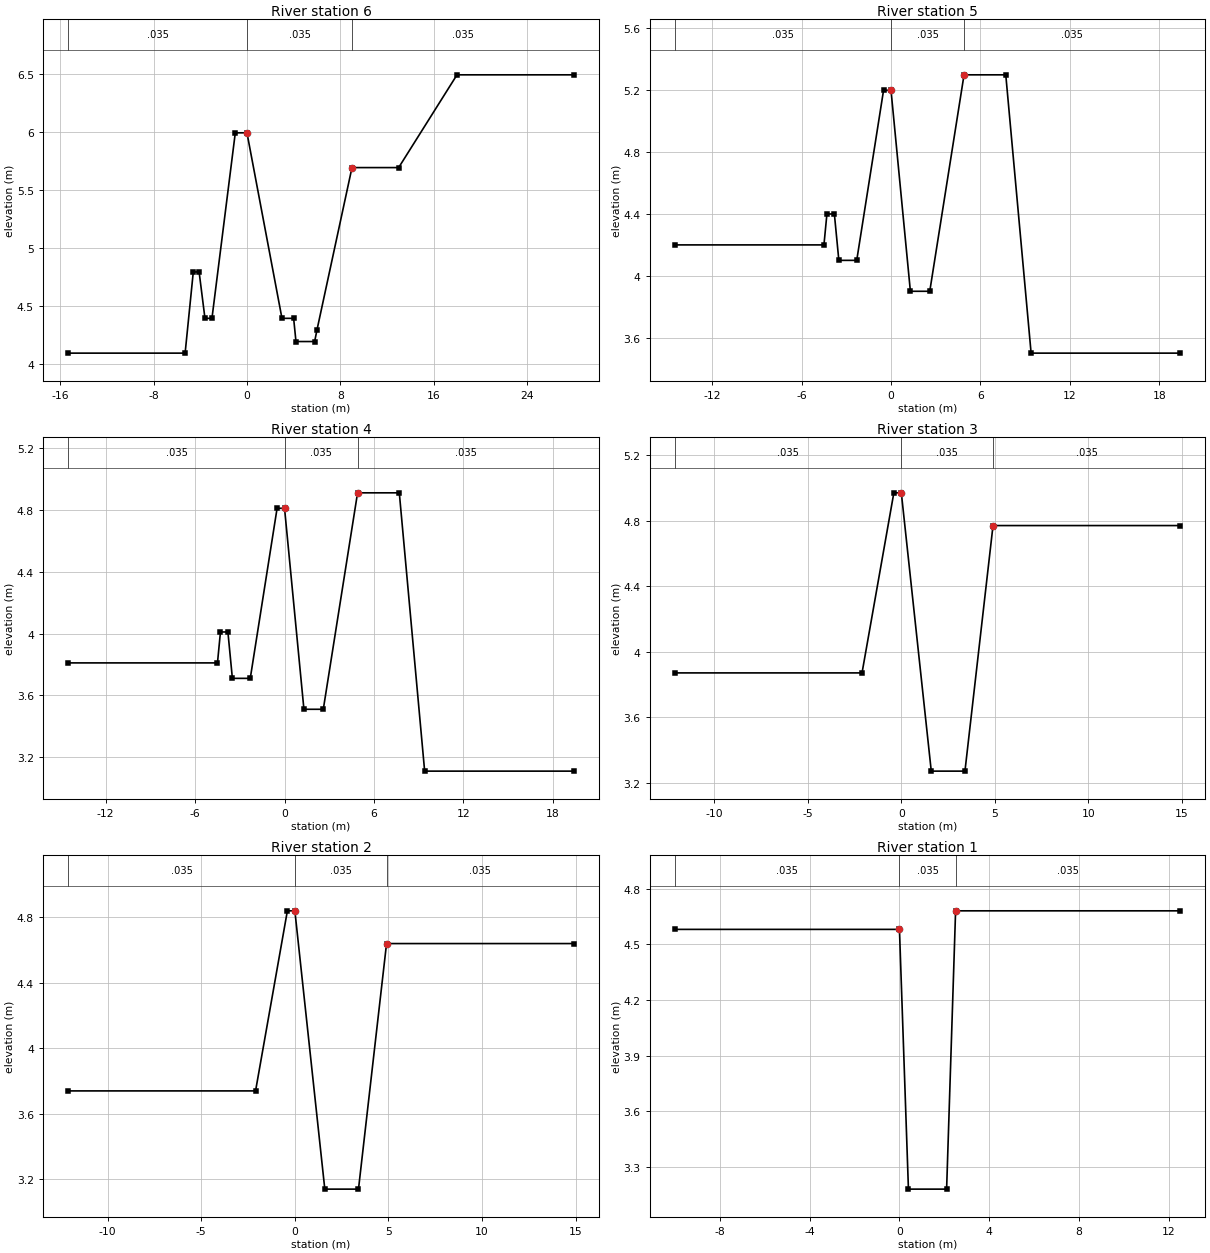
Type RM Length L Ch R = 1 ,6       ,50,50,50
#Sta/Elev= 17
   -15.3    4.09    -5.3    4.09    -4.6    4.79    -4.1    4.79    -3.6    4.39
      -3    4.39      -1    5.99       0    5.99       3    4.39       4    4.39
     4.2    4.19     5.8    4.19       6    4.29       9    5.69      13    5.69
      18    6.49      28    6.49
#Mann= 3 , 0 , 0
   -15.3    .035       0       0    .035       0       9    .035       0
Bank Sta=0,9
XS Rating Curve= 0
Exp/Cntr=.3,.1

Type RM Length L Ch R = 1 ,5       ,50,50,50
#Sta/Elev= 14
   -14.5     4.2    -4.5     4.2    -4.3     4.4    -3.8     4.4    -3.5     4.1
    -2.3     4.1     -.5     5.2       0     5.2     1.3     3.9     2.6     3.9
     4.9     5.3     7.7     5.3     9.4     3.5    19.4     3.5
#Mann= 3 , 0 , 0
   -14.5    .035       0       0    .035       0     4.9    .035       0
Bank Sta=0,4.9
XS Rating Curve= 0
Exp/Cntr=.3,.1

Type RM Length L Ch R = 1 ,4       ,50,50,50
#Sta/Elev= 14
   -14.5    3.81    -4.5    3.81    -4.3    4.01    -3.8    4.01    -3.5    3.71
    -2.3    3.71     -.5    4.81       0    4.81     1.3    3.51     2.6    3.51
     4.9    4.91     7.7    4.91     9.4    3.11    19.4    3.11
#Mann= 3 , 0 , 0
   -14.5    .035       0       0    .035       0     4.9    .035       0
Bank Sta=0,4.9
XS Rating Curve= 0
Exp/Cntr=.3,.1

Type RM Length L Ch R = 1 ,3       ,50,50,50
#Sta/Elev= 8
   -12.1    3.87    -2.1    3.87     -.4    4.97       0    4.97     1.6    3.27
     3.4    3.27     4.9    4.77    14.9    4.77
#Mann= 3 , 0 , 0
   -12.1    .035       0       0    .035       0     4.9    .035       0
Bank Sta=0,4.9
XS Rating Curve= 0
Exp/Cntr=.3,.1

Type RM Length L Ch R = 1 ,2       ,50,50,50
#Sta/Elev= 8
   -12.1    3.74    -2.1    3.74     -.4    4.84       0    4.84     1.6    3.14
     3.4    3.14     4.9    4.64    14.9    4.64
#Mann= 3 , 0 , 0
   -12.1    .035       0       0    .035       0     4.9    .035       0
Bank Sta=0,4.9
XS Rating Curve= 0
Exp/Cntr=.3,.1

Type RM Length L Ch R = 1 ,1       ,21,21,21
#Sta/Elev= 6
     -10    4.58       0    4.58      .4    3.18     2.1    3.18     2.5    4.68
    12.5    4.68
#Mann= 3 , 0 , 0
     -10    .035       0       0    .035       0     2.5    .035       0
Bank Sta=0,2.5
XS Rating Curve= 0
Exp/Cntr=.3,.1

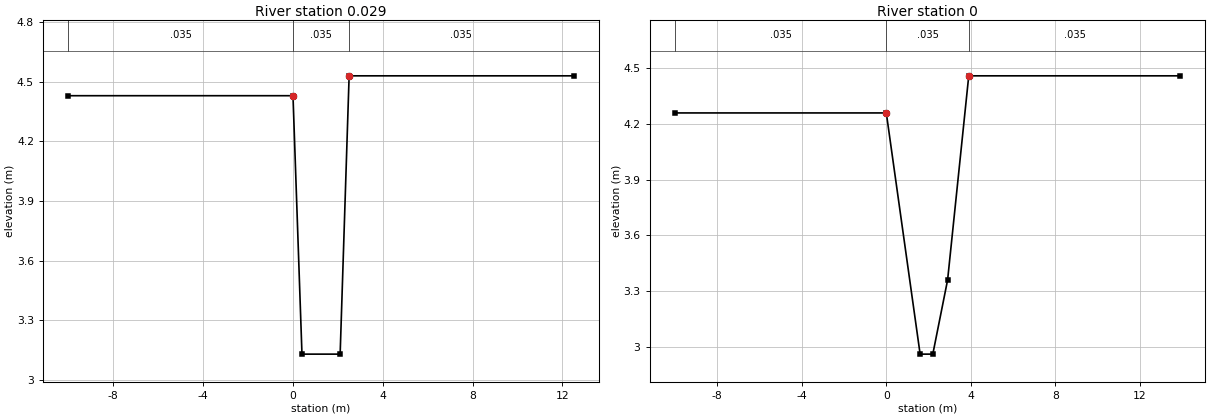
Type RM Length L Ch R = 1 ,0.029   ,29,29,29
#Sta/Elev= 6
     -10    4.43       0    4.43      .4    3.13     2.1    3.13     2.5    4.53
    12.5    4.53
#Mann= 3 , 0 , 0
     -10    .035       0       0    .035       0     2.5    .035       0
Bank Sta=0,2.5
XS Rating Curve= 0
Exp/Cntr=.3,.1

Type RM Length L Ch R = 1 ,0       ,0,0,0
#Sta/Elev= 7
     -10    4.26       0    4.26     1.6    2.96     2.2    2.96     2.9    3.36
     3.9    4.46    13.9    4.46
#Mann= 3 , 0 , 0
     -10    .035       0       0    .035       0     3.9    .035       0
Bank Sta=0,3.9
XS Rating Curve= 0
Exp/Cntr=.3,.1

Chan Stop Cuts=-1