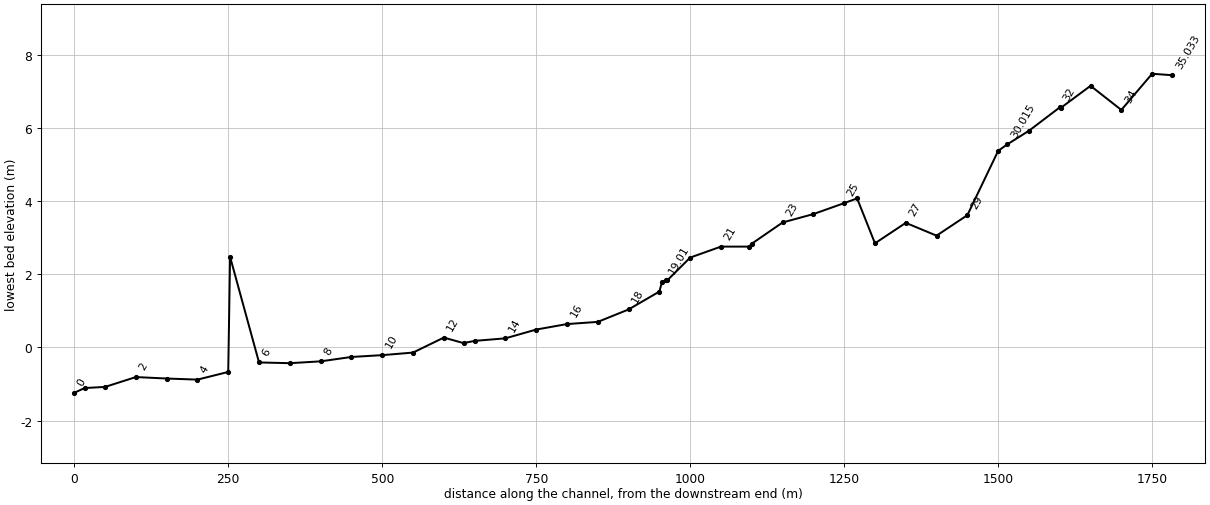
--- SUKSUK.prj (project) ---

Proj Title=SUKSUK
Current Plan=p01
Default Exp/Contr=.3,.1
SI Units
Geom File=g01
Flow File=f01
Plan File=p01
Y Axis Title=Elevation
X Axis Title(PF)=Main Channel Distance
X Axis Title(XS)=Station
BEGIN DESCRIPTION:
           BACK WATER COMPUTATION
      APPLICATION OF HEC-2 BY Samju Construction Engineering
      SUKSUK-STREEM : 30 YR
END DESCRIPTION:
DSS Export Rating Curves= 0
DSS Export Rating Curve Sorted= 0
DSS Export Volume Flow Curves= 0
DXF OffsetX= 0
DXF OffsetY= 0
DXF ScaleX= 1
DXF ScaleY= 10

--- SUKSUK.p01 (plan) ---

Plan Title=Imported Plan 01
Version=Version 3.0.1  Mar 2001
Short Identifier=Imported Pla
Geom File=g01
Flow File=f01
Subcritical Flow
K Sum by GR= 0
Std Step Tol= 0.003
Critical Tol= 0.003
Num of Std Step Trials= 20
Max Error Tol= 0.1
Flow Tol Ratio= 0.001
Split Flow NTrial= 30
Split Flow Tol= 0.02
Split Flow Ratio= 0.02
Log Output Level= 0
Friction Slope Method= 1
Unsteady Friction Slope Method= 2
Parabolic Critical Depth
Global Vel Dist= 0 , 0 , 0
Global Log Level= 0
CheckData=True
Encroach Param=-1 ,0,0, 0
Computation Interval=1HOUR
Output Interval=1HOUR
Run HTab= 0
Run UNet= 0
Run PostProcess= 0
UNET Theta= 1
UNET ZTol= 0.02
UNET ZSATol= 0.1
UNET MxIter= 20
UNET MaxInSteps= 20
UNET DtIC= 0
UNET DtMin= 0
UNET MaxCRTS= 20
UNET WFStab= 2
UNET SFStab= 1
UNET WFX= 1
UNET SFX= 1
UNET Convert EG Bridges=-1
UNET Use Existing IB Tables=-1
Instantaneous Interval=1HOUR
Write IC File= 0
Write Velocity= 0
Write Detailed= 0

--- SUKSUK.f01 (steady flow) ---

Flow Title=Imported Flow 01
Version=Version 3.0.1  Mar 2001
Number of Profiles= 1
Profile Names=PF 1
River Rch & RM=RIVER-1,Reach-1         ,35.033
      75
River Rch & RM=SUKSUK,SUKSUK          ,35.033
      75
Boundary for River Rch & Prof#=SUKSUK,SUKSUK          , 1
Up Type= 0
Dn Type= 3
Dn Slope=.0109
DSS Import GetInterval= 0
DSS Import GetPeak= 0
DSS Import FillOption= 0

--- SUKSUK.g01 (geometry) ---

Geom Title=Imported Geom 01
Version=Version 3.0.1  Mar 2001

River Reach=SUKSUK          ,SUKSUK
Reach XY= 2
              .5             .95              .5             .05

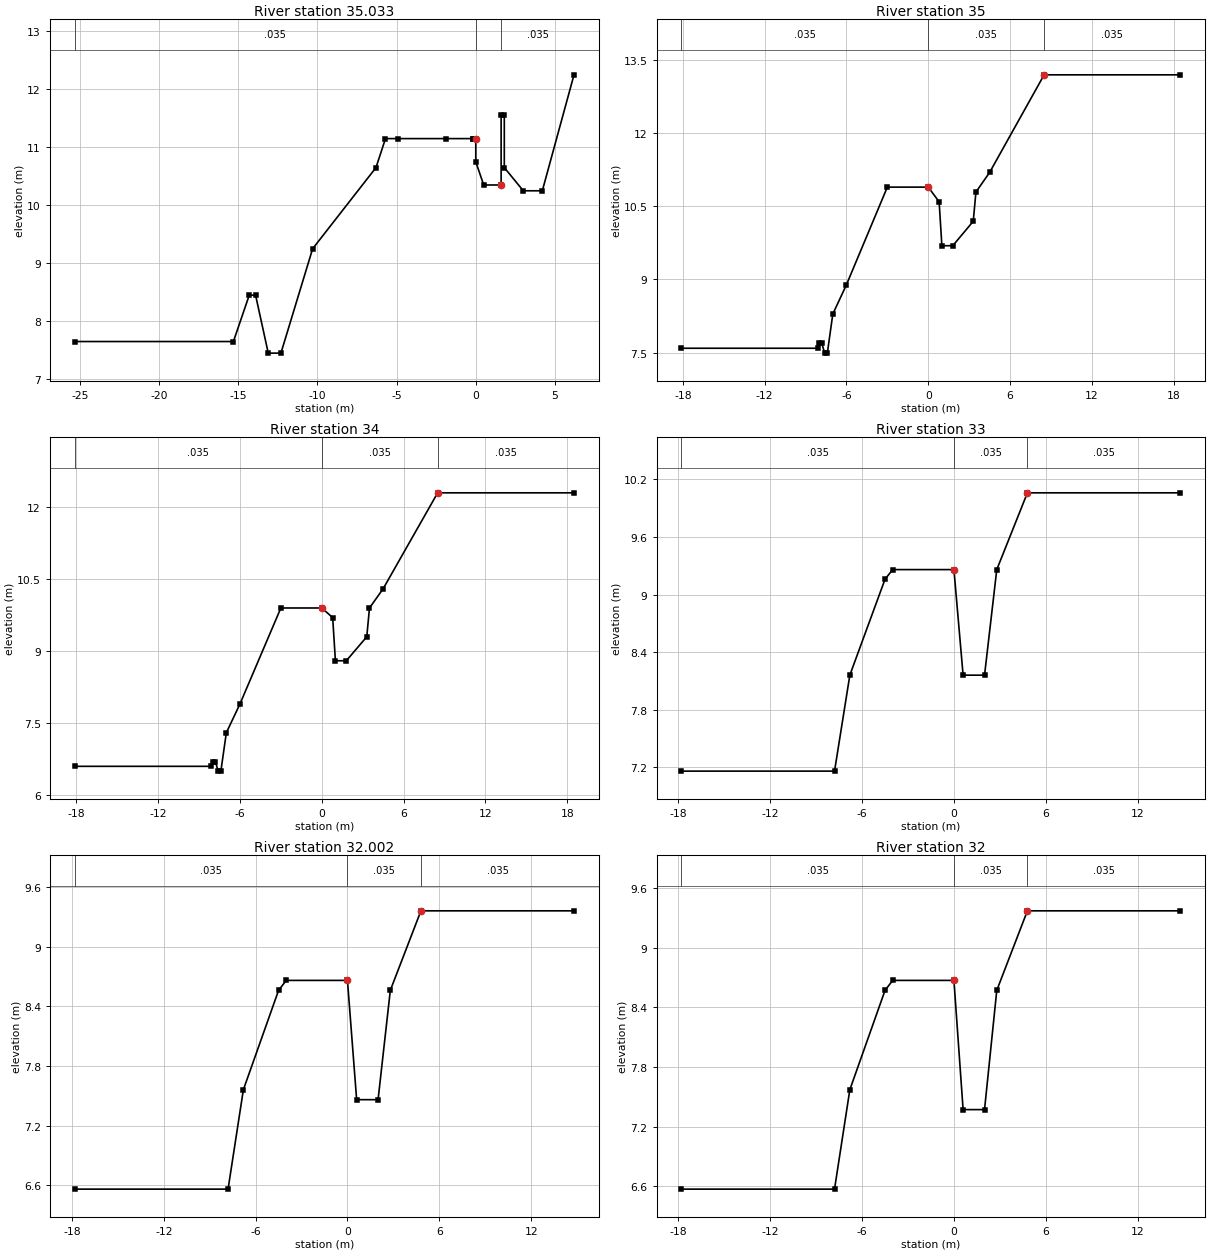
Type RM Length L Ch R = 1 ,35.033  ,33,33,33
#Sta/Elev= 23
   -25.3    7.65   -15.3    7.65   -14.3    8.45   -13.9    8.45   -13.1    7.45
   -12.3    7.45   -10.3    9.25    -6.3   10.65    -5.7   11.15    -4.9   11.15
    -1.9   11.15     -.2   11.15     -.2   11.15       0   11.15       0   10.75
      .5   10.35     1.6   10.35     1.6   11.55     1.8   11.55     1.8   10.65
       3   10.25     4.2   10.25     6.2   12.25
#Mann= 3 , 0 , 0
   -25.3    .035       0       0    .035       0     1.6    .035       0
Bank Sta=0,1.6
XS Rating Curve= 0
Exp/Cntr=.3,.1

Type RM Length L Ch R = 1 ,35      ,50,50,50
#Sta/Elev= 18
   -18.1    7.59    -8.1    7.59      -8    7.69    -7.8    7.69    -7.6    7.49
    -7.4    7.49      -7    8.29      -6    8.89      -3   10.89       0   10.89
      .8   10.59       1    9.69     1.8    9.69     3.3   10.19     3.5   10.79
     4.5   11.19     8.5   13.19    18.5   13.19
#Mann= 3 , 0 , 0
   -18.1    .035       0       0    .035       0     8.5    .035       0
Bank Sta=0,8.5
XS Rating Curve= 0
Exp/Cntr=.3,.1

Type RM Length L Ch R = 1 ,34      ,50,50,50
#Sta/Elev= 18
   -18.1     6.6    -8.1     6.6      -8     6.7    -7.8     6.7    -7.6     6.5
    -7.4     6.5      -7     7.3      -6     7.9      -3     9.9       0     9.9
      .8     9.7       1     8.8     1.8     8.8     3.3     9.3     3.5     9.9
     4.5    10.3     8.5    12.3    18.5    12.3
#Mann= 3 , 0 , 0
   -18.1    .035       0       0    .035       0     8.5    .035       0
Bank Sta=0,8.5
XS Rating Curve= 0
Exp/Cntr=.3,.1

Type RM Length L Ch R = 1 ,33      ,48,48,48
#Sta/Elev= 11
   -17.8    7.16    -7.8    7.16    -6.8    8.16    -4.5    9.16      -4    9.26
       0    9.26      .6    8.16       2    8.16     2.8    9.26     4.8   10.06
    14.8   10.06
#Mann= 3 , 0 , 0
   -17.8    .035       0       0    .035       0     4.8    .035       0
Bank Sta=0,4.8
XS Rating Curve= 0
Exp/Cntr=.3,.1

Type RM Length L Ch R = 1 ,32.002  ,2,2,2
#Sta/Elev= 11
   -17.8    6.56    -7.8    6.56    -6.8    7.56    -4.5    8.56      -4    8.66
       0    8.66      .6    7.46       2    7.46     2.8    8.56     4.8    9.36
    14.8    9.36
#Mann= 3 , 0 , 0
   -17.8    .035       0       0    .035       0     4.8    .035       0
Bank Sta=0,4.8
XS Rating Curve= 0
Exp/Cntr=.3,.1

Type RM Length L Ch R = 1 ,32      ,50,50,50
#Sta/Elev= 11
   -17.8    6.57    -7.8    6.57    -6.8    7.57    -4.5    8.57      -4    8.67
       0    8.67      .6    7.37       2    7.37     2.8    8.57     4.8    9.37
    14.8    9.37
#Mann= 3 , 0 , 0
   -17.8    .035       0       0    .035       0     4.8    .035       0
Bank Sta=0,4.8
XS Rating Curve= 0
Exp/Cntr=.3,.1

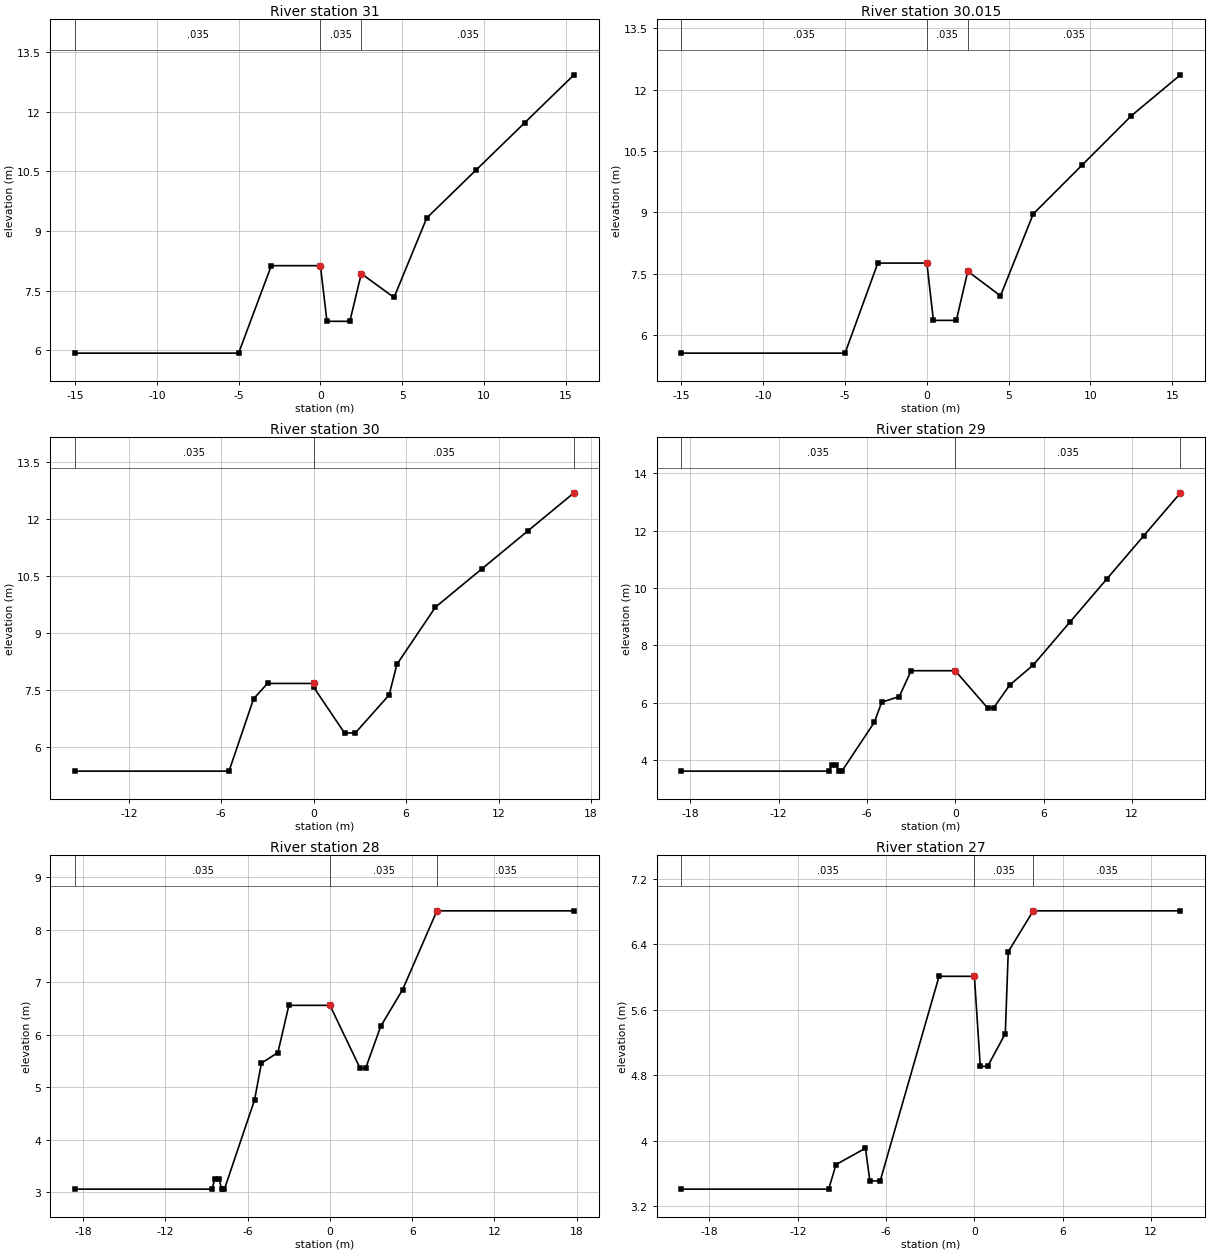
Type RM Length L Ch R = 1 ,31      ,35,35,35
#Sta/Elev= 12
     -15    5.93      -5    5.93      -3    8.13       0    8.13      .4    6.73
     1.8    6.73     2.5    7.93     4.5    7.33     6.5    9.33     9.5   10.53
    12.5   11.73    15.5   12.93
#Mann= 3 , 0 , 0
     -15    .035       0       0    .035       0     2.5    .035       0
Bank Sta=0,2.5
XS Rating Curve= 0
Exp/Cntr=.3,.1

Type RM Length L Ch R = 1 ,30.015  ,15,15,15
#Sta/Elev= 12
     -15    5.56      -5    5.56      -3    7.76       0    7.76      .4    6.36
     1.8    6.36     2.5    7.56     4.5    6.96     6.5    8.96     9.5   10.16
    12.5   11.36    15.5   12.36
#Mann= 3 , 0 , 0
     -15    .035       0       0    .035       0     2.5    .035       0
Bank Sta=0,2.5
XS Rating Curve= 0
Exp/Cntr=.3,.1

Type RM Length L Ch R = 1 ,30      ,50,50,50
#Sta/Elev= 14
   -15.5    5.38    -5.5    5.38    -3.9    7.28      -3    7.68       0    7.68
       0    7.58       2    6.38     2.7    6.38     4.9    7.38     5.4    8.18
     7.9    9.68    10.9   10.68    13.9   11.68    16.9   12.68
#Mann= 3 , 0 , 0
   -15.5    .035       0       0    .035       0    16.9    .035       0
Bank Sta=0,16.9
XS Rating Curve= 0
Exp/Cntr=.3,.1

Type RM Length L Ch R = 1 ,29      ,50,50,50
#Sta/Elev= 19
   -18.6    3.62    -8.6    3.62    -8.4    3.82    -8.1    3.82    -7.9    3.62
    -7.7    3.62    -5.5    5.32      -5    6.02    -3.8    6.22      -3    7.12
       0    7.12     2.2    5.82     2.6    5.82     3.7    6.62     5.3    7.32
     7.8    8.82    10.3   10.32    12.8   11.82    15.3   13.32
#Mann= 3 , 0 , 0
   -18.6    .035       0       0    .035       0    15.3    .035       0
Bank Sta=0,15.3
XS Rating Curve= 0
Exp/Cntr=.3,.1

Type RM Length L Ch R = 1 ,28      ,50,50,50
#Sta/Elev= 17
   -18.6    3.06    -8.6    3.06    -8.4    3.26    -8.1    3.26    -7.9    3.06
    -7.7    3.06    -5.5    4.76      -5    5.46    -3.8    5.66      -3    6.56
       0    6.56     2.2    5.36     2.6    5.36     3.7    6.16     5.3    6.86
     7.8    8.36    17.8    8.36
#Mann= 3 , 0 , 0
   -18.6    .035       0       0    .035       0     7.8    .035       0
Bank Sta=0,7.8
XS Rating Curve= 0
Exp/Cntr=.3,.1

Type RM Length L Ch R = 1 ,27      ,50,50,50
#Sta/Elev= 14
   -19.9    3.41    -9.9    3.41    -9.4    3.71    -7.4    3.91    -7.1    3.51
    -6.4    3.51    -2.4    6.01       0    6.01      .4    4.91      .9    4.91
     2.1    5.31     2.3    6.31       4    6.81      14    6.81
#Mann= 3 , 0 , 0
   -19.9    .035       0       0    .035       0       4    .035       0
Bank Sta=0,4
XS Rating Curve= 0
Exp/Cntr=.3,.1

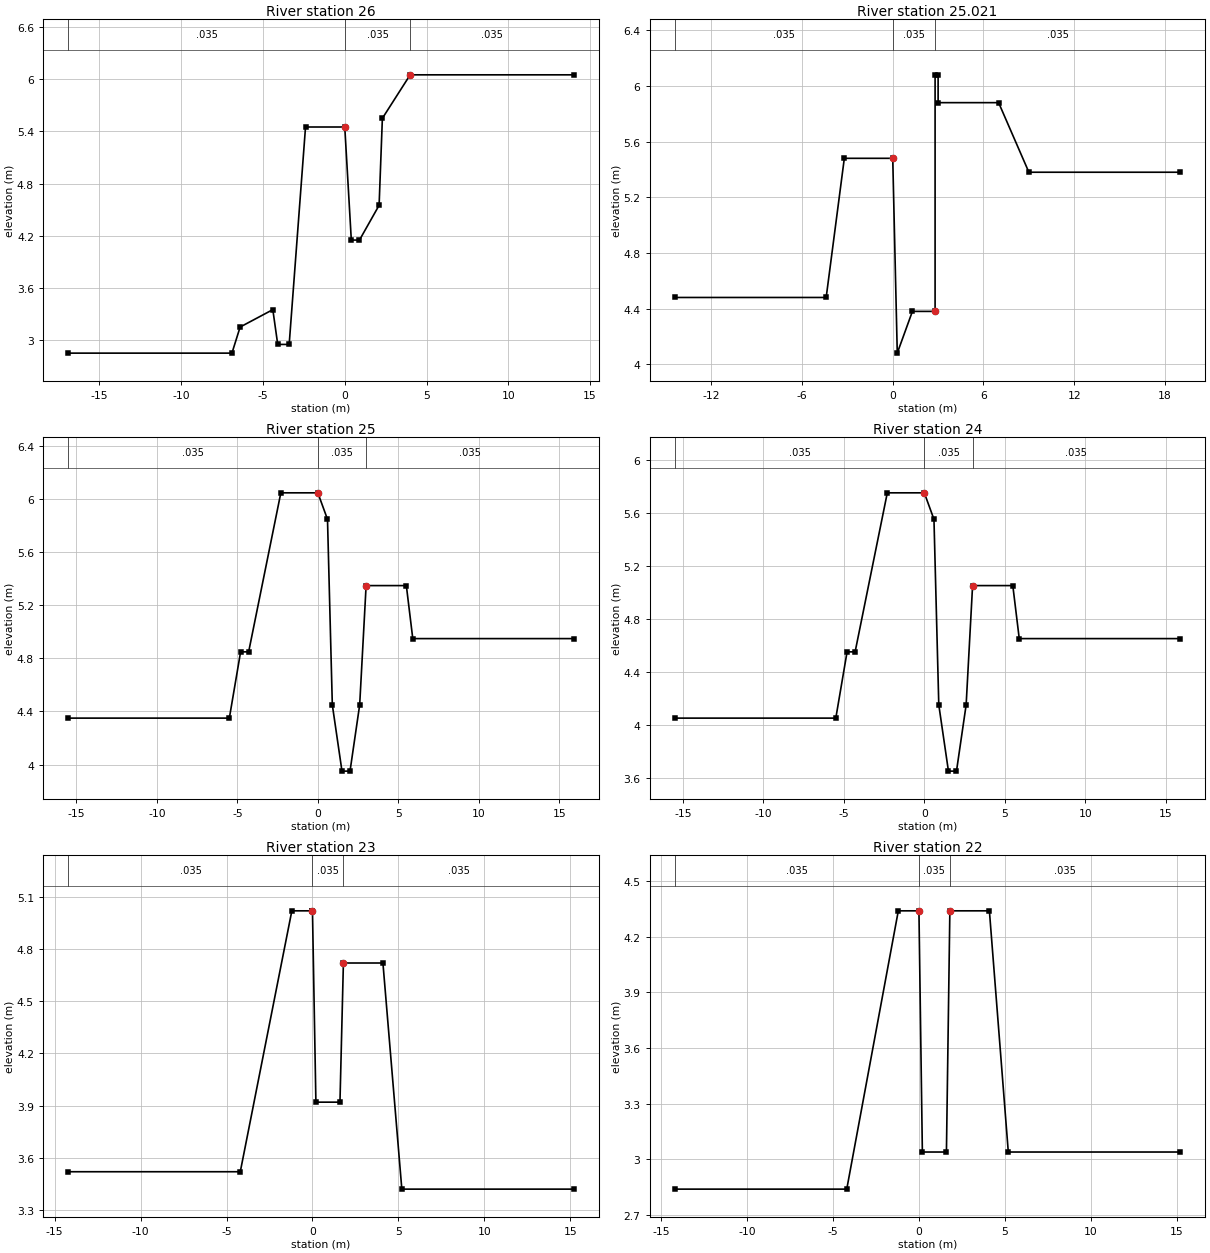
Type RM Length L Ch R = 1 ,26      ,29,29,29
#Sta/Elev= 14
   -16.9    2.85    -6.9    2.85    -6.4    3.15    -4.4    3.35    -4.1    2.95
    -3.4    2.95    -2.4    5.45       0    5.45      .4    4.15      .9    4.15
     2.1    4.55     2.3    5.55       4    6.05      14    6.05
#Mann= 3 , 0 , 0
   -16.9    .035       0       0    .035       0       4    .035       0
Bank Sta=0,4
XS Rating Curve= 0
Exp/Cntr=.3,.1

Type RM Length L Ch R = 1 ,25.021  ,21,21,21
#Sta/Elev= 13
   -14.4    4.48    -4.4    4.48    -3.2    5.48       0    5.48      .3    4.08
     1.3    4.38     2.8    4.38     2.8    6.08       3    6.08       3    5.88
       7    5.88       9    5.38      19    5.38
#Mann= 3 , 0 , 0
   -14.4    .035       0       0    .035       0     2.8    .035       0
Bank Sta=0,2.8
XS Rating Curve= 0
Exp/Cntr=.3,.1

Type RM Length L Ch R = 1 ,25      ,50,50,50
#Sta/Elev= 15
   -15.5    4.35    -5.5    4.35    -4.8    4.85    -4.3    4.85    -2.3    6.05
       0    6.05      .6    5.85      .9    4.45     1.5    3.95       2    3.95
     2.6    4.45       3    5.35     5.5    5.35     5.9    4.95    15.9    4.95
#Mann= 3 , 0 , 0
   -15.5    .035       0       0    .035       0       3    .035       0
Bank Sta=0,3
XS Rating Curve= 0
Exp/Cntr=.3,.1

Type RM Length L Ch R = 1 ,24      ,50,50,50
#Sta/Elev= 15
   -15.5    4.05    -5.5    4.05    -4.8    4.55    -4.3    4.55    -2.3    5.75
       0    5.75      .6    5.55      .9    4.15     1.5    3.65       2    3.65
     2.6    4.15       3    5.05     5.5    5.05     5.9    4.65    15.9    4.65
#Mann= 3 , 0 , 0
   -15.5    .035       0       0    .035       0       3    .035       0
Bank Sta=0,3
XS Rating Curve= 0
Exp/Cntr=.3,.1

Type RM Length L Ch R = 1 ,23      ,50,50,50
#Sta/Elev= 11
   -14.2    3.52    -4.2    3.52    -1.2    5.02       0    5.02       0    5.02
      .2    3.92     1.6    3.92     1.8    4.72     4.1    4.72     5.2    3.42
    15.2    3.42
#Mann= 3 , 0 , 0
   -14.2    .035       0       0    .035       0     1.8    .035       0
Bank Sta=0,1.8
XS Rating Curve= 0
Exp/Cntr=.3,.1

Type RM Length L Ch R = 1 ,22      ,4,4,4
#Sta/Elev= 10
   -14.2    2.84    -4.2    2.84    -1.2    4.34       0    4.34      .2    3.04
     1.6    3.04     1.8    4.34     4.1    4.34     5.2    3.04    15.2    3.04
#Mann= 3 , 0 , 0
   -14.2    .035       0       0    .035       0     1.8    .035       0
Bank Sta=0,1.8
XS Rating Curve= 0
Exp/Cntr=.3,.1

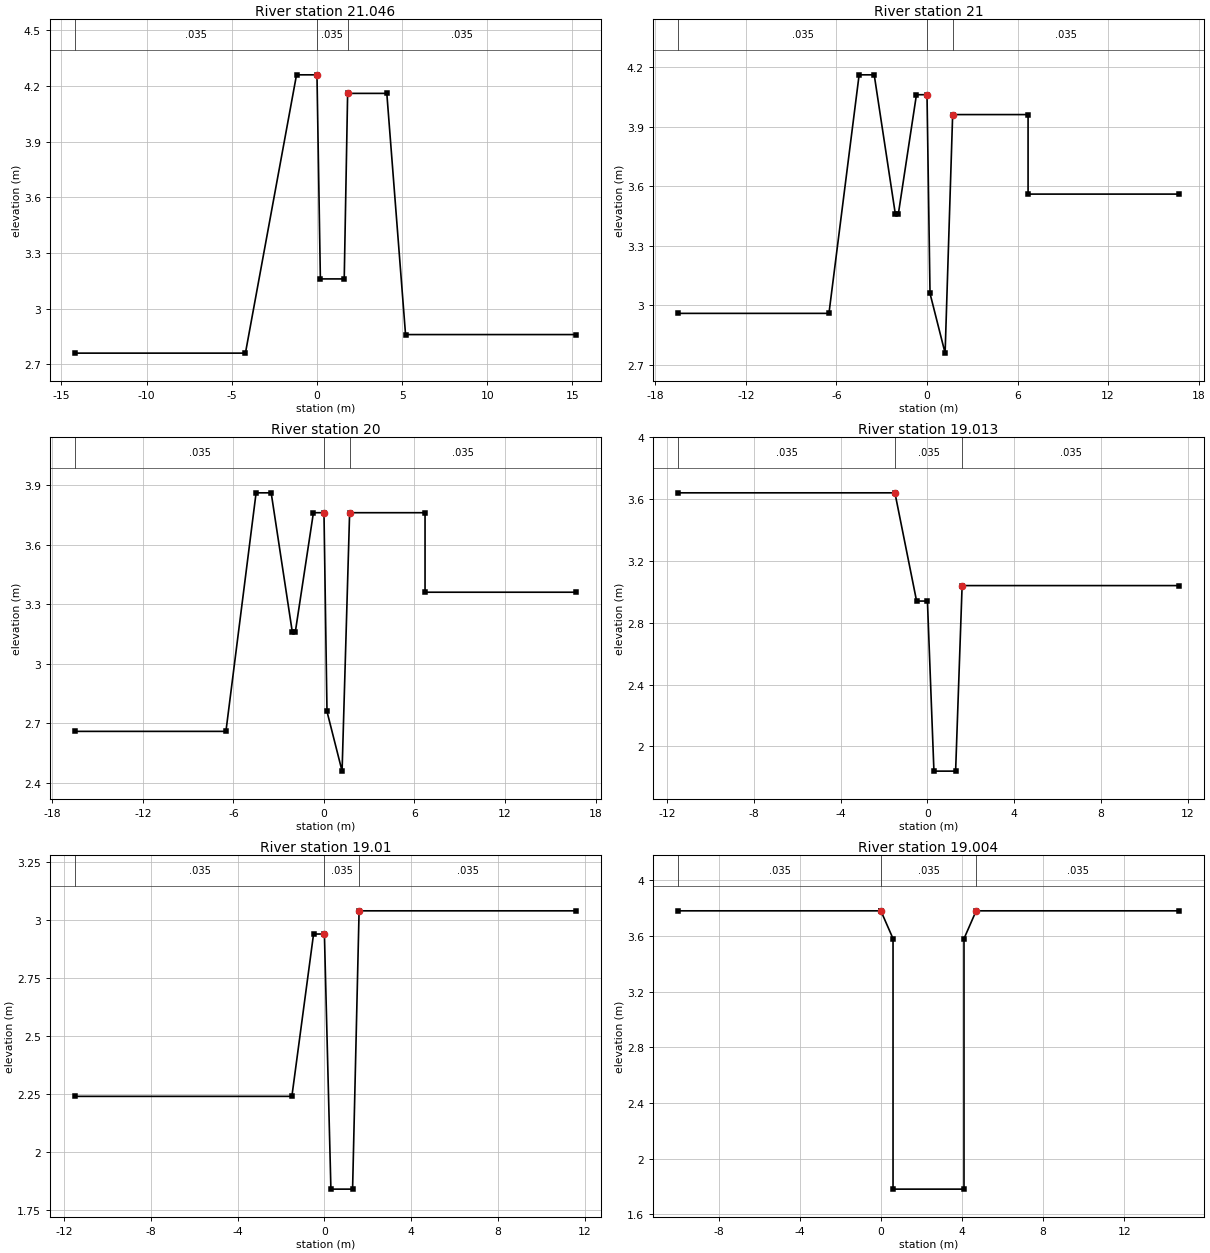
Type RM Length L Ch R = 1 ,21.046  ,46,46,46
#Sta/Elev= 10
   -14.2    2.76    -4.2    2.76    -1.2    4.26       0    4.26      .2    3.16
     1.6    3.16     1.8    4.16     4.1    4.16     5.2    2.86    15.2    2.86
#Mann= 3 , 0 , 0
   -14.2    .035       0       0    .035       0     1.8    .035       0
Bank Sta=0,1.8
XS Rating Curve= 0
Exp/Cntr=.3,.1

Type RM Length L Ch R = 1 ,21      ,50,50,50
#Sta/Elev= 14
   -16.5    2.96    -6.5    2.96    -4.5    4.16    -3.5    4.16    -2.1    3.46
    -1.9    3.46     -.7    4.06       0    4.06      .2    3.06     1.2    2.76
     1.7    3.96     6.7    3.96     6.7    3.56    16.7    3.56
#Mann= 3 , 0 , 0
   -16.5    .035       0       0    .035       0     1.7    .035       0
Bank Sta=0,1.7
XS Rating Curve= 0
Exp/Cntr=.3,.1

Type RM Length L Ch R = 1 ,20      ,37,37,37
#Sta/Elev= 14
   -16.5    2.66    -6.5    2.66    -4.5    3.86    -3.5    3.86    -2.1    3.16
    -1.9    3.16     -.7    3.76       0    3.76      .2    2.76     1.2    2.46
     1.7    3.76     6.7    3.76     6.7    3.36    16.7    3.36
#Mann= 3 , 0 , 0
   -16.5    .035       0       0    .035       0     1.7    .035       0
Bank Sta=0,1.7
XS Rating Curve= 0
Exp/Cntr=.3,.1

Type RM Length L Ch R = 1 ,19.013  ,3,3,3
#Sta/Elev= 8
   -11.5    3.64    -1.5    3.64     -.5    2.94       0    2.94      .3    1.84
     1.3    1.84     1.6    3.04    11.6    3.04
#Mann= 3 , 0 , 0
   -11.5    .035       0    -1.5    .035       0     1.6    .035       0
Bank Sta=-1.5,1.6
XS Rating Curve= 0
Exp/Cntr=.3,.1

Type RM Length L Ch R = 1 ,19.01   ,6,6,6
#Sta/Elev= 8
   -11.5    2.24    -1.5    2.24     -.5    2.94       0    2.94      .3    1.84
     1.3    1.84     1.6    3.04    11.6    3.04
#Mann= 3 , 0 , 0
   -11.5    .035       0       0    .035       0     1.6    .035       0
Bank Sta=0,1.6
XS Rating Curve= 0
Exp/Cntr=.3,.1

Type RM Length L Ch R = 1 ,19.004  ,4,4,4
#Sta/Elev= 9
     -10    3.78       0    3.78       0    3.78      .6    3.58      .6    1.78
     4.1    1.78     4.1    3.58     4.7    3.78    14.7    3.78
#Mann= 3 , 0 , 0
     -10    .035       0       0    .035       0     4.7    .035       0
Bank Sta=0,4.7
XS Rating Curve= 0
Exp/Cntr=.3,.1

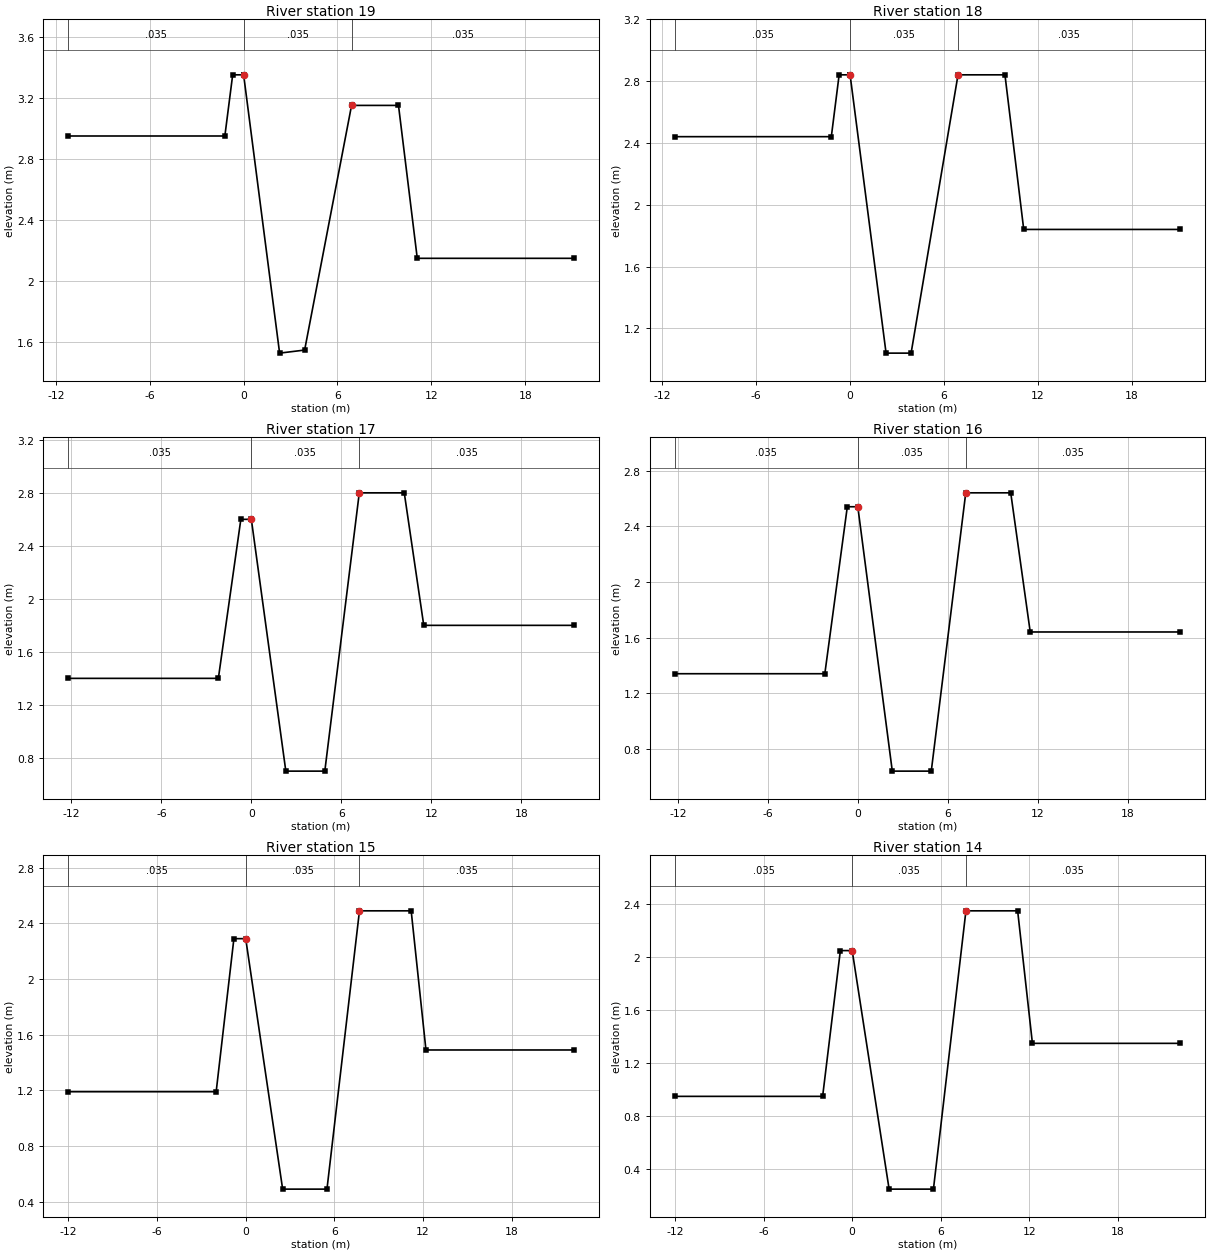
Type RM Length L Ch R = 1 ,19      ,50,50,50
#Sta/Elev= 11
   -11.2    2.95    -1.2    2.95     -.7    3.35       0    3.35       0    3.35
     2.3    1.53     3.9    1.55     6.9    3.15     9.9    3.15    11.1    2.15
    21.1    2.15
#Mann= 3 , 0 , 0
   -11.2    .035       0       0    .035       0     6.9    .035       0
Bank Sta=0,6.9
XS Rating Curve= 0
Exp/Cntr=.3,.1

Type RM Length L Ch R = 1 ,18      ,50,50,50
#Sta/Elev= 11
   -11.2    2.44    -1.2    2.44     -.7    2.84       0    2.84       0    2.84
     2.3    1.04     3.9    1.04     6.9    2.84     9.9    2.84    11.1    1.84
    21.1    1.84
#Mann= 3 , 0 , 0
   -11.2    .035       0       0    .035       0     6.9    .035       0
Bank Sta=0,6.9
XS Rating Curve= 0
Exp/Cntr=.3,.1

Type RM Length L Ch R = 1 ,17      ,50,50,50
#Sta/Elev= 10
   -12.2     1.4    -2.2     1.4     -.7     2.6       0     2.6     2.3      .7
     4.9      .7     7.2     2.8    10.2     2.8    11.5     1.8    21.5     1.8
#Mann= 3 , 0 , 0
   -12.2    .035       0       0    .035       0     7.2    .035       0
Bank Sta=0,7.2
XS Rating Curve= 0
Exp/Cntr=.3,.1

Type RM Length L Ch R = 1 ,16      ,50,50,50
#Sta/Elev= 10
   -12.2    1.34    -2.2    1.34     -.7    2.54       0    2.54     2.3     .64
     4.9     .64     7.2    2.64    10.2    2.64    11.5    1.64    21.5    1.64
#Mann= 3 , 0 , 0
   -12.2    .035       0       0    .035       0     7.2    .035       0
Bank Sta=0,7.2
XS Rating Curve= 0
Exp/Cntr=.3,.1

Type RM Length L Ch R = 1 ,15      ,50,50,50
#Sta/Elev= 10
     -12    1.19      -2    1.19     -.8    2.29       0    2.29     2.5     .49
     5.5     .49     7.7    2.49    11.2    2.49    12.2    1.49    22.2    1.49
#Mann= 3 , 0 , 0
     -12    .035       0       0    .035       0     7.7    .035       0
Bank Sta=0,7.7
XS Rating Curve= 0
Exp/Cntr=.3,.1

Type RM Length L Ch R = 1 ,14      ,50,50,50
#Sta/Elev= 10
     -12     .95      -2     .95     -.8    2.05       0    2.05     2.5     .25
     5.5     .25     7.7    2.35    11.2    2.35    12.2    1.35    22.2    1.35
#Mann= 3 , 0 , 0
     -12    .035       0       0    .035       0     7.7    .035       0
Bank Sta=0,7.7
XS Rating Curve= 0
Exp/Cntr=.3,.1

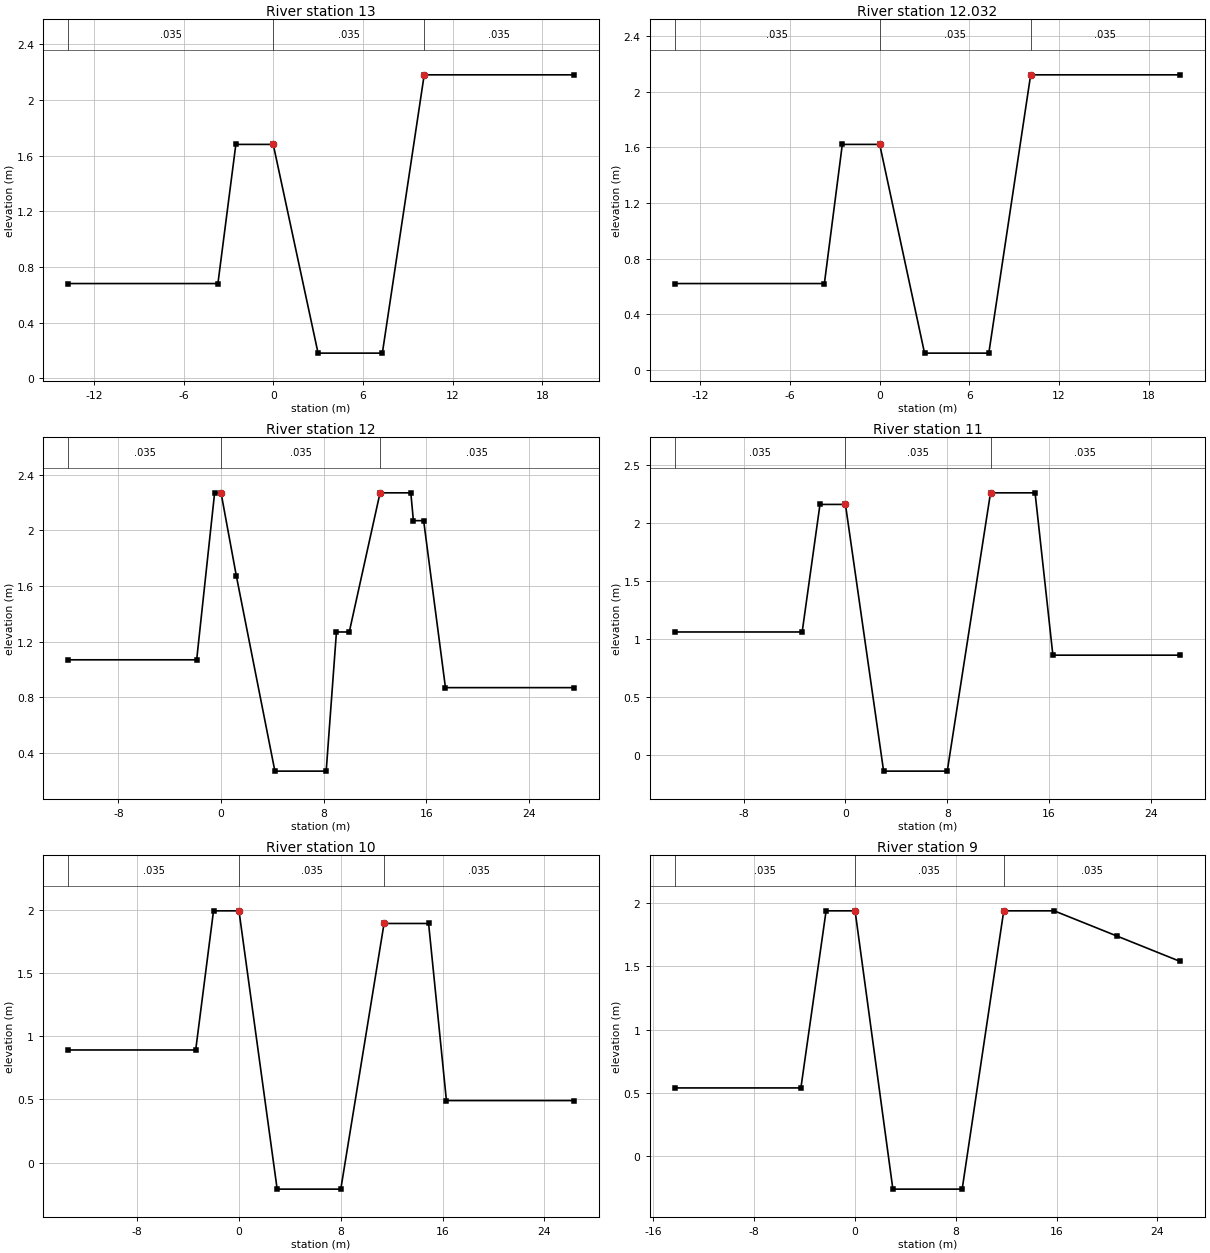
Type RM Length L Ch R = 1 ,13      ,18,18,18
#Sta/Elev= 8
   -13.7     .68    -3.7     .68    -2.5    1.68       0    1.68       3     .18
     7.3     .18    10.1    2.18    20.1    2.18
#Mann= 3 , 0 , 0
   -13.7    .035       0       0    .035       0    10.1    .035       0
Bank Sta=0,10.1
XS Rating Curve= 0
Exp/Cntr=.3,.1

Type RM Length L Ch R = 1 ,12.032  ,32,32,32
#Sta/Elev= 8
   -13.7     .62    -3.7     .62    -2.5    1.62       0    1.62       3     .12
     7.3     .12    10.1    2.12    20.1    2.12
#Mann= 3 , 0 , 0
   -13.7    .035       0       0    .035       0    10.1    .035       0
Bank Sta=0,10.1
XS Rating Curve= 0
Exp/Cntr=.3,.1

Type RM Length L Ch R = 1 ,12      ,50,50,50
#Sta/Elev= 15
   -11.9    1.07    -1.9    1.07     -.5    2.27       0    2.27     1.2    1.67
     4.2     .27     8.2     .27       9    1.27      10    1.27    12.4    2.27
    14.8    2.27      15    2.07    15.8    2.07    17.5     .87    27.5     .87
#Mann= 3 , 0 , 0
   -11.9    .035       0       0    .035       0    12.4    .035       0
Bank Sta=0,12.4
XS Rating Curve= 0
Exp/Cntr=.3,.1

Type RM Length L Ch R = 1 ,11      ,50,50,50
#Sta/Elev= 10
   -13.4    1.06    -3.4    1.06      -2    2.16       0    2.16       3    -.14
       8    -.14    11.4    2.26    14.9    2.26    16.3     .86    26.3     .86
#Mann= 3 , 0 , 0
   -13.4    .035       0       0    .035       0    11.4    .035       0
Bank Sta=0,11.4
XS Rating Curve= 0
Exp/Cntr=.3,.1

Type RM Length L Ch R = 1 ,10      ,50,50,50
#Sta/Elev= 10
   -13.4     .89    -3.4     .89      -2    1.99       0    1.99       3    -.21
       8    -.21    11.4    1.89    14.9    1.89    16.3     .49    26.3     .49
#Mann= 3 , 0 , 0
   -13.4    .035       0       0    .035       0    11.4    .035       0
Bank Sta=0,11.4
XS Rating Curve= 0
Exp/Cntr=.3,.1

Type RM Length L Ch R = 1 ,9       ,50,50,50
#Sta/Elev= 10
   -14.3     .54    -4.3     .54    -2.3    1.94       0    1.94       3    -.26
     8.5    -.26    11.8    1.94    15.8    1.94    20.8    1.74    25.8    1.54
#Mann= 3 , 0 , 0
   -14.3    .035       0       0    .035       0    11.8    .035       0
Bank Sta=0,11.8
XS Rating Curve= 0
Exp/Cntr=.3,.1

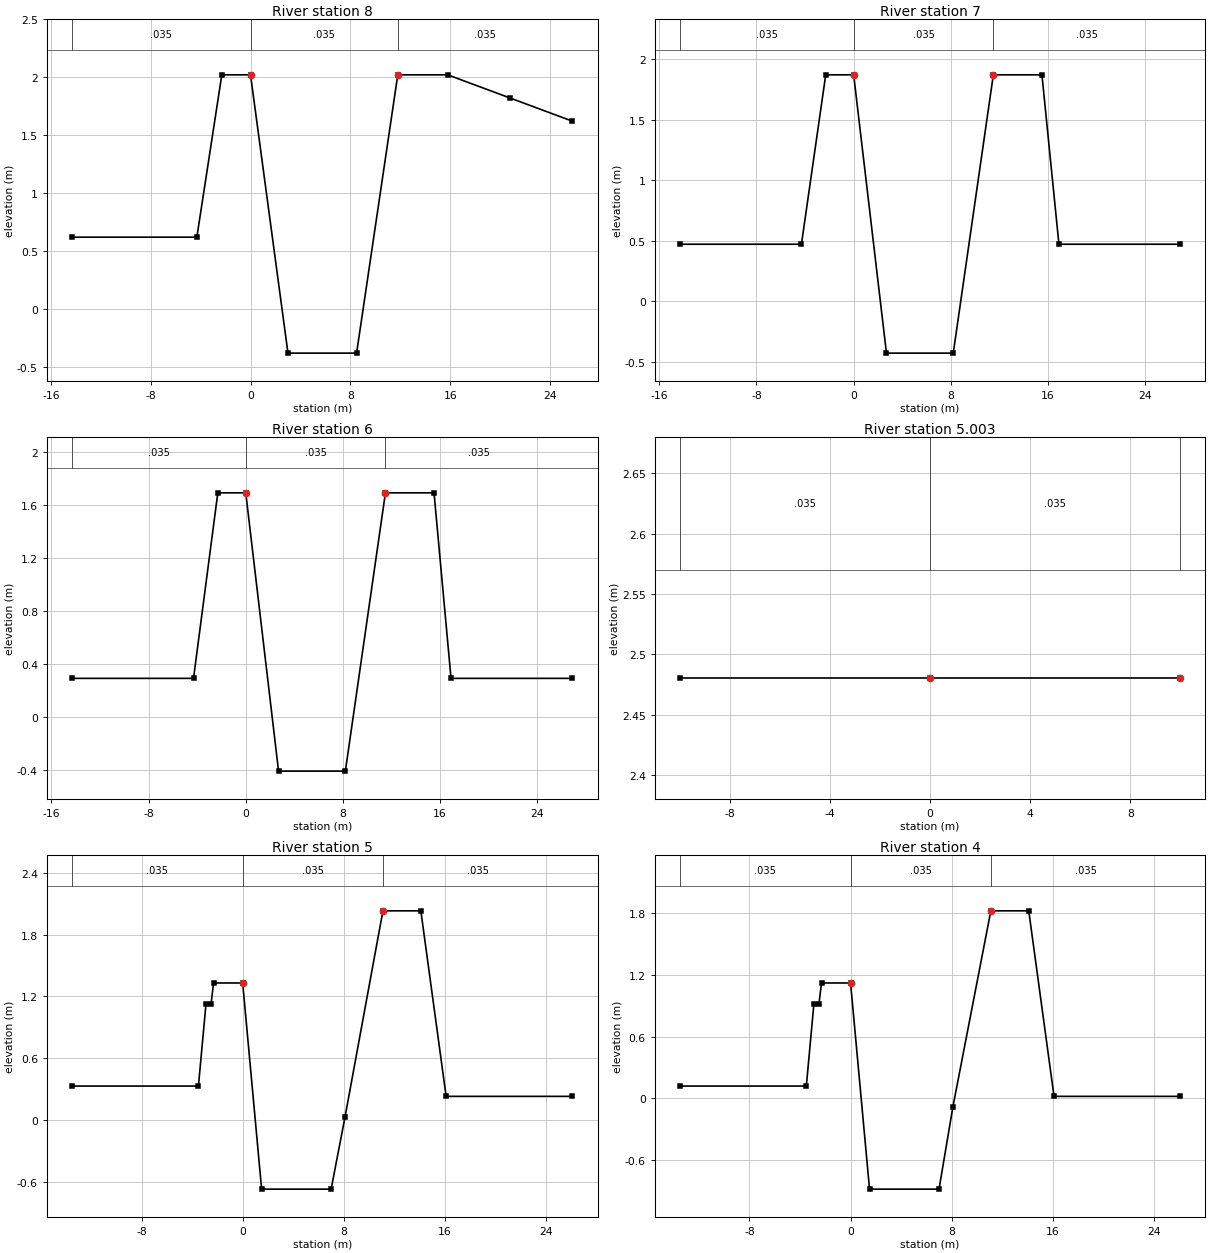
Type RM Length L Ch R = 1 ,8       ,50,50,50
#Sta/Elev= 10
   -14.3     .62    -4.3     .62    -2.3    2.02       0    2.02       3    -.38
     8.5    -.38    11.8    2.02    15.8    2.02    20.8    1.82    25.8    1.62
#Mann= 3 , 0 , 0
   -14.3    .035       0       0    .035       0    11.8    .035       0
Bank Sta=0,11.8
XS Rating Curve= 0
Exp/Cntr=.3,.1

Type RM Length L Ch R = 1 ,7       ,50,50,50
#Sta/Elev= 10
   -14.3     .47    -4.3     .47    -2.3    1.87       0    1.87     2.7    -.43
     8.2    -.43    11.5    1.87    15.5    1.87    16.9     .47    26.9     .47
#Mann= 3 , 0 , 0
   -14.3    .035       0       0    .035       0    11.5    .035       0
Bank Sta=0,11.5
XS Rating Curve= 0
Exp/Cntr=.3,.1

Type RM Length L Ch R = 1 ,6       ,47,47,47
#Sta/Elev= 10
   -14.3     .29    -4.3     .29    -2.3    1.69       0    1.69     2.7    -.41
     8.2    -.41    11.5    1.69    15.5    1.69    16.9     .29    26.9     .29
#Mann= 3 , 0 , 0
   -14.3    .035       0       0    .035       0    11.5    .035       0
Bank Sta=0,11.5
XS Rating Curve= 0
Exp/Cntr=.3,.1

Type RM Length L Ch R = 1 ,5.003   ,3,3,3
#Sta/Elev= 3
     -10    2.48       0    2.48      10    2.48
#Mann= 3 , 0 , 0
     -10    .035       0       0    .035       0      10    .035       0
Bank Sta=0,10
XS Rating Curve= 0
Exp/Cntr=.3,.1

Type RM Length L Ch R = 1 ,5       ,50,50,50
#Sta/Elev= 13
   -13.5     .33    -3.5     .33    -2.9    1.13    -2.5    1.13    -2.3    1.33
       0    1.33     1.5    -.67       7    -.67     8.1     .03    11.1    2.03
    14.1    2.03    16.1     .23    26.1     .23
#Mann= 3 , 0 , 0
   -13.5    .035       0       0    .035       0    11.1    .035       0
Bank Sta=0,11.1
XS Rating Curve= 0
Exp/Cntr=.3,.1

Type RM Length L Ch R = 1 ,4       ,50,50,50
#Sta/Elev= 13
   -13.5     .12    -3.5     .12    -2.9     .92    -2.5     .92    -2.3    1.12
       0    1.12     1.5    -.88       7    -.88     8.1    -.08    11.1    1.82
    14.1    1.82    16.1     .02    26.1     .02
#Mann= 3 , 0 , 0
   -13.5    .035       0       0    .035       0    11.1    .035       0
Bank Sta=0,11.1
XS Rating Curve= 0
Exp/Cntr=.3,.1

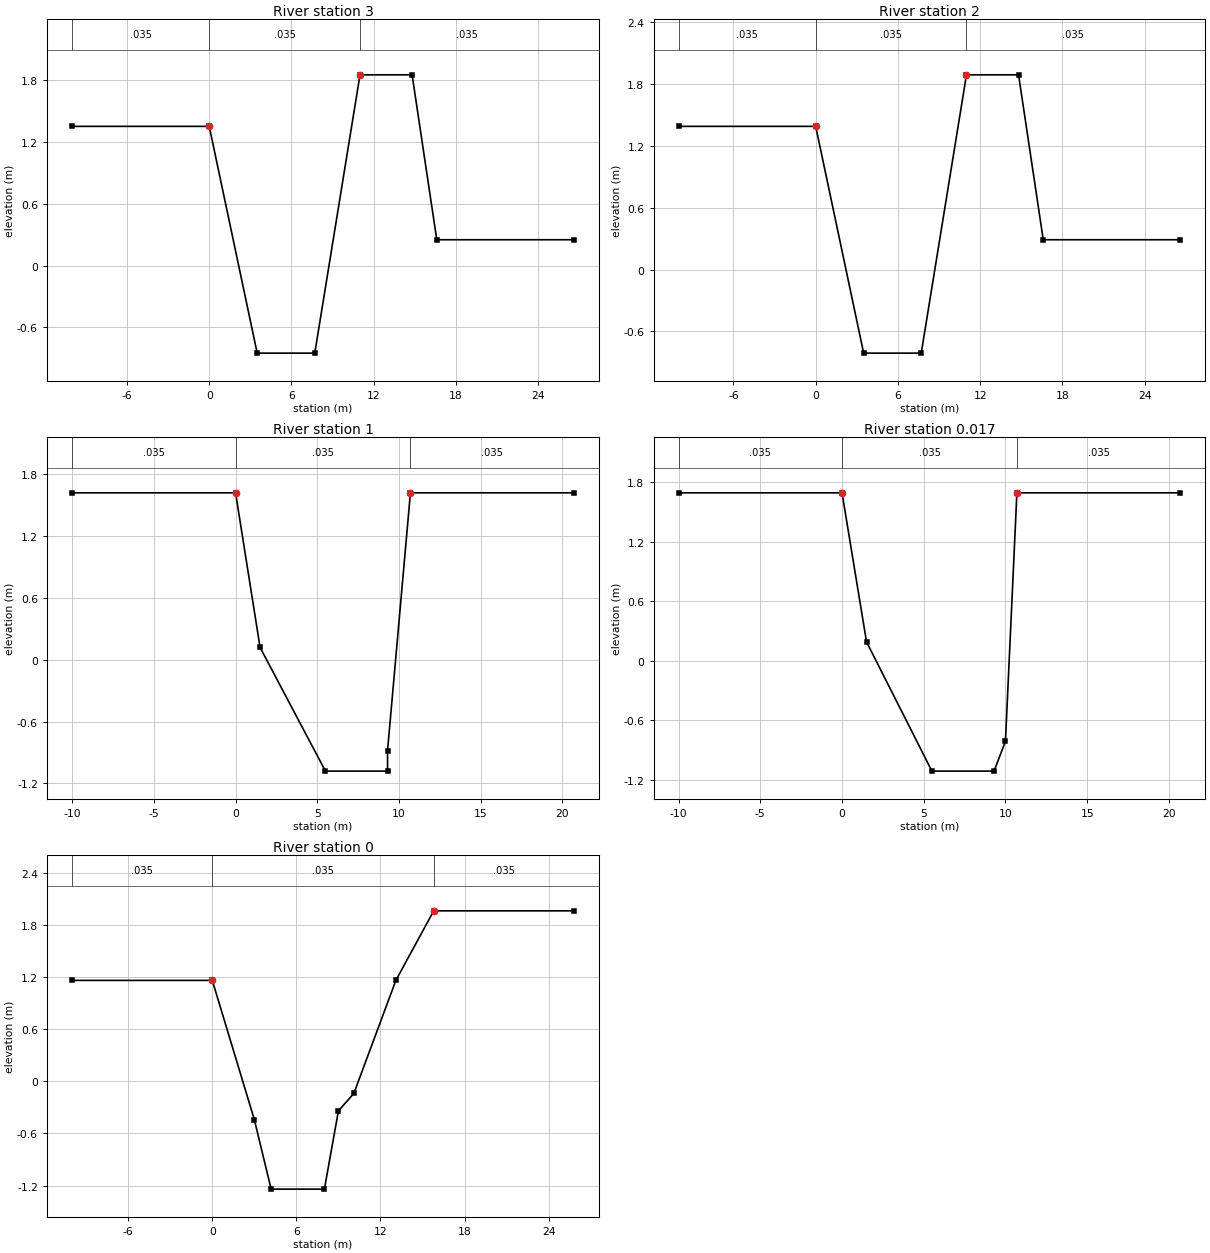
Type RM Length L Ch R = 1 ,3       ,50,50,50
#Sta/Elev= 8
     -10    1.35       0    1.35     3.5    -.85     7.7    -.85      11    1.85
    14.8    1.85    16.6     .25    26.6     .25
#Mann= 3 , 0 , 0
     -10    .035       0       0    .035       0      11    .035       0
Bank Sta=0,11
XS Rating Curve= 0
Exp/Cntr=.3,.1

Type RM Length L Ch R = 1 ,2       ,50,50,50
#Sta/Elev= 8
     -10    1.39       0    1.39     3.5    -.81     7.7    -.81      11    1.89
    14.8    1.89    16.6     .29    26.6     .29
#Mann= 3 , 0 , 0
     -10    .035       0       0    .035       0      11    .035       0
Bank Sta=0,11
XS Rating Curve= 0
Exp/Cntr=.3,.1

Type RM Length L Ch R = 1 ,1       ,33,33,33
#Sta/Elev= 8
     -10    1.62       0    1.62     1.5     .12     5.5   -1.08     9.3   -1.08
     9.3    -.88    10.7    1.62    20.7    1.62
#Mann= 3 , 0 , 0
     -10    .035       0       0    .035       0    10.7    .035       0
Bank Sta=0,10.7
XS Rating Curve= 0
Exp/Cntr=.3,.1

Type RM Length L Ch R = 1 ,0.017   ,17,17,17
#Sta/Elev= 8
     -10    1.69       0    1.69     1.5     .19     5.5   -1.11     9.3   -1.11
      10    -.81    10.7    1.69    20.7    1.69
#Mann= 3 , 0 , 0
     -10    .035       0       0    .035       0    10.7    .035       0
Bank Sta=0,10.7
XS Rating Curve= 0
Exp/Cntr=.3,.1

Type RM Length L Ch R = 1 ,0       ,0,0,0
#Sta/Elev= 10
     -10    1.16       0    1.16       3    -.44     4.2   -1.24       8   -1.24
       9    -.34    10.1    -.14    13.1    1.16    15.8    1.96    25.8    1.96
#Mann= 3 , 0 , 0
     -10    .035       0       0    .035       0    15.8    .035       0
Bank Sta=0,15.8
XS Rating Curve= 0
Exp/Cntr=.3,.1

Chan Stop Cuts=-1