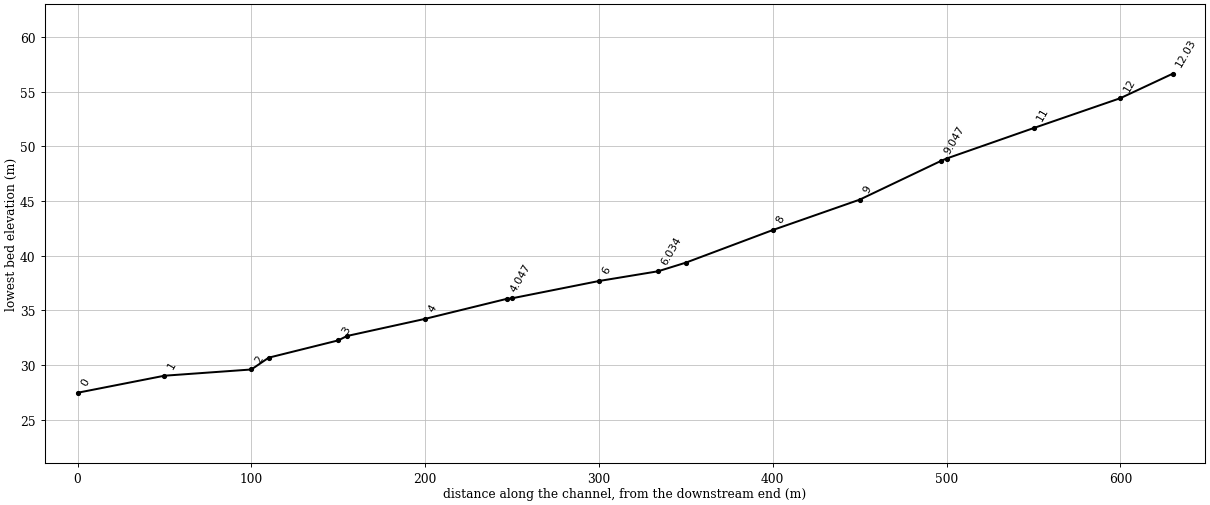
--- KORITGOL.prj (project) ---

Proj Title=KORITGOL
Current Plan=p01
Default Exp/Contr=.3,.1
SI Units
Geom File=g01
Flow File=f01
Plan File=p01
Y Axis Title=Elevation
X Axis Title(PF)=Main Channel Distance
X Axis Title(XS)=Station
BEGIN DESCRIPTION:
           BACK WATER COMPUTATION
      APPLICATION OF HEC-2 BY Samju Construction Engineering
      GORIGOL-STREEM : 30 YR
END DESCRIPTION:
DSS Export Rating Curves= 0
DSS Export Rating Curve Sorted= 0
DSS Export Volume Flow Curves= 0
DXF OffsetX= 0
DXF OffsetY= 0
DXF ScaleX= 1
DXF ScaleY= 10

--- KORITGOL.p01 (plan) ---

Plan Title=Imported Plan 01
Version=Version 3.0.1  Mar 2001
Short Identifier=Imported Pla
Geom File=g01
Flow File=f01
Subcritical Flow
K Sum by GR= 0
Std Step Tol= 0.003
Critical Tol= 0.003
Num of Std Step Trials= 20
Max Error Tol= 0.1
Flow Tol Ratio= 0.001
Split Flow NTrial= 30
Split Flow Tol= 0.02
Split Flow Ratio= 0.02
Log Output Level= 0
Friction Slope Method= 1
Unsteady Friction Slope Method= 2
Parabolic Critical Depth
Global Vel Dist= 0 , 0 , 0
Global Log Level= 0
CheckData=True
Encroach Param=-1 ,0,0, 0
Computation Interval=1HOUR
Output Interval=1HOUR
Run HTab= 0
Run UNet= 0
Run PostProcess= 0
UNET Theta= 1
UNET ZTol= 0.02
UNET ZSATol= 0.1
UNET MxIter= 20
UNET MaxInSteps= 20
UNET DtIC= 0
UNET DtMin= 0
UNET MaxCRTS= 20
UNET WFStab= 2
UNET SFStab= 1
UNET WFX= 1
UNET SFX= 1
UNET Convert EG Bridges=-1
UNET Use Existing IB Tables=-1
Instantaneous Interval=1HOUR
Write IC File= 0
Write Velocity= 0
Write Detailed= 0

--- KORITGOL.f01 (steady flow) ---

Flow Title=Imported Flow 01
Version=Version 3.0.1  Mar 2001
Number of Profiles= 1
Profile Names=PF 1
River Rch & RM=RIVER-1,Reach-1         ,12.03
      75
River Rch & RM=KORITGOL,KORITGOL        ,12.03
      75
Boundary for River Rch & Prof#=KORITGOL,KORITGOL        , 1
Up Type= 0
Dn Type= 3
Dn Slope=.0109
DSS Import GetInterval= 0
DSS Import GetPeak= 0
DSS Import FillOption= 0

--- KORITGOL.g01 (geometry) ---

Geom Title=Imported Geom 01
Version=Version 3.0.1  Mar 2001

River Reach=KORITGOL        ,KORITGOL
Reach XY= 2
              .5             .95              .5             .05

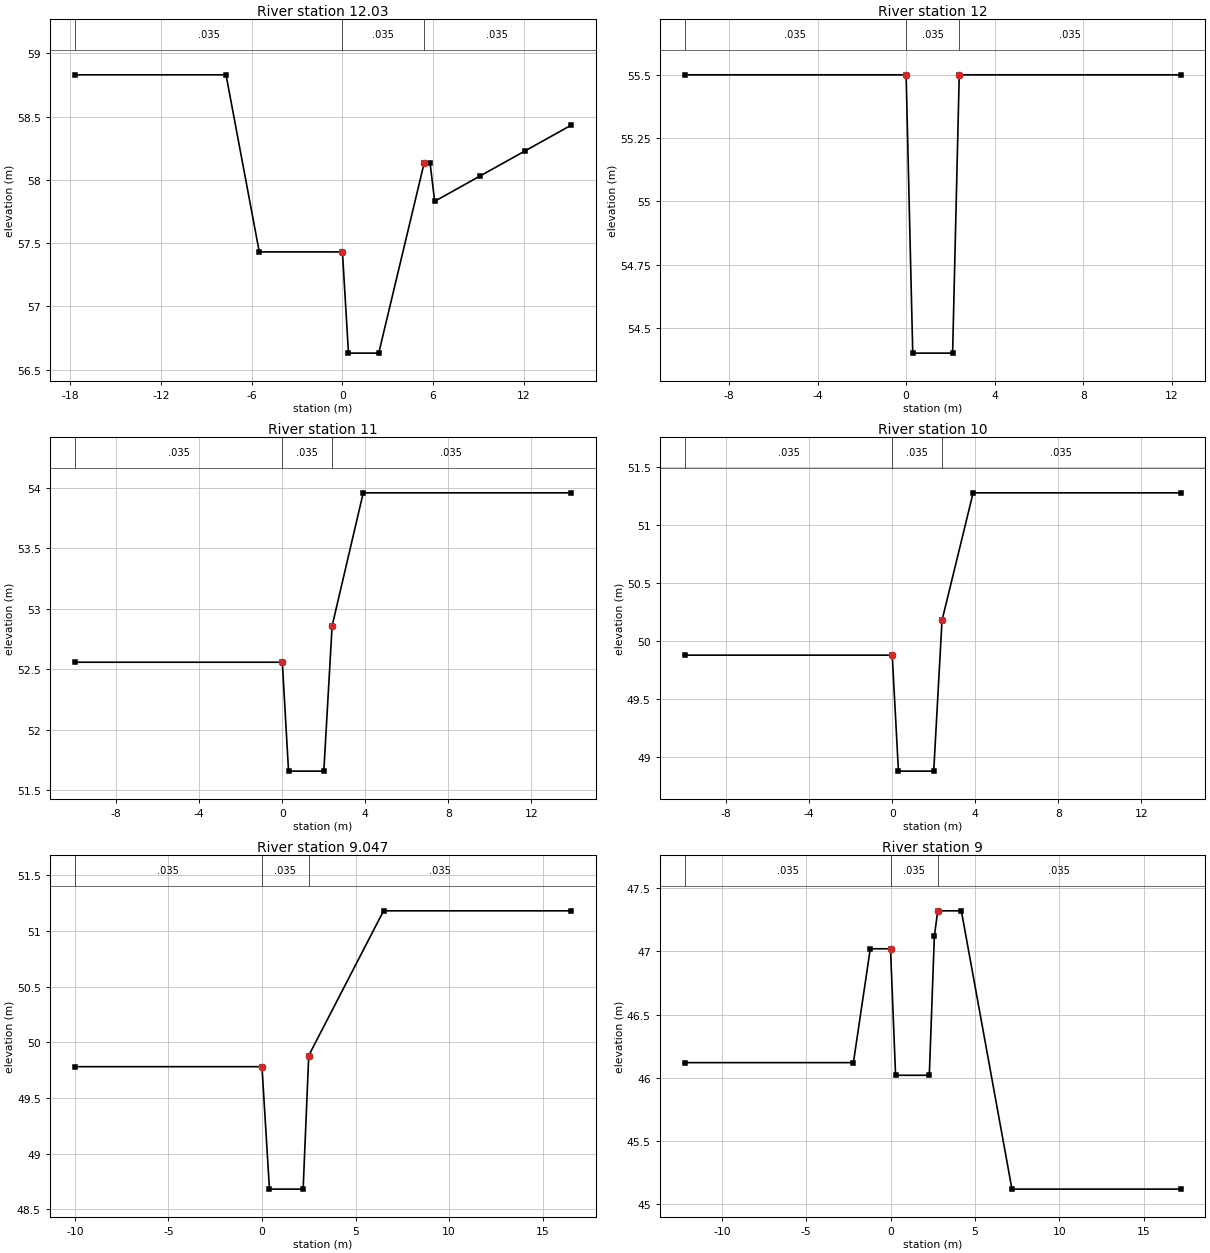
Type RM Length L Ch R = 1 ,12.03   ,30,30,30
#Sta/Elev= 12
   -17.7   58.83    -7.7   58.83    -5.5   57.43       0   57.43      .4   56.63
     2.4   56.63     5.4   58.13     5.8   58.13     6.1   57.83     9.1   58.03
    12.1   58.23    15.1   58.43
#Mann= 3 , 0 , 0
   -17.7    .035       0       0    .035       0     5.4    .035       0
Bank Sta=0,5.4
XS Rating Curve= 0
Exp/Cntr=.3,.1

Type RM Length L Ch R = 1 ,12      ,50,50,50
#Sta/Elev= 6
     -10    55.5       0    55.5      .3    54.4     2.1    54.4     2.4    55.5
    12.4    55.5
#Mann= 3 , 0 , 0
     -10    .035       0       0    .035       0     2.4    .035       0
Bank Sta=0,2.4
XS Rating Curve= 0
Exp/Cntr=.3,.1

Type RM Length L Ch R = 1 ,11      ,50,50,50
#Sta/Elev= 7
     -10   52.56       0   52.56      .3   51.66       2   51.66     2.4   52.86
     3.9   53.96    13.9   53.96
#Mann= 3 , 0 , 0
     -10    .035       0       0    .035       0     2.4    .035       0
Bank Sta=0,2.4
XS Rating Curve= 0
Exp/Cntr=.3,.1

Type RM Length L Ch R = 1 ,10      ,3,3,3
#Sta/Elev= 7
     -10   49.88       0   49.88      .3   48.88       2   48.88     2.4   50.18
     3.9   51.28    13.9   51.28
#Mann= 3 , 0 , 0
     -10    .035       0       0    .035       0     2.4    .035       0
Bank Sta=0,2.4
XS Rating Curve= 0
Exp/Cntr=.3,.1

Type RM Length L Ch R = 1 ,9.047   ,47,47,47
#Sta/Elev= 7
     -10   49.78       0   49.78      .4   48.68     2.2   48.68     2.5   49.88
     6.5   51.18    16.5   51.18
#Mann= 3 , 0 , 0
     -10    .035       0       0    .035       0     2.5    .035       0
Bank Sta=0,2.5
XS Rating Curve= 0
Exp/Cntr=.3,.1

Type RM Length L Ch R = 1 ,9       ,50,50,50
#Sta/Elev= 11
   -12.2   46.12    -2.2   46.12    -1.2   47.02       0   47.02      .3   46.02
     2.3   46.02     2.6   47.12     2.8   47.32     4.2   47.32     7.2   45.12
    17.2   45.12
#Mann= 3 , 0 , 0
   -12.2    .035       0       0    .035       0     2.8    .035       0
Bank Sta=0,2.8
XS Rating Curve= 0
Exp/Cntr=.3,.1

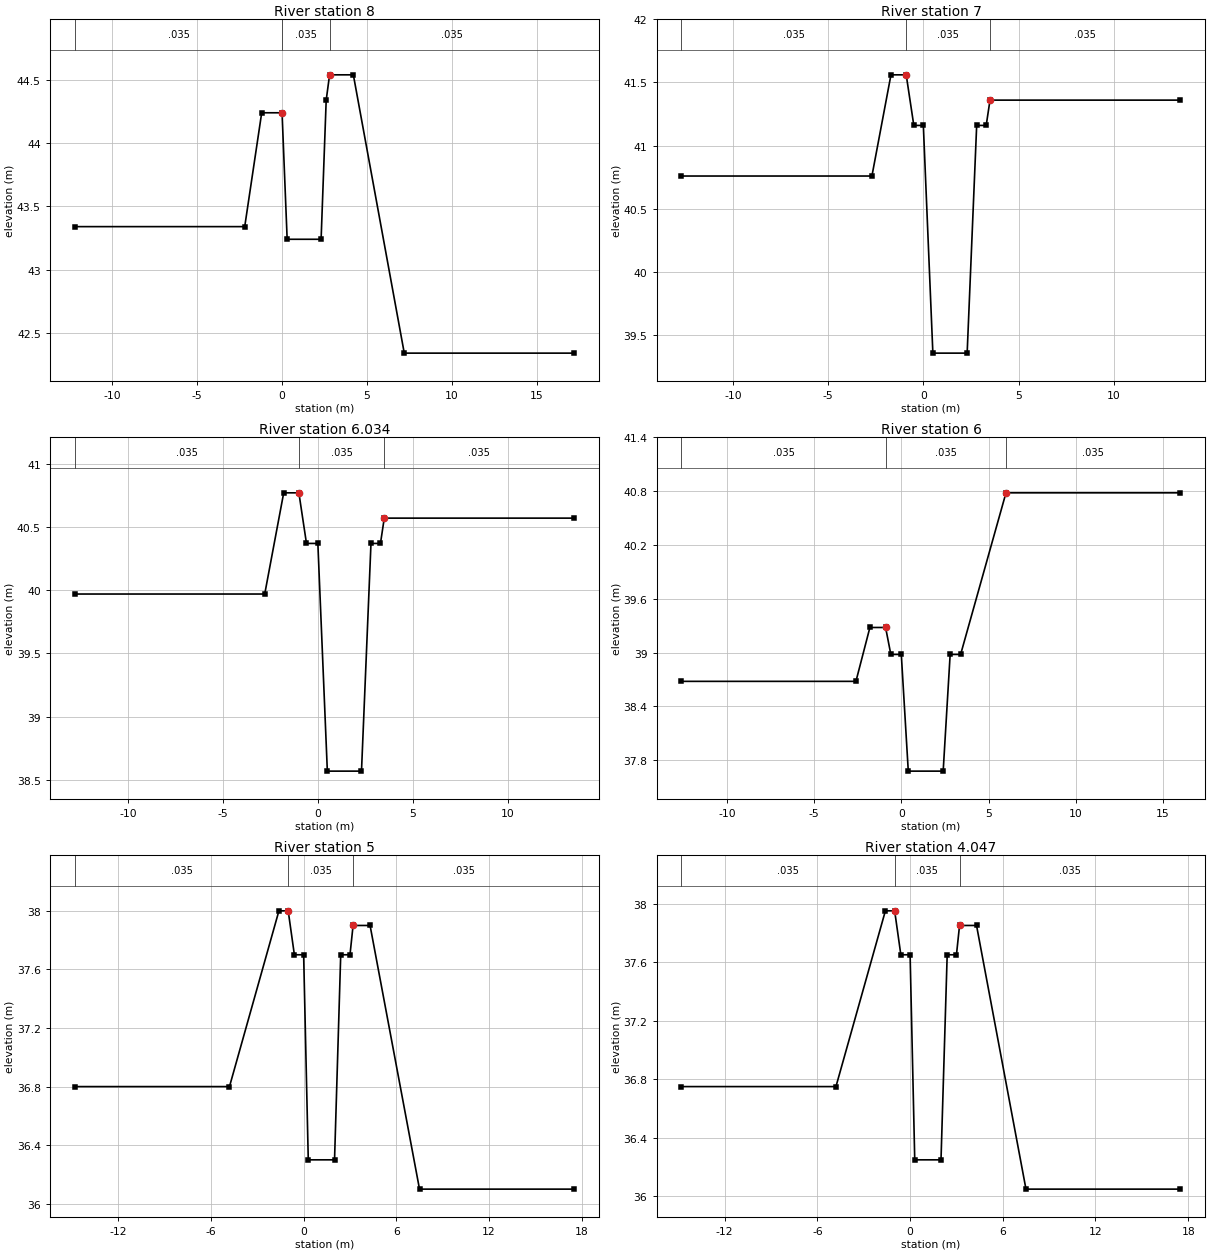
Type RM Length L Ch R = 1 ,8       ,50,50,50
#Sta/Elev= 11
   -12.2   43.34    -2.2   43.34    -1.2   44.24       0   44.24      .3   43.24
     2.3   43.24     2.6   44.34     2.8   44.54     4.2   44.54     7.2   42.34
    17.2   42.34
#Mann= 3 , 0 , 0
   -12.2    .035       0       0    .035       0     2.8    .035       0
Bank Sta=0,2.8
XS Rating Curve= 0
Exp/Cntr=.3,.1

Type RM Length L Ch R = 1 ,7       ,16,16,16
#Sta/Elev= 12
   -12.7   40.76    -2.7   40.76    -1.7   41.56     -.9   41.56     -.5   41.16
       0   41.16      .5   39.36     2.3   39.36     2.8   41.16     3.3   41.16
     3.5   41.36    13.5   41.36
#Mann= 3 , 0 , 0
   -12.7    .035       0     -.9    .035       0     3.5    .035       0
Bank Sta=-.9,3.5
XS Rating Curve= 0
Exp/Cntr=.3,.1

Type RM Length L Ch R = 1 ,6.034   ,34,34,34
#Sta/Elev= 12
   -12.8   39.97    -2.8   39.97    -1.8   40.77      -1   40.77     -.6   40.37
       0   40.37      .5   38.57     2.3   38.57     2.8   40.37     3.3   40.37
     3.5   40.57    13.5   40.57
#Mann= 3 , 0 , 0
   -12.8    .035       0      -1    .035       0     3.5    .035       0
Bank Sta=-1,3.5
XS Rating Curve= 0
Exp/Cntr=.3,.1

Type RM Length L Ch R = 1 ,6       ,50,50,50
#Sta/Elev= 12
   -12.6   38.68    -2.6   38.68    -1.8   39.28     -.9   39.28     -.6   38.98
       0   38.98      .4   37.68     2.4   37.68     2.8   38.98     3.4   38.98
       6   40.78      16   40.78
#Mann= 3 , 0 , 0
   -12.6    .035       0     -.9    .035       0       6    .035       0
Bank Sta=-.9,6
XS Rating Curve= 0
Exp/Cntr=.3,.1

Type RM Length L Ch R = 1 ,5       ,3,3,3
#Sta/Elev= 14
   -14.8    36.8    -4.8    36.8    -1.6      38      -1      38     -.6    37.7
       0    37.7      .3    36.3       2    36.3     2.4    37.7       3    37.7
     3.2    37.9     4.3    37.9     7.5    36.1    17.5    36.1
#Mann= 3 , 0 , 0
   -14.8    .035       0      -1    .035       0     3.2    .035       0
Bank Sta=-1,3.2
XS Rating Curve= 0
Exp/Cntr=.3,.1

Type RM Length L Ch R = 1 ,4.047   ,47,47,47
#Sta/Elev= 14
   -14.8   36.75    -4.8   36.75    -1.6   37.95      -1   37.95     -.6   37.65
       0   37.65      .3   36.25       2   36.25     2.4   37.65       3   37.65
     3.2   37.85     4.3   37.85     7.5   36.05    17.5   36.05
#Mann= 3 , 0 , 0
   -14.8    .035       0      -1    .035       0     3.2    .035       0
Bank Sta=-1,3.2
XS Rating Curve= 0
Exp/Cntr=.3,.1

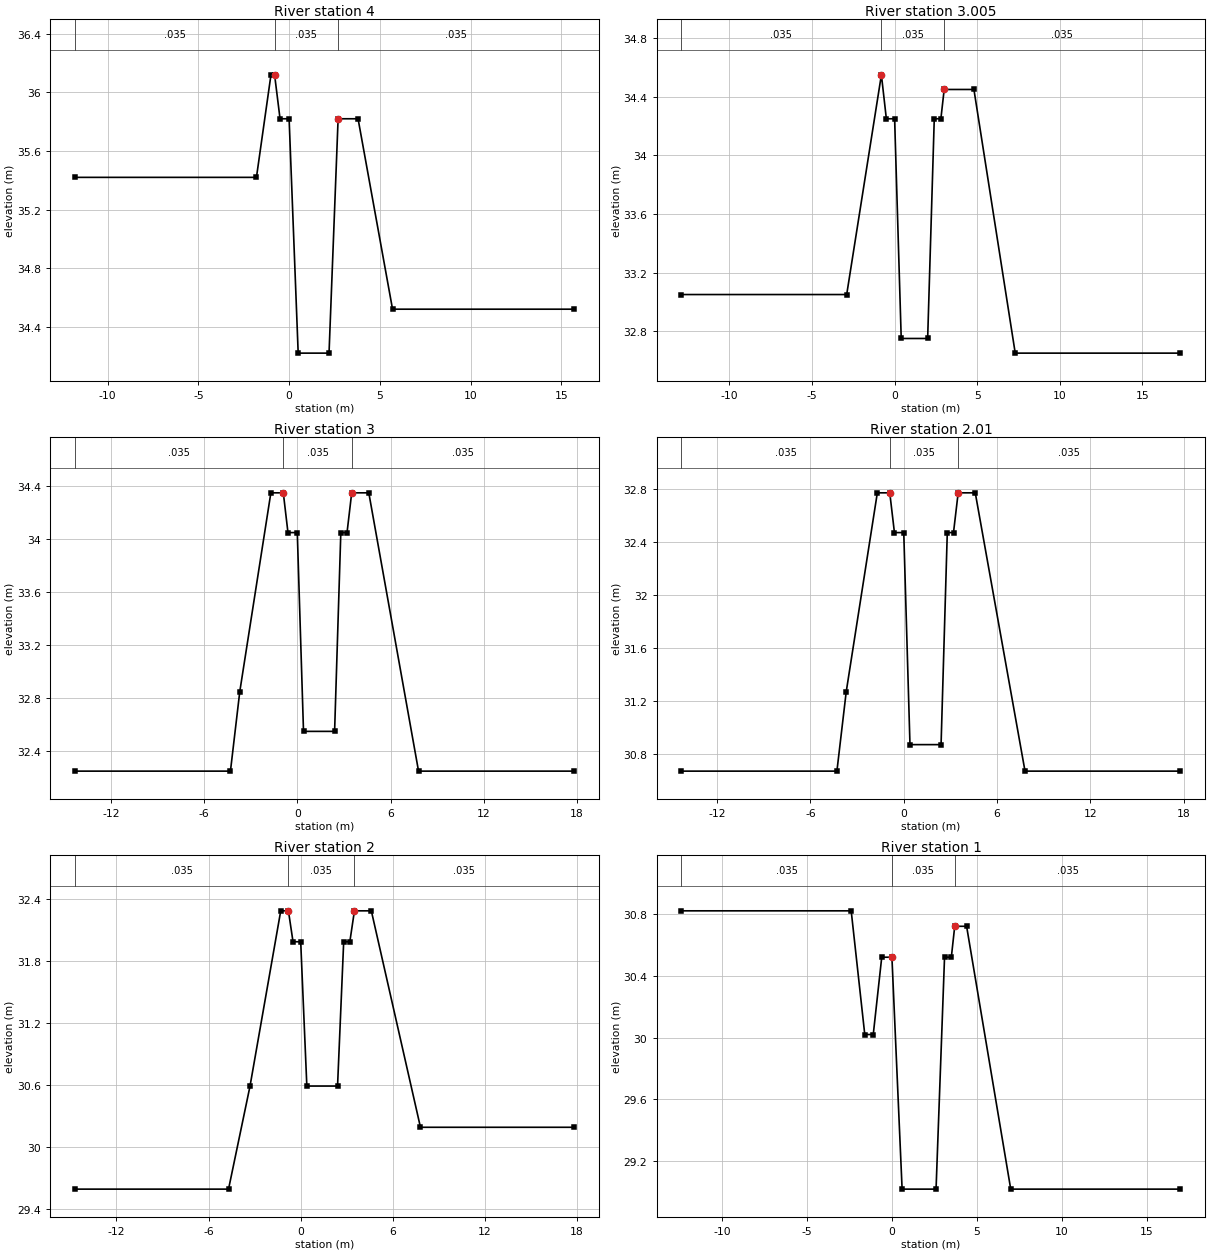
Type RM Length L Ch R = 1 ,4       ,45,45,45
#Sta/Elev= 12
   -11.8   35.42    -1.8   35.42      -1   36.12     -.8   36.12     -.5   35.82
       0   35.82      .5   34.22     2.2   34.22     2.7   35.82     3.8   35.82
     5.7   34.52    15.7   34.52
#Mann= 3 , 0 , 0
   -11.8    .035       0     -.8    .035       0     2.7    .035       0
Bank Sta=-.8,2.7
XS Rating Curve= 0
Exp/Cntr=.3,.1

Type RM Length L Ch R = 1 ,3.005   ,5,5,5
#Sta/Elev= 13
   -12.9   33.05    -2.9   33.05     -.8   34.55     -.5   34.25       0   34.25
      .4   32.75       2   32.75     2.4   34.25     2.8   34.25       3   34.45
     4.8   34.45     7.3   32.65    17.3   32.65
#Mann= 3 , 0 , 0
   -12.9    .035       0     -.8    .035       0       3    .035       0
Bank Sta=-.8,3
XS Rating Curve= 0
Exp/Cntr=.3,.1

Type RM Length L Ch R = 1 ,3       ,40,40,40
#Sta/Elev= 15
   -14.3   32.25    -4.3   32.25    -3.7   32.85    -1.7   34.35     -.9   34.35
     -.6   34.05       0   34.05      .4   32.55     2.4   32.55     2.8   34.05
     3.2   34.05     3.5   34.35     4.6   34.35     7.8   32.25    17.8   32.25
#Mann= 3 , 0 , 0
   -14.3    .035       0     -.9    .035       0     3.5    .035       0
Bank Sta=-.9,3.5
XS Rating Curve= 0
Exp/Cntr=.3,.1

Type RM Length L Ch R = 1 ,2.01    ,10,10,10
#Sta/Elev= 15
   -14.3   30.67    -4.3   30.67    -3.7   31.27    -1.7   32.77     -.9   32.77
     -.6   32.47       0   32.47      .4   30.87     2.4   30.87     2.8   32.47
     3.2   32.47     3.5   32.77     4.6   32.77     7.8   30.67    17.8   30.67
#Mann= 3 , 0 , 0
   -14.3    .035       0     -.9    .035       0     3.5    .035       0
Bank Sta=-.9,3.5
XS Rating Curve= 0
Exp/Cntr=.3,.1

Type RM Length L Ch R = 1 ,2       ,50,50,50
#Sta/Elev= 15
   -14.7   29.59    -4.7   29.59    -3.3   30.59    -1.3   32.29     -.8   32.29
     -.5   31.99       0   31.99      .4   30.59     2.4   30.59     2.8   31.99
     3.2   31.99     3.5   32.29     4.6   32.29     7.8   30.19    17.8   30.19
#Mann= 3 , 0 , 0
   -14.7    .035       0     -.8    .035       0     3.5    .035       0
Bank Sta=-.8,3.5
XS Rating Curve= 0
Exp/Cntr=.3,.1

Type RM Length L Ch R = 1 ,1       ,50,50,50
#Sta/Elev= 14
   -12.4   30.82    -2.4   30.82    -1.6   30.02    -1.1   30.02     -.6   30.52
       0   30.52      .6   29.02     2.6   29.02     3.1   30.52     3.5   30.52
     3.7   30.72     4.4   30.72       7   29.02      17   29.02
#Mann= 3 , 0 , 0
   -12.4    .035       0       0    .035       0     3.7    .035       0
Bank Sta=0,3.7
XS Rating Curve= 0
Exp/Cntr=.3,.1

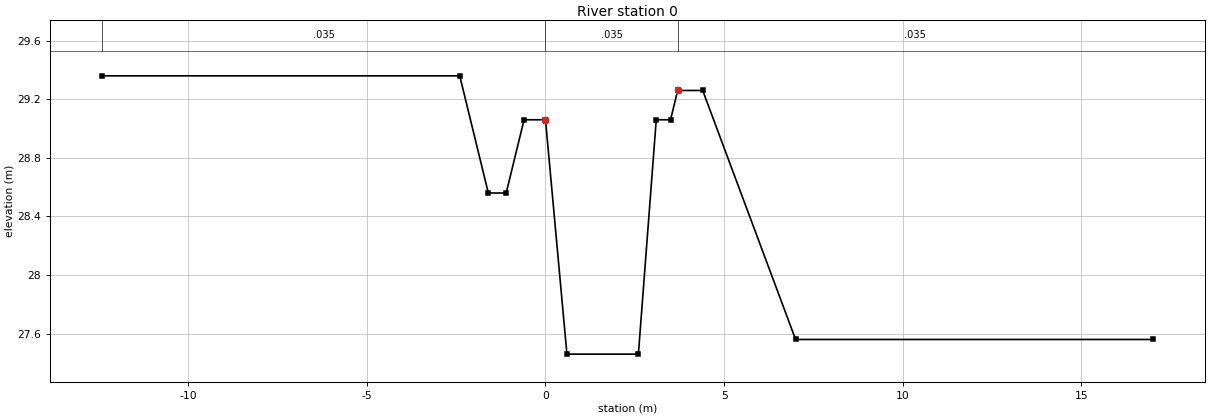
Type RM Length L Ch R = 1 ,0       ,0,0,0
#Sta/Elev= 14
   -12.4   29.36    -2.4   29.36    -1.6   28.56    -1.1   28.56     -.6   29.06
       0   29.06      .6   27.46     2.6   27.46     3.1   29.06     3.5   29.06
     3.7   29.26     4.4   29.26       7   27.56      17   27.56
#Mann= 3 , 0 , 0
   -12.4    .035       0       0    .035       0     3.7    .035       0
Bank Sta=0,3.7
XS Rating Curve= 0
Exp/Cntr=.3,.1

Chan Stop Cuts=-1